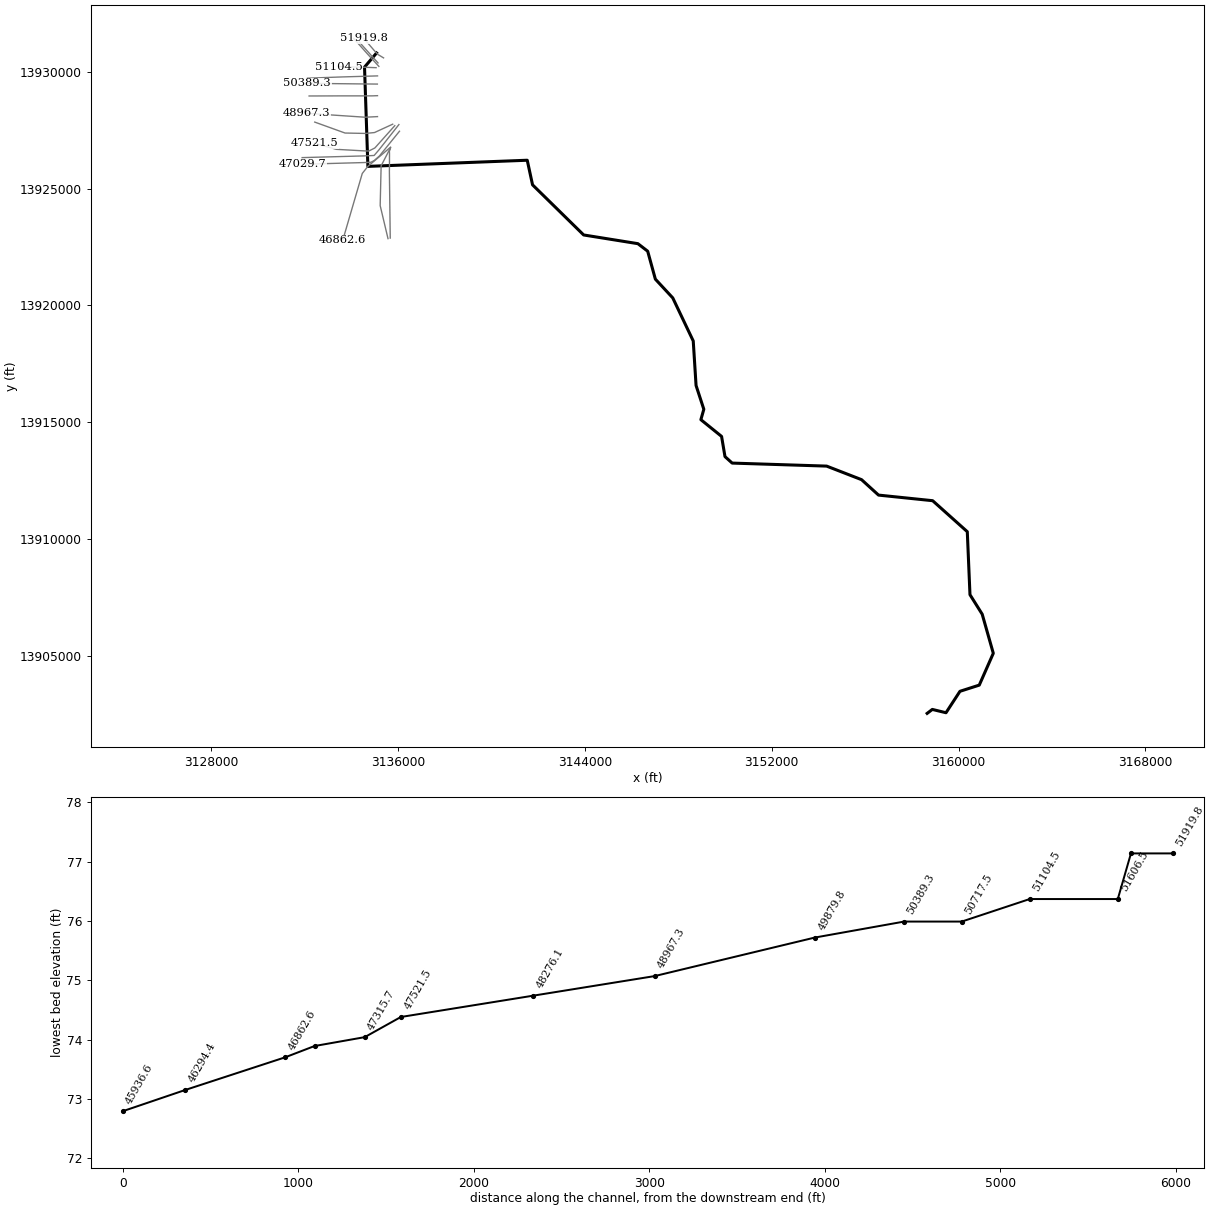
--- P130-00-00.prj (project) ---

Proj Title=P130-00-00
Current Plan=p02
Default Exp/Contr=.3,.1
English Units
Geom File=g01
Flow File=f02
Flow File=f01
Plan File=p01
Plan File=p02
Y Axis Title=Elevation
X Axis Title(PF)=Main Channel Distance
X Axis Title(XS)=Station
BEGIN DESCRIPTION:
HCFCD MODEL SUMMARY METADATA
The purpose of this summary is to document the high points of hydrologic and hydraulic models filed within the HCFCD Model and Map Management (M3) system.  The document includes references to the project that prompted the creation or update of the model.
DESCRIPTION OF PROJECT:
The following model was the hydraulic model which represented the effective condition of Harris County’s watersheds.
PURPOSE OF PROJECT:
Development of effective models to support the National Flood Insurance Program.
HCFCD Watershed Unit ID: P
M3 Study Identifier: 2014_Effective_P
Engineer: HCFCD
Project Name: Effective FEMA Study for watershed Garner Creek (P)
Study Completion Date: [No Data]
FEMA Case Number: 10-06-2789P
FEMA Effective Date: 06/09/2014
Vertical Datum: NAVD 1988
Datum Note: 2001 ADJ
HYDRAULICS
HCFCD Unit No.:  P130-00-00
Hydraulic Program Name: HEC-RAS
Hydraulic Program Version: 3.0.1
Steady Hydraulic Model: Yes
Unsteady Hydraulic Model: No
Update1:The effective FEMA hydraulic model for unit number P130-00-00 has been updated by FEMA LOMR 15-06-1289P with an effective date of 10/30/2015.
Update2:The effective FEMA hydraulic model for unit number P130-00-00 has been updated by FEMA LOMR 16-06-0003P with an effective date of 05/29/2016.
Update 3:The effective FEMA hydraulic model for unit number P130-00-00 has been updated by FEMA LOMR 19-06-1346P with an effective date of xx/xx/2020.
END DESCRIPTION:
DSS File=dss
DSS Export Rating Curves= 0
DSS Export Rating Curve Sorted= 0
DSS Export Volume Flow Curves= 0
DXF OffsetX= 0
DXF OffsetY= 0
DXF ScaleX= 1
DXF ScaleY= 10

--- P130-00-00.p02 (plan) ---

Plan Title=FEMA Effective Multi-Profile 2020
Program Version=5.07
Short Identifier=Eff+LOMR MP
Geom File=g01
Flow File=f01
Subcritical Flow
K Sum by GR= 0
Std Step Tol= 0.01
Critical Tol= 0.01
Num of Std Step Trials= 20
Max Error Tol= 0.3
Flow Tol Ratio= 0.001
Split Flow NTrial= 30
Split Flow Tol= 0.02
Split Flow Ratio= 0.02
Log Output Level= 0
Friction Slope Method= 1
Unsteady Friction Slope Method= 2
Unsteady Bridges Friction Slope Method= 1
Parabolic Critical Depth
Global Vel Dist= 0 , 0 , 0
Global Log Level= 0
CheckData=True
Encroach Param=-1 ,0,0, 0
BEGIN DESCRIPTION:
FEMA Effective Multi-Profile June 2007 + LOMR 15-06-1289P + LOMR 16-06-0003P+ LOMR 19-06-1346P
END DESCRIPTION:
Computation Interval=1HOUR
Output Interval=1HOUR
Instantaneous Interval=1HOUR
Mapping Interval=1HOUR
Computation Time Step Use Courant=        0
Computation Time Step Use Time Series=    0
Computation Time Step Count To Double=0
Computation Time Step Max Doubling=0
Computation Time Step Max Halving=0
Computation Time Step Residence Courant=0
Run HTab= 0
Run UNet= 0
Run Sediment= 0
Run PostProcess= 0
Run WQNet= 0
Run RASMapper= 0
UNET Theta= 1
UNET Theta Warmup= 1
UNET ZTol= 0.02
UNET ZSATol= 0.1
UNET MxIter= 20
UNET Max Iter WO Improvement= 0
UNET MaxInSteps= 20
UNET DtIC= 0
UNET DtMin= 0
UNET MaxCRTS= 20
UNET WFStab= 2
UNET SFStab= 1
UNET WFX= 1
UNET SFX= 1
UNET 1D Methodology=Finite Difference
UNET DSS MLevel= 4
UNET Pardiso=0
UNET DZMax Abort= 100
UNET Use Existing IB Tables=-1
UNET Froude Reduction=False
UNET Froude Limit= 0.8
UNET Froude Power= 4
UNET D1 Cores= 0
UNET D2 Coriolis=0
UNET D2 Cores= 0
UNET D2 Theta= 1
UNET D2 Theta Warmup= 1
UNET D2 Z Tol= 0.01
UNET D2 Volume Tol= 0.01
UNET D2 Max Iterations= 20
UNET D2 Equation= 0
UNET D2 RampUpFraction=0.1
UNET D2 TimeSlices= 1
UNET D2 BCVolumeCheck=0
UNET D1D2 MaxIter= 0
UNET D1D2 ZTol=0.01
UNET D1D2 QTol=0.1
UNET D1D2 MinQTol=1
Write IC File= 0
Write IC File at Fixed DateTime=0
Write IC File at Sim End=0
Echo Input=False
Echo Parameters=False
Echo Output=False
Write Detailed= 0
HDF Write Warmup=0
HDF Write Time Slices=0
HDF Flush=0
HDF Face Node Velocities=0
HDF Compression= 1
HDF Chunk Size= 1
HDF Spatial Parts= 1
HDF Use Max Rows=0
HDF Fixed Rows= 1
Calibration Method= 0
Calibration Iterations= 20
Calibration Max Change=0.05
Calibration Tolerance=0.2
Calibration Maximum=1.5
Calibration Minimum=0.5
Calibration Optimization Method= 1
WQ AD Non Conservative
WQ ULTIMATE=-1
WQ Max Comp Step=1HOUR
WQ Output Interval=15MIN
WQ Output Selected Increments= 0
WQ Output face flow=0
WQ Output face velocity=0
WQ Output face area=0
WQ Output face dispersion=0
WQ Output cell volume=0
WQ Output cell surface area=0
WQ Output cell continuity=0
WQ Output cumulative cell continuity=0
WQ Output face conc=0
WQ Output face dconc_dx=0
WQ Output face courant=0
WQ Output face peclet=0
WQ Output face adv mass=0
WQ Output face disp mass=0
WQ Output cell mass=0
WQ Output cell source sink temp=0
WQ Output nsm pathways=0
WQ Output nsm derived pathways=0
WQ Output MaxMinRange=-1
WQ Daily Max Min Mean=-1
WQ Daily Range=0
WQ Daily Time=0
WQ Create Restart=0
WQ Fixed Restart=0
WQ System Summary=0
WQ Write To DSS=0
WQ Use Fixed Temperature=0
Sorting and Armoring Iterations= 10
XS Update Threshold= 0.02
Bed Roughness Predictor= 0
Hydraulics Update Threshold= 0.02
Energy Slope Method= 1
Volume Change Method= 1
Sediment Retention Method= 0
XS Weighting Method= 0
Number of US Weighted Cross Sections= 1
Number of DS Weighted Cross Sections= 1
Upstream XS Weight=0
Main XS Weight=1
Downstream XS Weight=0
Number of DS XS's Weighted with US Boundary= 1
Upstream Boundary Weight= 1
Weight of XSs Associated with US Boundary= 0
Number of US XS's Weighted with DS Boundary= 1
Downstream Boundary Weight= 0.5
Weight of XSs Associated with DS Boundary= 0.5
Percentile Method= 0
Sediment Output Level= 3
Mass or Volume Output= 0
Output Increment Type= 1
Profile and TS Output Increment= 1
XS Output Flag= 0
XS Output Increment= 10
Write Gradation File= 0
Read Gradation Hotstart= 0
Write HDF5 File= 1
Write Binary Output= 1
Write DSS Sediment File= 0
SV Curve= 0
Specific Gage Flag= 0

--- P130-00-00.p01 (plan) ---

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Plan Title=FEMA Effective Floodway 2020
Short Identifier=Eff+LOMR FW
Geom File=g01
Flow File=f02
Std Step Tol= 0.003
Critical Tol= 0.003
Max Error Tol= 0.1
Encroach Param=-1 ,0,0, 2
Encroach River=P130-00-00
Encroach Reach=P130-00-00_0014
Encroach Node=51919.8
       1 4937.65 5062.35
Encroach Node=51681.5
       1    4925    5075
Encroach Node=51644
       1    4925    5075
Encroach Node=51606.5
       1    4928    5156
Encroach Node=51104.5
       1    4928    5156
Encroach Node=50911
       1    4928    5156
Encroach Node=50717.5
       1    4928    5851
Encroach Node=50389.3
       1  4928.1  5851.1
Encroach Node=49879.8
       1  4928.1  5851.1
Encroach Node=48967.3
       1  4936.8  5063.2
Encroach Node=48276.1
       1  4932.8  5086.2
Encroach Node=47521.5
       1  4932.8  5086.2
Encroach Node=47315.7
       1  4950.4  5056.4
Encroach Node=47172.7
       1  4950.4  5056.4
Encroach Node=47029.7
       1  4950.4  5056.4
Encroach Node=46862.6
       1  4868.1  5064.3
Encroach Node=46294.4
       1  4938.4  5064.3
Encroach Node=45936.6
       1  4938.4  5064.3
Encroach Node=45887.9
       1  4938.4  5064.3
Encroach Node=45858.9
       1  4938.4  5064.3
Encroach Node=45829.9
       1  4938.4  5064.3
Encroach Node=45692.5
       1  4941.3    5265
Encroach Node=45292.0
       1  4942.3    5500
Encroach Node=44793.4
       1  4962.2 5097.35
Encroach Node=44743.4
       1    4937 5055.83
Encroach Node=44712.4
       1  4962.5    5980
Encroach Node=44681.4
       1    4938 5055.71
Encroach Node=44451.0
       1    4870    5073
Encroach Node=44181.0
       1 4918.63    5088
Encroach Node=43695.1
       1    4914    5114
Encroach Node=43262.1
       1    4776    5129
Encroach Node=42585.9
       1    4912    5093
Encroach Node=41802.7
       1  4913.2  5085.7
Encroach Node=41178.8
       1  4913.2  5085.7
Encroach Node=40856.8
       1  4913.2  5085.7
Encroach Node=40799.8
       1  4913.2  5085.7
Encroach Node=40742.8
       1  4913.2  5085.7
Encroach Node=40493.7
       1  4913.2  5106.6
Encroach Node=40057.2
       1  4945.5  5106.6
Encroach Node=39811.5
       1    4701  5106.6
Encroach Node=39010.7
       1    4170  5043.7
Encroach Node=38376.9
       1    4345    5050
Encroach Node=37911.8
       1    4500    5050
Encroach Node=37118.1
       1    4500  5049.3
Encroach Node=36997.0
       1    3896    5090
Encroach Node=36964.9
       1    3995    5090
Encroach Node=36932.8
       1    3895    5090
Encroach Node=36766.0
       1    4000    5150
Encroach Node=36623.8
       1    4010    5100
Encroach Node=36591.8
       1  4308.2    5100
Encroach Node=36559.8
       1    4010    5100
Encroach Node=36116.9
       1    4230    5063
Encroach Node=36087.9
       1    4190    5050
Encroach Node=35094.3
       1    4690    5105
Encroach Node=34160.0
       1    4900    5100
Encroach Node=33284.4
       1  4938.2    5097
Encroach Node=33154.5
       1    4903    5097
Encroach Node=32983.5
       1    4903    5097
Encroach Node=32812.5
       1    4903    5097
Encroach Node=32701.4
       1    4901    5091
Encroach Node=32661.4
       1    4901    5091
Encroach Node=32621.4
       1    4901    5091
Encroach Node=32371.9
       1  4958.6  5033.6
Encroach Node=31976.7
       1  4973.2  5037.7
Encroach Node=31489.9
       1  4928.6    5060
Encroach Node=30858.0
       1    4940    5060
Encroach Node=30734.8
       1    4911  5079.5
Encroach Node=30716.3
       1    4911  5079.5
Encroach Node=30697.8
       1    4911  5079.5
Encroach Node=30188.2
       1    4880    5120
Encroach Node=29377.1
       1    4880  5082.5
Encroach Node=28588.1
       1    4910  5069.7
Encroach Node=27772.6
       1    4920    5075
Encroach Node=27259.5
       1    4935    5065
Encroach Node=27170.1
       1  4934.5  5057.4
Encroach Node=27143.1
       1  4934.5  5057.4
Encroach Node=27116.1
       1  4934.5  5057.4
Encroach Node=26711.8
       1    4920    5090
Encroach Node=26519.3
       1    4910    5090
Encroach Node=25741.4
       1    4930    5090
Encroach Node=25436.0
       1    4890    5080
Encroach Node=24637.8
       1    4940    5080
Encroach Node=24175.7
       1    4890    5110
Encroach Node=23603.6
       1    4890    5110
Encroach Node=23007.2
       1    4775    5160
Encroach Node=22793.7
       1    4675    5225
Encroach Node=22737.5
       1    4675    5225
Encroach Node=22681.3
       1    4675    5225
Encroach Node=22311.2
       1    4525    5100
Encroach Node=22073.6
       1    4570    5160
Encroach Node=22047.1
       1    4570    5160
Encroach Node=22020.6
       1    4570    5160
Encroach Node=21261.7
       1    4500    5061
Encroach Node=20642.8
       1    4610    5160
Encroach Node=20100.3
       1    4395    5090
Encroach Node=19487.2
       1  4862.4  5112.2
Encroach Node=18553.8
       1  4781.1  5057.2
Encroach Node=17618.7
       1 4596.77 5068.21
Encroach Node=16936.3
       1 4430.72 5093.01
Encroach Node=16634.8
       1    4157    5126
Encroach Node=16603.3
       1    4157    5134
Encroach Node=16571.8
       1    4157    5134
Encroach Node=15659.5
       1    4552    5520
Encroach Node=15039.5
       1    4459    5350
Encroach Node=14428.3
       1    4355    5220
Encroach Node=13853.7
       1    4355    5115
Encroach Node=13302.5
       1    4275    5192
Encroach Node=12700.3
       1    4275    5188
Encroach Node=11732.7
       1    4630    5440
Encroach Node=11317.6
       1    4500    5184
Encroach Node=10650.1
       1    4275    5212
Encroach Node=10207.9
       1    4000    5180
Encroach Node=9774.3
       1    3819    5164
Encroach Node=9308.9
       1    4904    5401
Encroach Node=8875.9
       1 4941.64    5417
Encroach Node=8448.1
       1    4847    5342
Encroach Node=7951.8
       1    4843    5446
Encroach Node=7609.0
       1    5785    6610
Encroach Node=7438.9
       1    4928    5751
Encroach Node=7303.8
       1    4452    6557
Encroach Node=7293.8
       1    3650    5800
Encroach Node=7257.8
       1    3650    5800
Encroach Node=7221.8
       1    3650    5800
Encroach Node=7180.1
       1    3650    5800
Encroach Node=7033.0
       1    3650    5800
Encroach Node=6998.0
       1    3650    5800
Encroach Node=6963.0
       1    3650    5800
Encroach Node=6344.4
       1    3700    5670
Encroach Node=5584.1
       1    4000    5615
Encroach Node=5573.1
       1    4000    5615
Encroach Node=5562.1
       1    4000    5615
Encroach Node=5461.1
       1    4000    5550
Encroach Node=5449.6
       1    4000    5550
Encroach Node=5438.1
       1    4000 5560.84
Encroach Node=4989.1
       1    4100    5540
Encroach Node=4337.7
       1    4400 5614.63
Encroach Node=3440.4
       1    4270 5382.27
Encroach Node=2611.8
       1    4490 5857.85
Encroach Node=2290.7
       1    4490    6000
Encroach Node=1400.0
       1  4652.5    5500
FEMA Effective Floodway June 2007 + LOMR 15-06-1289P + LOMR 16-06-0003P+ LOMR 19-06-1346P

--- P130-00-00.f01 (steady flow) ---

Flow Title=Effective MP 2014
Version=Version 3.0.1  May 2012
Number of Profiles= 4
Profile Names=10PCT_10yr,2PCT_50yr,1PCT_100yr,0.2PCT_500yr
River Rch & RM=P130-00-00,P130-00-00_0014 ,51919.8
     315     434     495     650
River Rch & RM=P130-00-00,P130-00-00_0014 ,50389.3
    2032    2838    3252    4291
River Rch & RM=P130-00-00,P130-00-00_0014 ,48967.3
    1332    1828    2100    3660
River Rch & RM=P130-00-00,P130-00-00_0014 ,47521.5
     619     800     929    3019
River Rch & RM=P130-00-00,P130-00-00_0014 ,47315.7
     518     654     762    2928
River Rch & RM=P130-00-00,P130-00-00_0014 ,46862.6
    1099    1610    1816    4295
River Rch & RM=P130-00-00,P130-00-00_0014 ,44743.4
    1298    1900    2171    4714
River Rch & RM=P130-00-00,P130-00-00_0014 ,43695.1
    1397    2043    2346    4921
River Rch & RM=P130-00-00,P130-00-00_0014 ,41802.7
    1472    2197    2524    5089
River Rch & RM=P130-00-00,P130-00-00_0014 ,39010.7
    1638    2397    2771    4975
River Rch & RM=P130-00-00,P130-00-00_0014 ,36087.9
    1811    2607    3030    4856
River Rch & RM=P130-00-00,P130-00-00_0014 ,35094.3
    2365    3328    3831    6193
River Rch & RM=P130-00-00,P130-00-00_0014 ,34160
    2886    4006    4584    7451
River Rch & RM=P130-00-00,P130-00-00_0014 ,32701.4
    3002    4168    4776    7403
River Rch & RM=P130-00-00,P130-00-00_0014 ,30188.2
    3203    4446    5106    7321
River Rch & RM=P130-00-00,P130-00-00_0014 ,29377.1
    3268    4538    5213    7418
River Rch & RM=P130-00-00,P130-00-00_0014 ,27259.5
    3437    4779    5491    7672
River Rch & RM=P130-00-00,P130-00-00_0014 ,25741.4
    3558    4952    5691    7854
River Rch & RM=P130-00-00,P130-00-00_0014 ,22793.7
    5727    8370    9622   12417
River Rch & RM=P130-00-00,P130-00-00_0014 ,19487.2
    6101    8606   10155   13160
River Rch & RM=P130-00-00,P130-00-00_0014 ,16634.8
    6996    9860   11378   14794
River Rch & RM=P130-00-00,P130-00-00_0014 ,13853.7
    7158   10082   11632   15172
River Rch & RM=P130-00-00,P130-00-00_0014 ,10650.1
    7344   10338   11925   15608
River Rch & RM=P130-00-00,P130-00-00_0014 ,9308.9
    9141   12881   14905   19698
River Rch & RM=P130-00-00,P130-00-00_0014 ,4337.7
    9426   13467   15554   20664
Boundary for River Rch & Prof#=P130-00-00,P130-00-00_0014 , 1
Up Type= 0
Dn Type= 3
Dn Slope=.0014
Boundary for River Rch & Prof#=P130-00-00,P130-00-00_0014 , 2
Up Type= 0
Dn Type= 3
Dn Slope=.0014
Boundary for River Rch & Prof#=P130-00-00,P130-00-00_0014 , 3
Up Type= 0
Dn Type= 3
Dn Slope=.0014
Boundary for River Rch & Prof#=P130-00-00,P130-00-00_0014 , 4
Up Type= 0
Dn Type= 3
Dn Slope=.0014
DSS Import GetInterval= 0
DSS Import GetPeak= 0
DSS Import FillOption= 0

--- P130-00-00.f02 (steady flow) ---

Flow Title=Effective Floodway 2014
Version=Version 3.0.1  Mar 2001
Number of Profiles= 2
Profile Names=1PCT_100yr,1PCTFloodway_100yr
River Rch & RM=P130-00-00,P130-00-00_0014       ,51919.8
     495     495
River Rch & RM=P130-00-00,P130-00-00_0014       ,50389.3
    3252    3252
River Rch & RM=P130-00-00,P130-00-00_0014       ,48967.3
    2100    2100
River Rch & RM=P130-00-00,P130-00-00_0014       ,47521.5
     929     929
River Rch & RM=P130-00-00,P130-00-00_0014       ,47315.7
     762     762
River Rch & RM=P130-00-00,P130-00-00_0014       ,46862.6
    1816    1816
River Rch & RM=P130-00-00,P130-00-00_0014       ,44743.4
    2171    2171
River Rch & RM=P130-00-00,P130-00-00_0014       ,43695.1
    2346    2346
River Rch & RM=P130-00-00,P130-00-00_0014       ,41802.7
    2524    2524
River Rch & RM=P130-00-00,P130-00-00_0014       ,39010.7
    2771    2771
River Rch & RM=P130-00-00,P130-00-00_0014       ,36087.9
    3030    3030
River Rch & RM=P130-00-00,P130-00-00_0014       ,35094.3
    3831    3831
River Rch & RM=P130-00-00,P130-00-00_0014       ,34160
    4584    4584
River Rch & RM=P130-00-00,P130-00-00_0014       ,32701.4
    4776    4776
River Rch & RM=P130-00-00,P130-00-00_0014       ,30188.2
    5106    5106
River Rch & RM=P130-00-00,P130-00-00_0014       ,29377.1
    5213    5213
River Rch & RM=P130-00-00,P130-00-00_0014       ,27259.5
    5491    5491
River Rch & RM=P130-00-00,P130-00-00_0014       ,25741.4
    5691    5691
River Rch & RM=P130-00-00,P130-00-00_0014       ,22793.7
    9622    9622
River Rch & RM=P130-00-00,P130-00-00_0014       ,19487.2
   10155   10155
River Rch & RM=P130-00-00,P130-00-00_0014       ,16634.8
   11378   11378
River Rch & RM=P130-00-00,P130-00-00_0014       ,13853.7
   11632   11632
River Rch & RM=P130-00-00,P130-00-00_0014       ,10650.1
   11925   11925
River Rch & RM=P130-00-00,P130-00-00_0014       ,9308.9
   14905   14905
River Rch & RM=P130-00-00,P130-00-00_0014       ,4337.7
   15554   15554
Boundary for River Rch & Prof#=P130-00-00,P130-00-00_0014       , 1
Up Type= 0
Dn Type= 3
Dn Slope=.0014
Boundary for River Rch & Prof#=P130-00-00,P130-00-00_0014       , 2
Up Type= 0
Dn Type= 3
Dn Slope=.0014
DSS Import GetInterval= 0
DSS Import GetPeak= 0
DSS Import FillOption= 0

--- P130-00-00.g01 (geometry) ---

Geom Title=P130-00-00 2020
Program Version=5.07

River Reach=P130-00-00      ,P130-00-00_0014
Reach XY= 30
      3135080.33     13930798.42      3134565.01     13930193.31
      3134708.94     13925949.32      3141531.75       13926212.
      3141759.25       13925160.        3143948.       13923016.
       3146269.5       13922644.      3146688.75       13922322.
      3147017.99     13921126.81      3147763.25       13920324.
      3148639.75       13918483.      3148760.75       13916578.
        3149093.       13915562.        3148967.       13915117.
      3149853.25       13914401.      3149999.25       13913537.
      3150306.75       13913260.       3154351.5       13913131.
        3155847.       13912551.      3156573.75       13911891.
      3158891.24     13911651.42        3160374.       13910326.
        3160489.       13907632.      3161012.75       13906797.
      3161487.75       13905126.       3160886.8     13903764.42
       3160060.5       13903500.      3159462.56     13902583.29
        3158877.       13902725.      3158654.75       13902556.

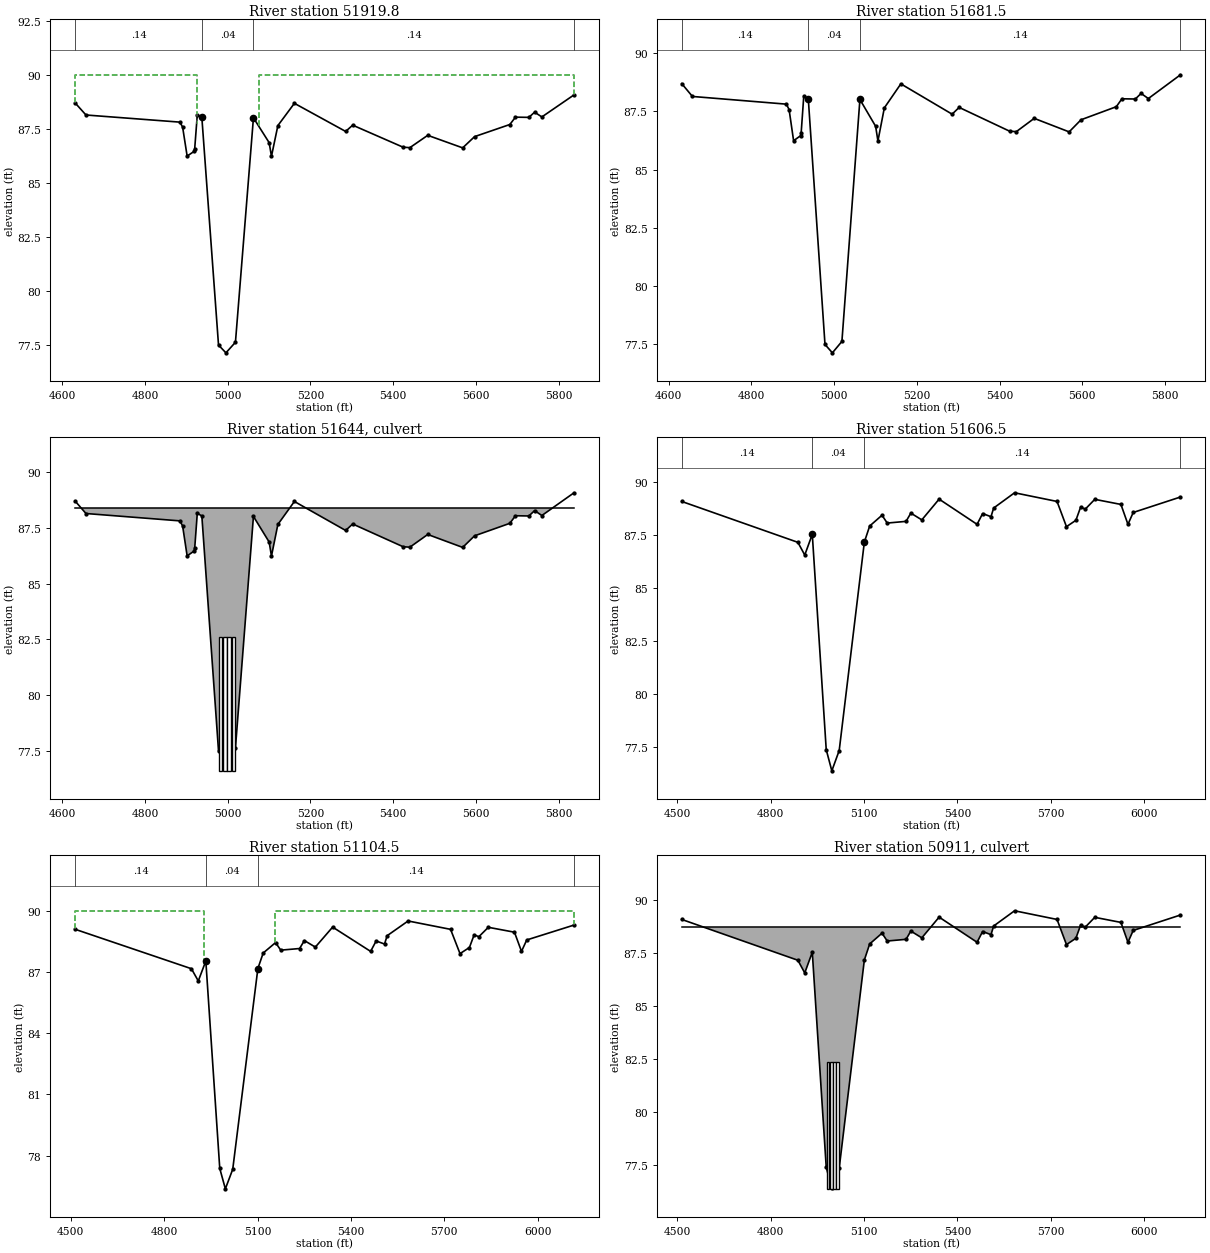
Type RM Length L Ch R = 1 ,51919.8 ,238.3,238.3,238.3
BEGIN DESCRIPTION:
Cross Section 51919.8
END DESCRIPTION:
XS GIS Cut Line= 5
      3135380.26     13930589.15      3135145.22     13930730.51
      3135002.05      13930880.5      3134606.64     13931337.27
      3134525.74     13931425.26
#Sta/Elev= 30
  4631.8   88.69  4657.6   88.14  4884.6   87.81  4891.2   87.58  4902.1   86.24
  4919.2   86.46  4920.4   86.58 4926.65   88.15 4937.65   88.03 4977.95    77.5
 4995.85   77.14 5018.85   77.63 5062.35   88.01 5100.35   86.86  5105.9   86.23
  5121.4   87.65  5161.3   88.68  5285.2   87.38  5302.2   87.67  5424.1   86.65
  5440.4   86.63  5483.6    87.2    5568   86.62  5596.8   87.14    5682    87.7
  5695.6   88.04    5728   88.03  5741.9   88.27  5759.4   88.05  5837.1   89.07
#Mann= 4 ,-1 , 0
  4631.8     .14       0 4937.65     .04       0 5062.35     .14       0
  5837.1      .2       0
#XS Ineff= 2 , 0
       0    4925      90    5075       0      90
Permanent Ineff=
       F       F
Bank Sta=4937.65,5062.35
XS Rating Curve= 0 ,0
Exp/Cntr=0.5,0.3

Type RM Length L Ch R = 1 ,51681.5 ,75,75,75
XS GIS Cut Line= 4
     3135142.443    13930372.916     3134903.032    13930638.929
     3134779.569    13930776.111      3134337.19    13931269.752
#Sta/Elev= 30
  4631.8   88.69  4657.6   88.14  4884.6   87.81  4891.2   87.58  4902.1   86.24
  4919.2   86.46  4920.4   86.58 4926.65   88.15 4937.65   88.03 4977.95    77.5
 4995.85   77.14 5018.85   77.63 5062.35   88.01 5100.35   86.86  5105.9   86.23
  5121.4   87.65  5161.3   88.68  5285.2   87.38  5302.2   87.67  5424.1   86.65
  5440.4   86.63  5483.6    87.2    5568   86.62  5596.8   87.14    5682    87.7
  5695.6   88.04    5728   88.03  5741.9   88.27  5759.4   88.05  5837.1   89.07
#Mann= 4 ,-1 , 0
  4631.8     .14       0 4937.65     .04       0 5062.35     .14       0
  5837.1      .2       0
Bank Sta=4937.65,5062.35
XS Rating Curve= 0 ,0
Exp/Cntr=0.5,0.3

Type RM Length L Ch R = 2 ,51644   ,,,
BEGIN DESCRIPTION:
4 - 8' x 6'
END DESCRIPTION:
Bridge Culvert--1,0,-1,-1, 0
Deck Dist Width WeirC Skew NumUp NumDn MinLoCord MaxHiCord MaxSubmerge Is_Ogee
10,55,2.5,0, 2, 2, , , 0.95, 0, 0,0,,
  4631.8  5837.1
   88.39   88.39
       0       0
  4514.3  6117.1
   88.18   88.18
       0       0
BR Coef=-1 , 0 , 0 ,, 0 ,,,0.8,-1,,0,
WSPro=,,,, 1 ,,,, 0 ,,,, 0 ,,,,-1 ,-1 ,-1 , 0 , 0 , 0 , 0 , 0
Multiple Barrel Culv=2,6,8,55,0.015,0.5,1,10,1,76.6,76.58, 4,Culvert #1  , 0 ,10
  4983.4    4985  4993.4    4995  5003.4    5005  5013.4    5015
BC Culvert Barrel=1,Barrel #1,0
BC Culvert Barrel=2,Barrel #2,0
BC Culvert Barrel=3,Barrel #3,0
BC Culvert Barrel=4,Barrel #4,0
Culvert Bottom n=0.015
BC Design=,, 0 ,, 0 ,,,,,,
BC HTab HWMax=89.07
BC Use User HTab Curves=0
BC User HTab FreeFlow(D)= 0

Type RM Length L Ch R = 1 ,51606.5 ,502,502,502
XS GIS Cut Line= 4
     3135178.652    13930226.971     3134850.606     13930584.25
      3134680.55    13930769.459     3134104.369    13931416.399
#Sta/Elev= 30
  4514.3   89.09  4887.5   87.16  4909.6   86.56  4933.8   87.54  4978.6   77.37
  4996.6   76.37  5020.3   77.33  5101.1   87.17  5118.2   87.93  5157.9   88.44
  5174.6   88.07  5235.2   88.15  5250.5   88.54  5285.8   88.22  5341.4    89.2
  5463.4   88.01  5481.2   88.52  5508.1   88.37  5516.7   88.78  5583.9    89.5
  5720.4   89.09  5750.7    87.9    5781    88.2  5796.1   88.82  5811.3   88.73
  5841.7   89.19  5925.7   88.95  5948.3   88.01  5965.2   88.57  6117.1    89.3
#Mann= 4 ,-1 , 0
  4514.3     .14       0  4933.8     .04       0  5101.1     .14       0
  6117.1      .2       0
Bank Sta=4933.8,5101.1
XS Rating Curve= 0 ,0
Exp/Cntr=0.5,0.3

Type RM Length L Ch R = 1 ,51104.5 ,387,387,387
BEGIN DESCRIPTION:
Cross Section 51101.7
END DESCRIPTION:
XS GIS Cut Line= 4
     3135062.007    13930170.536      3134554.37     13930187.18
     3134305.494     13930195.34     3133459.885    13930216.802
#Sta/Elev= 30
  4514.3   89.09  4887.5   87.16  4909.6   86.56  4933.8   87.54  4978.6   77.37
  4996.6   76.37  5020.3   77.33  5101.1   87.17  5118.2   87.93  5157.9   88.44
  5174.6   88.07  5235.2   88.15  5250.5   88.54  5285.8   88.22  5341.4    89.2
  5463.4   88.01  5481.2   88.52  5508.1   88.37  5516.7   88.78  5583.9    89.5
  5720.4   89.09  5750.7    87.9    5781    88.2  5796.1   88.82  5811.3   88.73
  5841.7   89.19  5925.7   88.95  5948.3   88.01  5965.2   88.57  6117.1    89.3
#Mann= 4 ,-1 , 0
  4514.3     .14       0  4933.8     .04       0  5101.1     .14       0
  6117.1      .2       0
#XS Ineff= 2 , 0
       0    4928      90    5156       0      90
Permanent Ineff=
       F       F
Bank Sta=4933.8,5101.1
XS Rating Curve= 0 ,0
Exp/Cntr=0.5,0.3

Type RM Length L Ch R = 2 ,50911   ,,,
BEGIN DESCRIPTION:
4 - 8' x 6'
END DESCRIPTION:
Bridge Culvert--1,0,-1,-1, 0
Deck Dist Width WeirC Skew NumUp NumDn MinLoCord MaxHiCord MaxSubmerge Is_Ogee
10,367,2.5,0, 2, 2, , , 0.95, 0, 0,0,,
  4514.3  6117.1
   88.72   88.72
       0       0
  4469.7  7470.2
    88.5    88.5
       0       0
BR Coef=-1 , 0 , 0 ,, 0 ,,,0.8,-1,,0,
WSPro=,,,, 1 ,,,, 0 ,,,, 0 ,,,,-1 ,-1 ,-1 , 0 , 0 , 0 , 0 , 0
Multiple Barrel Culv=2,6,8,367,0.015,0.5,1,8,1,76.35,75.7, 4,Culvert #1  , 0 ,10
    4985    4979    4995    4989    5005    4999    5015    5009
BC Culvert Barrel=1,Barrel #1,0
BC Culvert Barrel=2,Barrel #2,0
BC Culvert Barrel=3,Barrel #3,0
BC Culvert Barrel=4,Barrel #4,0
Culvert Bottom n=0.015
BC Design=,, 0 ,, 0 ,,,,,,
BC HTab HWMax=89.5
BC Use User HTab Curves=0
BC User HTab FreeFlow(D)= 0

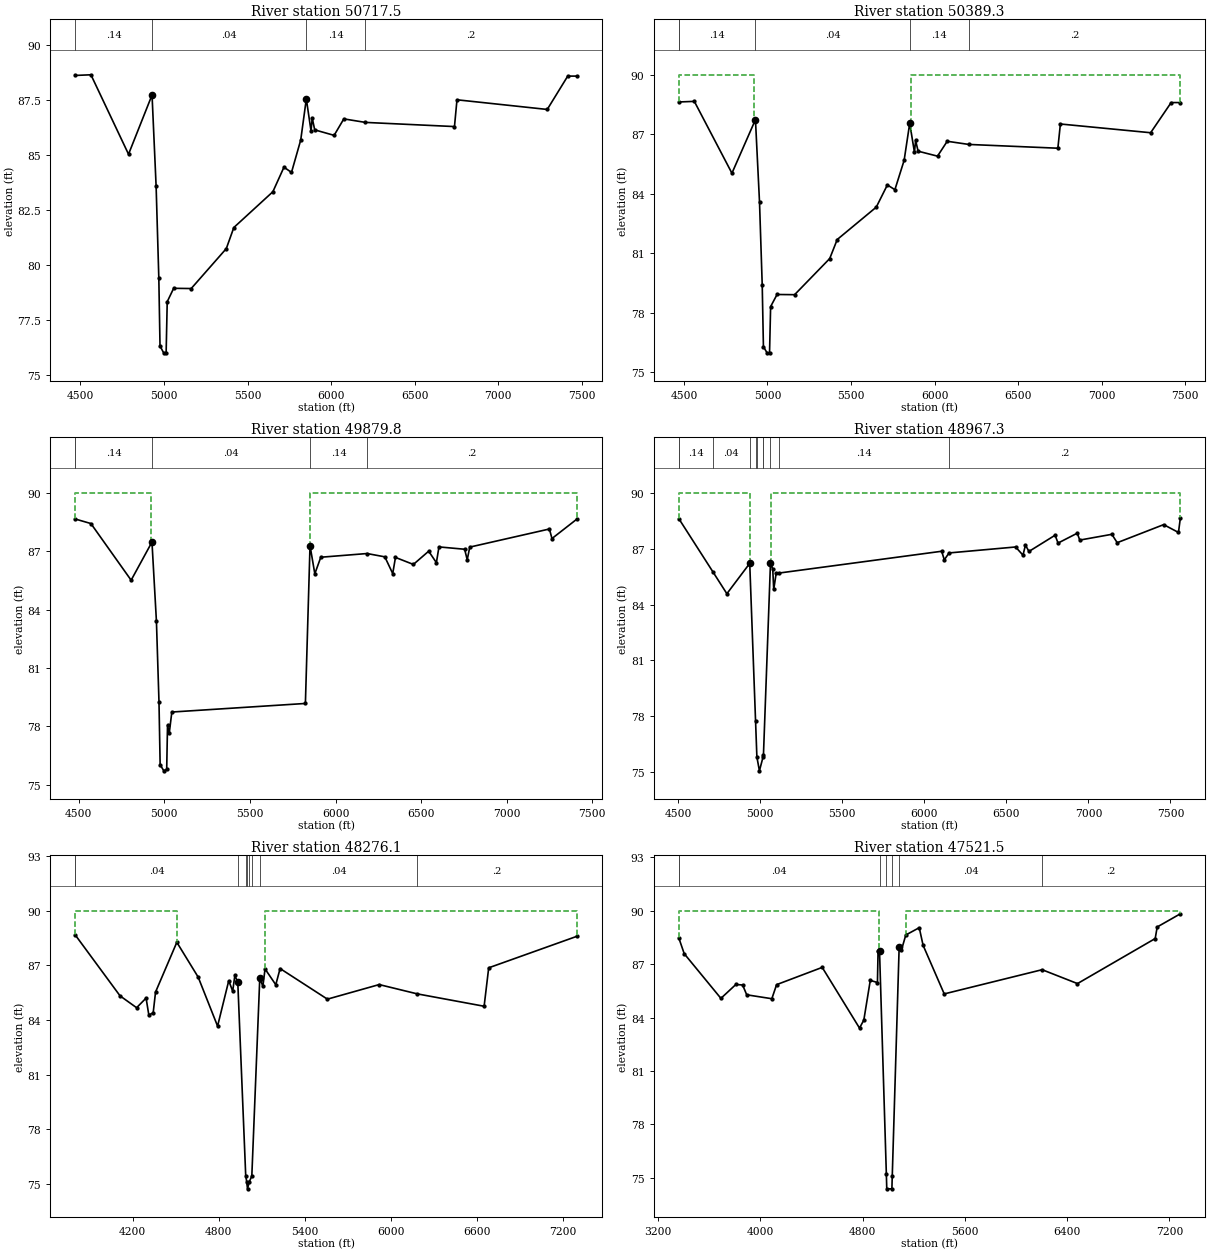
Type RM Length L Ch R = 1 ,50717.5 ,328.2,328.2,328.2
XS GIS Cut Line= 4
     3135121.656    13929819.056      3134193.04    13929791.623
     3133562.618    13929772.999     3132122.761    13929721.391
#Sta/Elev= 30
  4469.7   88.63  4562.4   88.66  4787.4   85.04  4928.1   87.74  4952.4   83.59
  4968.6   79.41  4975.8    76.3  4997.5   75.99  5012.4   75.99  5018.9   78.32
  5057.4   78.93  5162.4   78.92  5372.4   80.74  5417.4    81.7  5650.9   83.33
  5717.4   84.45  5762.4   84.21  5817.7   85.69  5851.1   87.56  5879.3    86.1
  5886.4   86.69  5901.3   86.15  6017.4    85.9  6075.5   86.65  6204.7   86.49
  6737.5    86.3  6752.5   87.52  7292.5   87.08  7415.2    88.6  7470.2    88.6
#Mann= 4 ,-1 , 0
  4469.7     .14       0  4928.1     .04       0  5851.1     .14       0
  6204.7      .2       0
Bank Sta=4928.1,5851.1
XS Rating Curve= 0 ,0
Exp/Cntr=0.5,0.3

Type RM Length L Ch R = 1 ,50389.3 ,509.5,509.5,509.5
BEGIN DESCRIPTION:
Cross Section 50389.3 - Interpolated
END DESCRIPTION:
XS GIS Cut Line= 3
      3135115.17     13929469.34      3134608.75     13929473.78
      3132114.81     13929500.42
#Sta/Elev= 30
  4469.7   88.63  4562.4   88.66  4787.4   85.04  4928.1   87.74  4952.4   83.59
  4968.6   79.41  4975.8    76.3  4997.5   75.99  5012.4   75.99  5018.9   78.32
  5057.4   78.93  5162.4   78.92  5372.4   80.74  5417.4    81.7  5650.9   83.33
  5717.4   84.45  5762.4   84.21  5817.7   85.69  5851.1   87.56  5879.3    86.1
  5886.4   86.69  5901.3   86.15  6017.4    85.9  6075.5   86.65  6204.7   86.49
  6737.5    86.3  6752.5   87.52  7292.5   87.08  7415.2    88.6  7470.2    88.6
#Mann= 5 , 1 , 0
  4469.7      .2       0  4469.7     .14       0  4928.1     .04       0
  5851.1     .14       0  6204.7      .2       0
#XS Ineff= 2 , 0
       0    4922      90    5860       0      90
Permanent Ineff=
       F       F
Bank Sta=4928.1,5851.1
XS Rating Curve= 0 ,0
Exp/Cntr=0.3,0.1

Type RM Length L Ch R = 1 ,49879.8 ,859.4,912.5,978.6
BEGIN DESCRIPTION:
Cross Section 49879.8
END DESCRIPTION:
XS GIS Cut Line= 5
      3135120.38     13928973.33      3134899.79     13928964.79
      3134586.19     13928964.79      3133685.98     13928964.79
      3132191.78     13928960.09
#Sta/Elev= 30
  4481.1   88.65  4571.4   88.42  4806.4   85.51  4928.1   87.47  4954.1   83.41
  4969.1   79.25  4975.8   76.03  4997.5   75.72  5014.1    75.8  5018.9   78.05
  5029.1   77.66  5044.1   78.74  5824.1   79.18  5851.1   87.29  5879.1   85.84
  5914.1   86.69  6184.3   86.88    6288   86.71  6334.1   85.85  6350.1   86.68
  6454.7   86.32  6544.1      87  6589.1   86.41  6604.1   87.22  6754.1    87.1
  6769.1   86.56  6784.1   87.21  7249.1   88.14  7264.1   87.65  7409.9   88.65
#Mann= 5 , 1 , 0
  4481.1      .2       0  4481.1     .14       0  4928.1     .04       0
  5851.1     .14       0  6184.3      .2       0
#XS Ineff= 2 , 0
       0    4924      90    5853       0      90
Permanent Ineff=
       F       F
Bank Sta=4928.1,5851.1
XS Rating Curve= 0 ,0
Exp/Cntr=0.3,0.1

Type RM Length L Ch R = 1 ,48967.3 ,406.5,691.2,615.7
BEGIN DESCRIPTION:
Cross Section 48967.3
END DESCRIPTION:
XS GIS Cut Line= 3
      3135119.86     13928077.59        3134593.     13928051.25
      3132071.04     13928220.54
#Sta/Elev= 30
  4504.9   88.61  4712.8   85.75  4797.6   84.58  4936.8   86.21 4972.33   77.74
 4980.37   75.82  4995.8   75.07  5018.2   75.82 5020.36   75.91  5063.2   86.23
    5077    85.9    5083   84.81  5098.1   85.69  5115.3   85.69    6106   86.86
  6122.1    86.4  6151.1   86.77  6556.3   87.09  6601.4   86.65  6616.5   87.19
  6637.8   86.85  6796.9   87.72  6815.1    87.3  6932.2   87.83  6947.2   87.46
  7142.7   87.77  7175.4   87.32  7458.4   88.29  7548.6   87.87    7560   88.64
#Mann= 11 ,-1 , 0
  4504.9      .2       0  4504.9     .14       0  4712.8     .04       0
  4936.8     .04       0 4972.33    .028       0 4980.37     .04       0
  5018.2    .028       0 5020.36     .04       0  5063.2     .04       0
  5115.3     .14       0  6151.1      .2       0
#XS Ineff= 2 , 0
       0    4936      90    5065       0      90
Permanent Ineff=
       F       F
Bank Sta=4936.8,5063.2
XS Rating Curve= 0 ,0
Exp/Cntr=0.3,0.1

Type RM Length L Ch R = 1 ,48276.1 ,381,754.6,717.8
BEGIN DESCRIPTION:
Cross Section 48276.1 - Interpolated
END DESCRIPTION:
XS GIS Cut Line= 5
      3135770.52     13927753.46      3134992.16     13927396.17
      3134608.75      13927357.9      3133731.26     13927375.34
      3132433.27     13927843.22
#Sta/Elev= 30
    3800   88.66  4111.4   85.33  4226.9   84.68    4293   85.21  4312.1   84.28
  4342.5    84.4    4359   85.54  4507.5   88.27  4656.4   86.36  4791.8   83.67
  4869.7   86.16  4897.3   85.59  4912.4   86.45  4932.8   86.08 4988.16   75.46
 4995.01   75.13  5000.6   74.74 5013.17   75.13 5030.72   75.44  5086.2   86.29
    5108   85.86    5123   86.81    5198   85.94    5228   86.83  5558.1   85.15
  5919.4   85.95  6184.9   85.44  6651.6   84.76  6683.5   86.87  7299.2    88.6
#Mann= 9 ,-1 , 0
    3800      .2       0    3800     .04       0  4932.8     .04       0
 4988.16    .028       0 4995.01     .04       0 5013.17    .028       0
 5030.72     .04       0  5086.2     .04       0  6184.9      .2       0
#XS Ineff= 2 , 0
       0    4510      90    5123       0      90
Permanent Ineff=
       F       F
Bank Sta=4932.8,5086.2
XS Rating Curve= 0 ,0
Exp/Cntr=0.3,0.1

Type RM Length L Ch R = 1 ,47521.5 ,112.8,205.8,684.8
BEGIN DESCRIPTION:
Cross Section 47521.5
END DESCRIPTION:
XS GIS Cut Line= 6
      3135859.84     13927689.66      3135008.79      13926737.8
       3134749.8     13926605.95      3134531.65     13926612.76
      3133353.79     13926678.48      3132433.27     13926937.64
#Sta/Elev= 30
  3363.4   88.47  3405.5   87.59  3692.4   85.08  3809.5   85.86  3862.3   85.83
  3894.2   85.28  4090.7   85.06  4127.9   85.85  4484.6   86.82  4776.3   83.41
    4810   83.86  4860.5   86.09  4916.5   85.97  4921.3   87.72  4932.8   87.73
 4986.17   75.21  4989.5   74.38  5029.5   74.38 5032.44   75.12  5086.2   87.94
  5103.6   87.78  5138.3   88.64  5243.4   89.05  5273.5   88.06  5438.7   85.33
  6204.2   86.69  6480.8   85.91  7088.5   88.44  7104.1   89.09  7285.1   89.83
#Mann= 7 ,-1 , 0
  3363.4      .2       0  3363.4     .04       0  4932.8     .04       0
 4986.17    .028       0 5032.44     .04       0  5086.2     .04       0
  6204.2      .2       0
#XS Ineff= 2 , 0
       0    4925      90    5137       0      90
Permanent Ineff=
       F       F
Bank Sta=4932.8,5086.2
XS Rating Curve= 0 ,0
Exp/Cntr=0.5,0.3

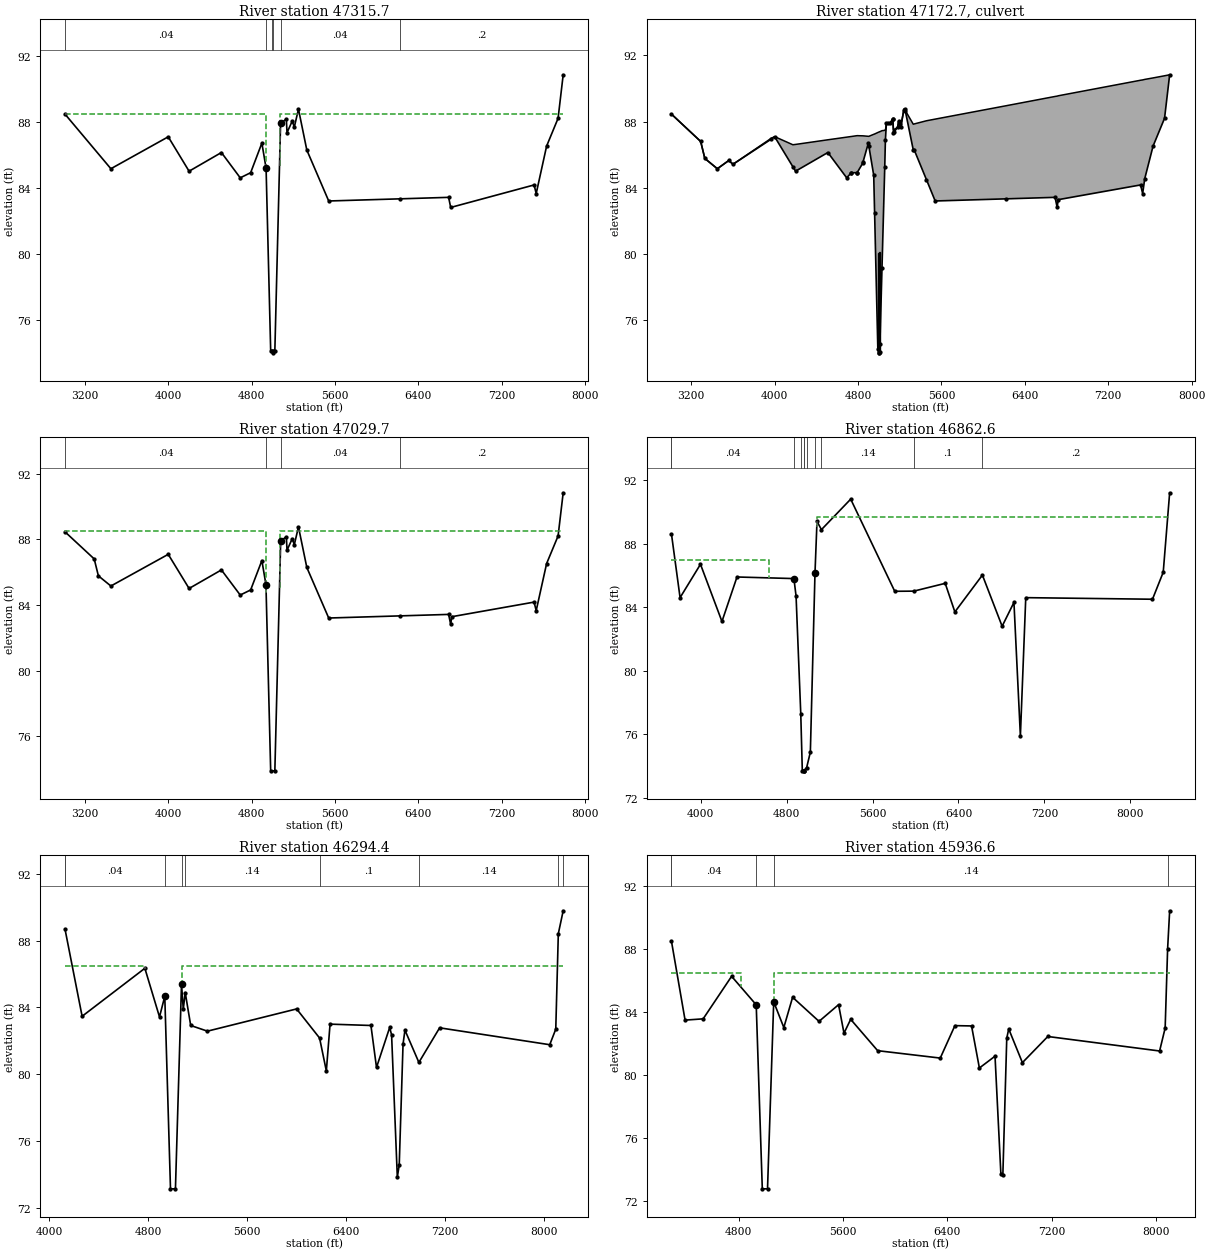
Type RM Length L Ch R = 1 ,47315.7 ,286,286,286
BEGIN DESCRIPTION:
Upstream Section of Bridge/Culvert/Weir
END DESCRIPTION:
XS GIS Cut Line= 5
     3136036.773    13927736.862     3135174.483    13926645.901
     3134975.883    13926415.272     3134501.803    13926396.052
     3131894.113    13926323.972
#Sta/Elev= 30
  3010.8   88.47  3450.8   85.17  4000.8    87.1  4200.8   85.02  4510.8   86.15
  4691.3   84.62  4791.2   84.93    4899   86.72 4939.28    85.2  4983.4   74.17
 4993.33   74.17  5001.8   74.04 5007.78   74.17  5023.4   74.17 5078.38   87.92
  5133.8   88.17    5140   87.35    5190   88.05    5210   87.69    5250   88.77
    5330    86.3    5540   83.22  6221.6   83.35    6690   83.44    6710   82.83
    7510   84.19    7530   83.67    7630   86.54    7740   88.22  7788.9   90.85
#Mann= 6 ,-1 , 0
  3010.8     .04       0 4939.28    .028       0 4993.33     .04       0
 5007.78    .028       0 5078.38     .04       0  6221.6      .2       0
#XS Ineff= 2 , 0
       0    4940    88.5    5068       0    88.5
Permanent Ineff=
       F       F
Bank Sta=4939.28,5078.38
XS Rating Curve= 0 ,0
Exp/Cntr=0.5,0.3

Type RM Length L Ch R = 2 ,47172.7 ,,,
BEGIN DESCRIPTION:
RUNWAY ACCESS ROAD
Structure ID: P30-24
END DESCRIPTION:
Bridge Culvert--1,0,-1,-1, 0
Deck Dist Width WeirC Skew NumUp NumDn MinLoCord MaxHiCord MaxSubmerge Is_Ogee
10,266,3,0, 58, 58, , , 0.95, 0, 1,1,,
  3010.8  3290.8  3330.8  3450.8  3560.8  3600.8    3970  4000.8    4175  4200.8
  4510.8  4691.3  4736.2  4737.1  4791.1  4791.2  4844.1  4846.7    4899  4903.8
  4950.4  4959.1  4989.9  4996.5  5001.8  5007.4    5010  5029.8  5056.4  5062.6
    5072    5083  5108.7  5133.7  5133.8    5140  5144.7    5180    5190  5199.7
    5210    5240    5250  5252.7    5330    5340  5456.2    5540  6221.6    6690
    6710    6720    7510    7530    7550    7630    7740  7788.9
   88.45    86.8   85.77   85.15   85.65   85.42      87   87.09    86.6   86.62
    86.9   87.06    87.1    87.1   87.15   87.15   87.14   87.14   87.11   87.11
   87.23   87.25   87.34   87.36   87.37   87.39   87.39   87.45   87.47   87.47
    87.9   87.91   87.93   88.16   88.16   87.51   87.51   87.66   88.04   87.87
   87.68   88.74   88.76   88.68   87.84   87.86   88.05   88.15   88.96   89.52
   89.54   89.56    90.5   90.52   90.55   90.64   90.77   90.83
   88.45    86.8   85.77   85.15   85.65   85.42   86.95   87.08   85.27      85
   86.13    84.6   84.91   84.91   84.91   84.91   85.47   85.53    86.7   86.52
   84.76   82.45   74.28   74.03   74.02   74.08   74.56   79.13   85.26   86.88
   87.89    87.9   87.92   88.15   88.15   87.33   87.37   87.65   88.03   87.86
   87.67   88.73   88.75   88.67   86.28   86.27   84.49    83.2   83.33   83.42
   82.81   83.28   84.17   83.65   84.55   86.52    88.2   90.83
  3010.8  3290.8  3330.8  3450.8  3560.8  3600.8    3970  4000.8    4175  4200.8
  4510.8  4691.3  4736.2  4737.1  4791.1  4791.2  4844.1  4846.7    4899  4903.8
  4950.4  4959.1  4989.9  4996.5  5001.8  5007.4    5010  5029.8  5056.4  5062.6
    5072    5083  5108.7  5133.7  5133.8    5140  5144.7    5180    5190  5199.7
    5210    5240    5250  5252.7    5330    5340  5456.2    5540  6221.6    6690
    6710    6720    7510    7530    7550    7630    7740  7788.9
   88.46   86.81   85.78   85.16   85.66   85.43      87   87.09    86.6   86.62
    86.9   87.06    87.1    87.1   87.15   87.15   87.14   87.14   87.11   87.11
   87.23   87.25   87.34   87.36   87.37   87.39   87.39   87.45   87.47   87.47
    87.9   87.91   87.93   88.16   88.16   87.51   87.51   87.66   88.04   87.87
   87.68   88.74   88.76   88.68   87.84   87.86   88.05   88.15   88.96   89.52
   89.54   89.56    90.5   90.52   90.55   90.64   90.77   90.84
   88.46   86.81   85.78   85.16   85.66   85.43   86.96   87.09   85.28   85.01
   86.14   84.61   84.92   84.92   84.92   84.92   85.48   85.54   86.71   86.53
   84.77   82.46   74.29   74.04   74.03   74.09   74.57   79.14   85.27   86.89
    87.9   87.91   87.93   88.16   88.16   87.34   87.38   87.66   88.04   87.87
   87.68   88.74   88.76   88.68   86.29   86.28    84.5   83.21   83.34   83.43
   82.82   83.29   84.18   83.66   84.56   86.53   88.21   90.84
BR Coef= 1 , 0 , 0 ,1.25, 0 ,,,0.8,-1,2,0,
WSPro=,,,, 1 ,,,, 0 ,,,, 0 ,,,,-1 ,-1 ,-1 , 0 , 0 , 0 , 0 , 0
Culvert=2,6,8,266,0.015,0.4,1,8,1,74.06,4999.8,73.87,4999.8,Culvert #2  , 0 ,10
  4999.8  4999.8
BC Culvert Barrel=1,,0
Culvert Bottom n=0.015
Culvert=2,6,8,266,0.015,0.4,1,8,1,74.13,5009.7,73.89,5009.7,Culvert #3  , 0 ,10
  5009.7  5009.7
BC Culvert Barrel=1,,0
Culvert Bottom n=0.015
BR U #Sta/Elev= 58
  3010.8   88.45  3290.8    86.8  3330.8   85.77  3450.8   85.15  3560.8   85.65
  3600.8   85.42    3970   86.95  4000.8   87.08    4175   85.27  4200.8      85
  4510.8   86.13  4691.3    84.6  4736.2   84.91  4737.1   84.91  4791.1   84.91
  4791.2   84.91  4844.1   85.47  4846.7   85.53    4899    86.7  4903.8   86.52
  4950.4   84.76  4959.1   82.45  4989.9   74.28  4996.5   74.03  5001.8   74.02
  5007.4   74.08    5010   74.56  5029.8   79.13  5056.4   85.26  5062.6   86.88
    5072   87.89    5083    87.9  5108.7   87.92  5133.7   88.15  5133.8   88.15
    5140   87.33  5144.7   87.37    5180   87.65    5190   88.03  5199.7   87.86
    5210   87.67    5240   88.73    5250   88.75  5252.7   88.67    5330   86.28
    5340   86.27  5456.2   84.49    5540    83.2  6221.6   83.33    6690   83.42
    6710   82.81    6720   83.28    7510   84.17    7530   83.65    7550   84.55
    7630   86.52    7740    88.2  7788.9   90.83
BR U #Mann= 4
  3010.8     .04  4950.4     .04  5056.4     .04  6221.6      .2
BR U Banks=4950.4,5056.4
BR D #Sta/Elev= 58
  3010.8   88.46  3290.8   86.81  3330.8   85.78  3450.8   85.16  3560.8   85.66
  3600.8   85.43    3970   86.96  4000.8   87.09    4175   85.28  4200.8   85.01
  4510.8   86.14  4691.3   84.61  4736.2   84.92  4737.1   84.92  4791.1   84.92
  4791.2   84.92  4844.1   85.48  4846.7   85.54    4899   86.71  4903.8   86.53
  4950.4   84.77  4959.1   82.46  4989.9   74.29  4996.5   74.04  5001.8   74.03
  5007.4   74.09    5010   74.57  5029.8   79.14  5056.4   85.27  5062.6   86.89
    5072    87.9    5083   87.91  5108.7   87.93  5133.7   88.16  5133.8   88.16
    5140   87.34  5144.7   87.38    5180   87.66    5190   88.04  5199.7   87.87
    5210   87.68    5240   88.74    5250   88.76  5252.7   88.68    5330   86.29
    5340   86.28  5456.2    84.5    5540   83.21  6221.6   83.34    6690   83.43
    6710   82.82    6720   83.29    7510   84.18    7530   83.66    7550   84.56
    7630   86.53    7740   88.21  7788.9   90.84
BR D #Mann= 4
  3010.8     .04  4950.4     .04  5056.4     .04  6221.6      .2
BR D Banks=4950.4,5056.4
BC Design=,, 0 ,, 0 ,,,,,,
BC HTab HWMax=90.85
BC Use User HTab Curves=0
BC User HTab FreeFlow(D)= 0

Type RM Length L Ch R = 1 ,47029.7 ,167.1,167.1,167.1
BEGIN DESCRIPTION:
Downstream Section of Bridge/Culvert/Weir
END DESCRIPTION:
XS GIS Cut Line= 6
     3136062.323     13927453.32     3135202.781    13926394.305
     3134986.135    13926203.919       3134841.7    13926125.244
     3134527.353      13926112.5     3131919.673     13926040.43
#Sta/Elev= 30
  3010.8   88.45  3290.8    86.8  3330.8   85.77  3450.8   85.15  4000.8   87.08
  4200.8      85  4510.8   86.13  4691.3    84.6  4791.2   84.91    4899    86.7
 4938.05   85.23  4983.4   73.89  5023.4   73.89 5079.43    87.9  5133.8   88.15
    5140   87.33    5190   88.03    5210   87.67    5250   88.75    5330   86.28
    5540    83.2  6221.6   83.33    6690   83.42    6710   82.81    6720   83.28
    7510   84.17    7530   83.65    7630   86.52    7740    88.2  7788.9   90.83
#Mann= 4 ,-1 , 0
  3010.8     .04       0 4938.05    .028       0 5079.43     .04       0
  6221.6      .2       0
#XS Ineff= 2 , 0
       0    4940    88.5    5068       0    88.5
Permanent Ineff=
       F       F
Bank Sta=4938.05,5079.43
XS Rating Curve= 0 ,0
Exp/Cntr=0.5,0.3

Type RM Length L Ch R = 1 ,46862.6 ,568.2,568.2,568.2
BEGIN DESCRIPTION:
Cross Section 46862.6 - Interpolated
END DESCRIPTION:
XS GIS Cut Line= 4
      3135680.77     13926770.35      3134706.61     13925947.93
      3134468.78     13925646.65      3133631.94     13922786.77
#Sta/Elev= 30
  3728.1    88.6  3808.1    84.6  3998.1    86.7  4198.1    83.1  4338.1    85.9
  4868.1    85.8  4888.1    84.7 4931.93   77.29  4946.2   73.72 4957.93   73.72
  4958.1    73.7  4960.1   73.72 4986.96   73.91  5021.2   74.88  5064.3   86.14
    5083    89.4  5124.4   88.88  5396.8    90.8  5806.8      85  5984.3   85.01
  6276.8    85.5  6366.8    83.7  6623.1   86.02  6806.8    82.8  6916.8    84.3
  6976.8    75.9  7026.8    84.6  8206.8    84.5  8306.8    86.2  8366.6    91.2
#Mann= 11 ,-1 , 0
  3728.1      .2       0  3728.1     .04       0  4868.1     .04       0
 4931.93    .028       0 4957.93     .04       0  4960.1    .028       0
 4986.96     .04       0  5064.3     .04       0  5124.4     .14       0
  5984.3      .1       0  6623.1      .2       0
#XS Ineff= 2 , 0
       0    4640      87    5081       0    89.7
Permanent Ineff=
       F       F
Bank Sta=4868.1,5064.3
XS Rating Curve= 0 ,0
Exp/Cntr=0.3,0.1

Type RM Length L Ch R = 1 ,46294.4 ,13.4,357.8,551.1
BEGIN DESCRIPTION:
Cross Section 46294.4 - Interpolated
END DESCRIPTION:
XS GIS Cut Line= 4
      3135675.72      13926745.1      3135276.13     13925973.49
      3135235.07     13924272.15      3135570.19     13922859.23
#Sta/Elev= 30
  4129.6   88.68  4267.7   83.47  4774.4   86.34  4892.7   83.43 4935.26   84.67
 4981.35   73.15 5021.35   73.15 5070.35    85.4  5084.6   83.89  5100.3   84.89
  5144.6   82.92  5279.6   82.58  5999.8   83.91  6185.3   82.17  6239.9    80.2
  6269.9      83    6600   82.92    6645   80.41  6751.4    82.8  6766.8   82.36
  6813.1   73.85  6828.5   74.57  6859.3   81.81  6874.7   82.64  6987.2   80.71
  7154.7   82.78  8043.9   81.77  8092.6    82.7  8113.2   88.41  8152.5   89.78
#Mann= 9 ,-1 , 0
  4129.6      .2       0  4129.6     .04       0 4935.26    .028       0
 5070.35     .04       0  5100.3     .14       0  6185.3      .1       0
  6987.2     .14       0  8113.2      .1       0  8152.5      .2       0
#XS Ineff= 2 , 0
       0    4775    86.5  5071.2       0    86.5
Permanent Ineff=
       F       F
Bank Sta=4935.26,5070.35
XS Rating Curve= 0 ,0
Exp/Cntr=0.3,0.1

Type RM Length L Ch R = 1 ,45936.6 ,10.9,48.7,10
BEGIN DESCRIPTION:
Cross Section 45936.6 - Interpolated
END DESCRIPTION:
XS GIS Cut Line= 6
      3135668.86     13926696.86      3135630.53     13926599.94
      3135634.17      13926495.7      3135633.49     13925989.83
      3135629.36     13925745.04      3135666.12     13922882.95
#Sta/Elev= 30
  4284.6    88.5  4388.9    83.5  4527.5   83.58  4745.9   86.28 4934.64   84.47
 4981.35   72.79 5021.35   72.79 5068.85   84.66  5146.4   83.03  5213.8   84.95
  5416.5   83.42  5566.5   84.48    5608   82.67  5659.3   83.55  5866.3   81.56
  6346.5   81.09  6458.8   83.15  6586.6   83.13  6646.6   80.46  6766.6   81.21
  6811.6   73.72  6826.6   73.66  6856.6   82.35  6871.6   82.94  6976.6    80.8
  7171.6   82.46  8029.1   81.54  8071.7      83  8090.6   88.03  8106.2   90.44
#Mann= 5 ,-1 , 0
  4284.6      .2       0  4284.6     .04       0 4934.64    .028       0
 5068.85     .14       0  8090.6      .1       0
#XS Ineff= 2 , 0
       0    4815    86.5  5070.6       0    86.5
Permanent Ineff=
       F       F
Bank Sta=4934.64,5068.85
XS Rating Curve= 0 ,0
Exp/Cntr=0.5,0.3