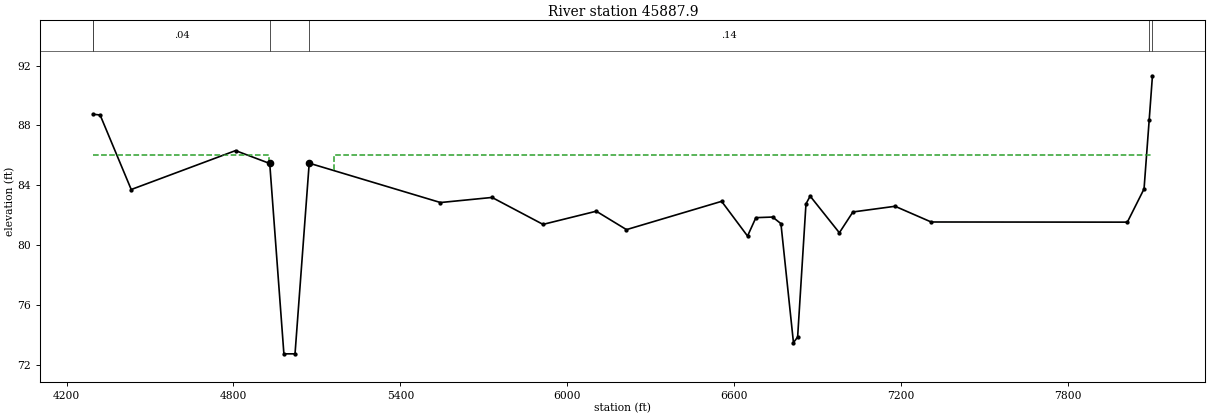
HEC-RAS study P130-00-00.prj: P130-00-00

--- P130-00-00.g01 (geometry) --- (continued)

Type RM Length L Ch R = 1 ,45887.9 ,58,58,58
BEGIN DESCRIPTION:
Upstream Section of Bridge/Culvert/Weir
END DESCRIPTION:
XS GIS Cut Line= 6
      3135675.36     13926697.62      3135675.36     13926289.77
      3135682.18     13925996.62      3135675.23     13925794.81
       3135716.4     13924153.15      3135720.06     13922890.74
#Sta/Elev= 30
  4295.5   88.75  4320.8    88.7  4432.6   83.72  4807.6   86.32 4930.46   85.46
 4981.35   72.74 5021.35   72.74 5072.33   85.48  5544.1   82.85  5729.5   83.19
  5912.7   81.39    6104   82.27  6212.7   81.04  6554.6   82.93  6647.8   80.61
  6677.8   81.84    6738   81.88  6767.8   81.44  6812.8   73.49  6827.8   73.86
  6857.8   82.76  6872.8   83.28  6977.8   80.83  7026.5   82.22    7178    82.6
  7307.8   81.55  8012.9   81.54  8072.9   83.76  8091.4   88.37  8103.1   91.32
#Mann= 6 ,-1 , 0
  4295.5      .2       0  4295.5     .04       0 4930.46    .028       0
 5072.33     .14       0  8091.4      .1       0  8103.1      .2       0
#XS Ineff= 2 , 0
       0  4927.5      86    5160       0      86
Permanent Ineff=
       F       F
Bank Sta=4930.46,5072.33
XS Rating Curve= 0 ,0
Exp/Cntr=0.5,0.3