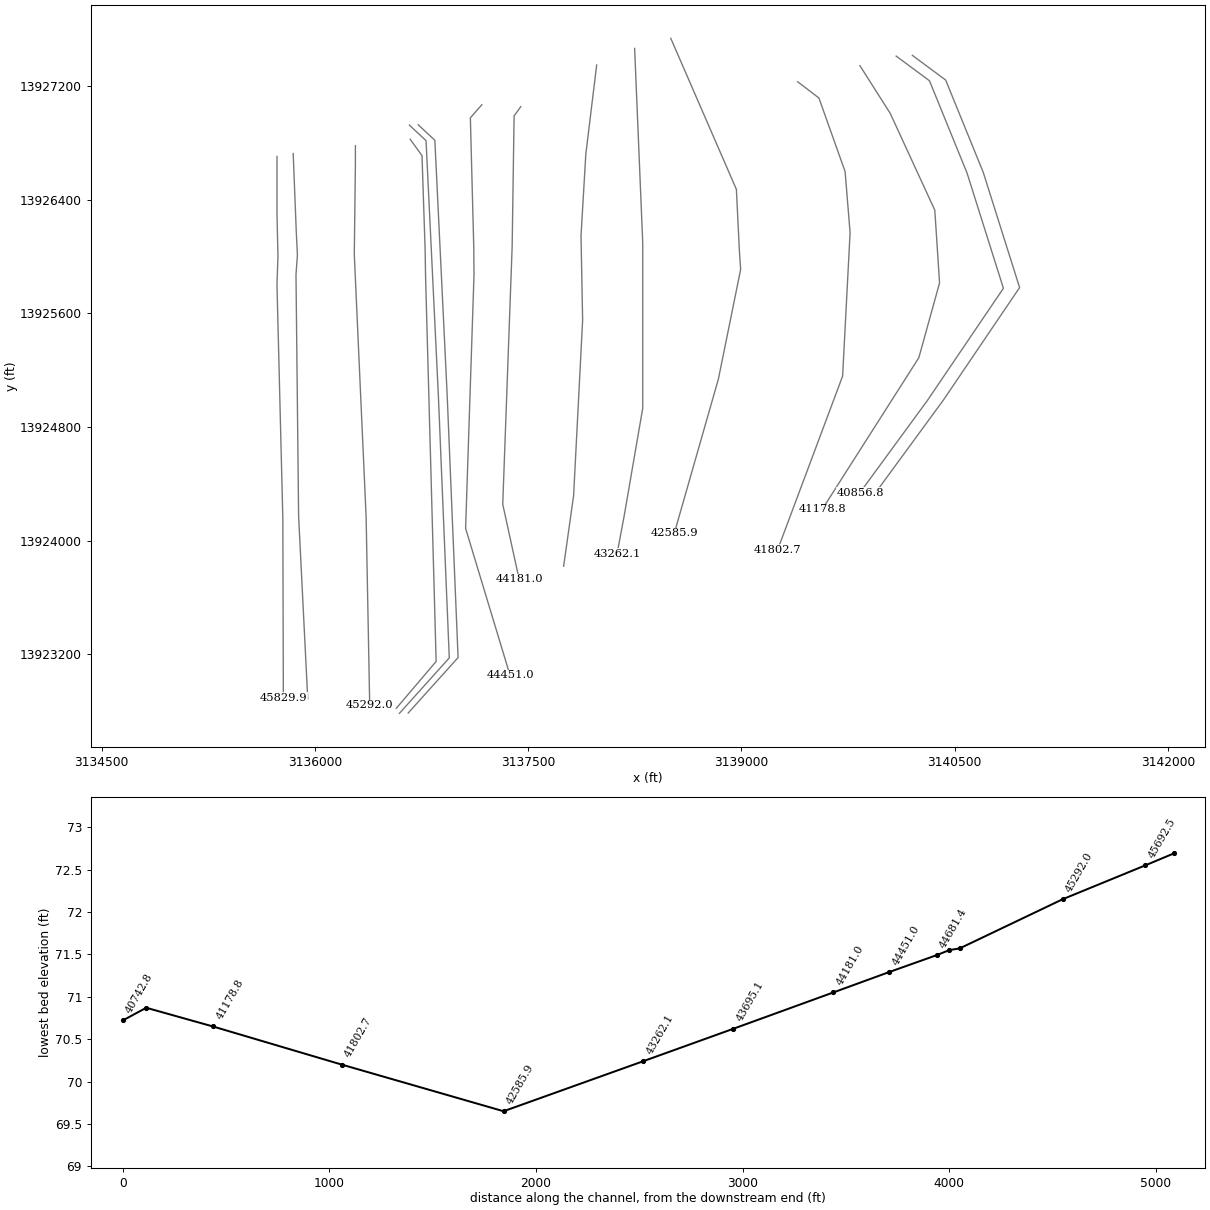
HEC-RAS study P130-00-00.prj: P130-00-00

--- P130-00-00.g01 (geometry) --- (continued)

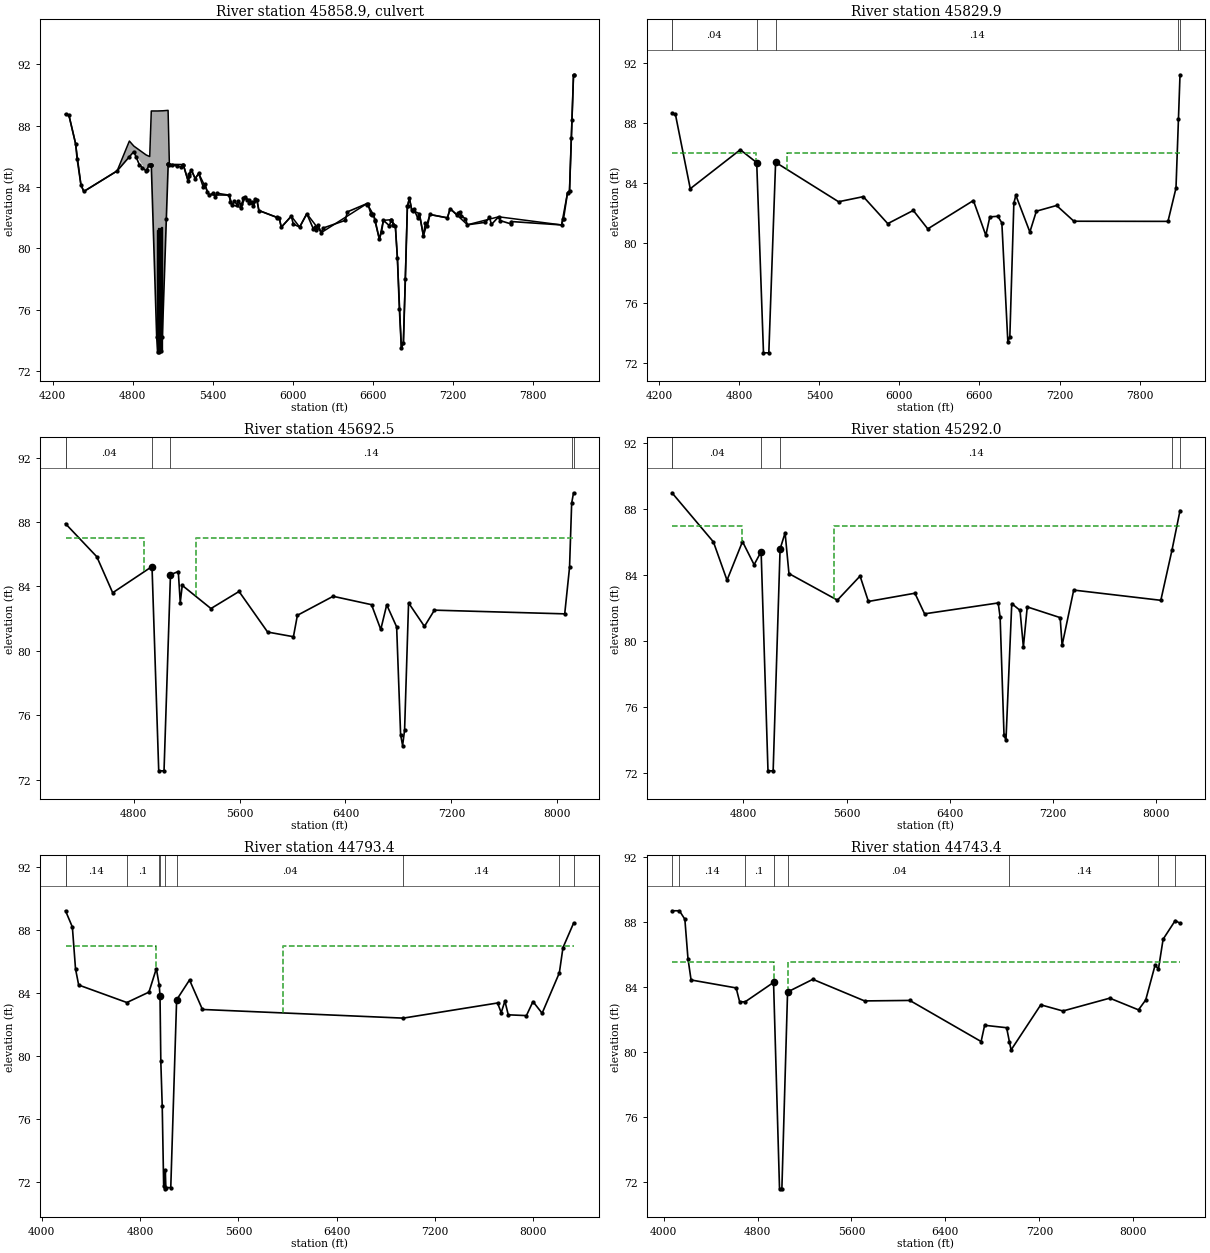
Type RM Length L Ch R = 2 ,45858.9 ,,,
BEGIN DESCRIPTION:
CULVERT 1/2 MILE WEST OF LEE ROAD
Structure ID: P30-23
END DESCRIPTION:
Bridge Culvert--1,0,-1,-1, 0
Deck Dist Width WeirC Skew NumUp NumDn MinLoCord MaxHiCord MaxSubmerge Is_Ogee
10,38,3,0, 60, 60, , , 0.95, 0, 1,1,,
  4295.5  4320.8  4371.1    4411  4432.6  4682.2  4774.1  4807.6  4900.3  4926.5
  4938.4  4978.9  4986.6  5014.3  5021.2  5064.3    5074    5178  5215.3  5237.6
  5267.6  5293.6  5372.6  5522.6  5544.1  5612.6  5642.6  5702.6  5729.5  5744.8
  5897.6  5912.7  5987.7  6050.4    6104  6212.7  6554.6  6602.8  6647.8  6677.8
    6738  6767.8  6782.8  6812.8  6827.8  6857.8  6872.8  6890.2  6947.8  6977.8
  7026.5  7157.8    7178  7307.8  7541.5  8012.9  8057.9  8072.9  8102.9  8103.1
   88.74   88.69   86.83   84.15   83.71   85.05      87   86.67   86.09   85.99
   88.96   88.96   88.96   88.97   88.97      89   85.48   85.47   84.38   85.13
   84.55   84.89   83.49   83.47   82.84   82.66   83.37   82.76   83.18   82.47
   81.97   81.38    82.1   81.39   82.26   81.03   82.92   82.21    80.6   81.83
   81.87   81.43    79.4   73.48   73.85   82.75   83.27   82.52   82.26   80.82
   82.21   81.99   82.59   81.54   82.06   81.53   83.63   83.75   91.32   91.31
   88.74   88.69   86.83   84.15   83.71   85.05   85.97   86.31   85.04   85.46
   85.44   74.23   73.26   73.34   74.23   85.49   85.47   85.46   84.37   85.13
   84.55   84.89   83.49   83.47   82.84   82.66   83.37   82.76   83.18   82.47
   81.97   81.38    82.1   81.39   82.26   81.03   82.92   82.21    80.6   81.83
   81.87   81.43    79.4   73.48   73.85   82.75   83.27   82.52   82.26   80.82
   82.21   81.99   82.59   81.54   82.06   81.53   83.63   83.75   91.32   91.31
  4295.5  4320.8  4371.1    4411  4432.6  4682.2  4774.1  4807.6  4900.3  4926.5
  4938.4  4978.9  4986.6  5014.3  5021.2  5064.3    5074    5178  5215.3  5237.6
  5267.6  5293.6  5372.6  5522.6  5544.1  5612.6  5642.6  5702.6  5729.5  5744.8
  5897.6  5912.7  5987.7  6050.4    6104  6212.7  6554.6  6602.8  6647.8  6677.8
    6738  6767.8  6782.8  6812.8  6827.8  6857.8  6872.8  6890.2  6947.8  6977.8
  7026.5  7157.8    7178  7307.8  7541.5  8012.9  8057.9  8072.9  8102.9  8103.1
   88.74   88.69   86.83   84.15   83.71   85.05      87   86.67   86.09   85.99
   88.96   88.96   88.96   88.97   88.97      89   85.48   85.47   84.38   85.13
   84.55   84.89   83.49   83.47   82.84   82.66   83.37   82.76   83.18   82.47
   81.97   81.38    82.1   81.39   82.26   81.03   82.92   82.21    80.6   81.83
   81.87   81.43    79.4   73.48   73.85   82.75   83.27   82.52   82.26   80.82
   82.21   81.99   82.59   81.54   82.06   81.53   83.63   83.75   91.32   91.31
   88.68   88.63   86.77   84.09   83.65   84.99   85.91   86.25   84.98    85.4
   85.38   74.17    73.2   73.28   74.17   85.43   85.41    85.4   84.31   85.07
   84.49   84.83   83.43   83.41   82.78    82.6   83.31    82.7   83.12   82.41
   81.91   81.32   82.04   81.33    82.2   80.97   82.86   82.15   80.54   81.77
   81.81   81.37   79.34   73.42   73.79   82.69   83.21   82.46    82.2   80.76
   82.15   81.93   82.53   81.48      82   81.47   83.57   83.69   91.26   91.25
BR Coef= 1 , 0 , 0 ,1.25, 0 ,,,0.8,-1,2,0,
WSPro=,,,, 1 ,,,, 0 ,,,, 0 ,,,,-1 ,-1 ,-1 , 0 , 0 , 0 , 0 , 0
Culvert=2,8,8,38,0.015,0.4,1,8,1,73.19,4985.4,73.12,4985.4,Culvert #1  , 0 ,10
  4985.4  4985.4
BC Culvert Barrel=1,,0
Culvert Bottom n=0.015
Culvert=2,8,8,38,0.015,0.4,1,8,1,73.36,4995.5,73.37,4995.5,Culvert #2  , 0 ,10
  4995.5  4995.5
BC Culvert Barrel=1,,0
Culvert Bottom n=0.015
Culvert=2,8,8,38,0.015,0.4,1,8,1,73.3,5006,73.25,5006,Culvert #3  , 0 ,10
    5006    5006
BC Culvert Barrel=1,,0
Culvert Bottom n=0.015
Culvert=2,8,8,38,0.015,0.4,1,8,1,73.4,5016.1,73.32,5016.1,Culvert #4  , 0 ,10
  5016.1  5016.1
BC Culvert Barrel=1,,0
Culvert Bottom n=0.015
BR U #Sta/Elev= 140
  4295.5   88.74  4320.8   88.69  4371.1   86.83  4382.3   85.85    4411   84.15
  4432.6   83.71  4682.2   85.05  4774.1   85.97  4807.6   86.31  4825.2   85.95
  4849.4   85.45  4871.5   85.27  4900.3   85.04  4905.5   85.14  4923.5   85.47
  4926.5   85.46  4937.7   85.44  4938.3   85.44  4938.4   85.44  4978.9   74.23
  4986.6   73.26    4998   73.26  5014.3   73.34  5021.2   74.23  5050.7   81.94
  5064.3   85.49  5064.6   85.49  5065.1   85.49    5074   85.47  5093.6   85.44
  5127.7   85.38  5162.8   85.32    5178   85.46  5178.6   85.44  5215.3   84.37
  5221.1   84.73  5223.1   84.86  5237.6   85.13  5267.6   84.55  5293.6   84.89
  5327.6   84.01  5342.6    84.2  5357.6   83.66  5372.6   83.49  5402.6   83.59
  5417.6   83.35  5432.6   83.59  5522.6   83.47  5530.8   83.02  5544.1   82.84
  5561.4   83.07  5582.6   82.85  5588.3   83.06  5607.2   82.88  5612.6   82.66
  5627.6    83.3  5642.6   83.37  5653.1   83.14  5668.4   83.18  5672.6   82.99
  5691.5   83.03  5702.6   82.76  5714.2   83.22  5729.5   83.18  5744.8   82.47
  5882.3   82.01  5882.7   82.02  5897.6   81.97  5912.7   81.38  5987.7    82.1
  6002.7   81.59  6050.4   81.39    6104   82.26  6152.7   81.28  6167.7   81.39
  6172.6   81.21  6187.9   81.52  6212.7   81.03  6227.7   81.33  6392.7   81.83
  6407.7   82.38  6554.6   82.92  6557.8   82.84  6560.8   82.91  6585.2   82.24
  6587.8   82.26  6590.3   82.18  6602.8   82.21  6615.8   81.88  6617.8   81.76
  6647.8    80.6  6663.9   81.07  6677.8   81.83  6722.7   81.48  6737.8   81.86
    6738   81.87  6752.8   81.55  6753.3   81.52  6767.8   81.43  6782.8    79.4
  6797.8   76.04  6812.8   73.48  6827.8   73.85  6842.8   78.02  6857.8   82.75
  6859.9   82.77  6872.8   83.27  6890.2   82.52  6902.8   82.45  6905.4   82.58
  6935.7   81.98  6947.8   82.26  6977.8   80.82  6992.8   81.65  7007.8   81.45
  7026.5   82.21  7157.8   81.99    7178   82.59  7232.8   82.16  7238.6   82.33
  7253.7   82.36  7262.8   82.12  7292.8   81.93  7307.8   81.54  7442.8    81.7
  7472.8   82.03  7487.8   81.56  7541.5   82.06    7554   81.81  7632.4    81.6
  7637.9   81.75  8012.9   81.53  8026.3   81.93  8027.9   81.93  8057.9   83.63
  8072.9   83.75  8086.8   87.18  8091.4   88.36  8102.9   91.32  8103.1   91.31
BR U #Mann= 6
  4295.5      .2  4295.5     .04  4938.4     .04  5064.3     .14  8091.4      .1
  8103.1      .2
BR U Banks=4938.4,5064.3
BR D #Sta/Elev= 140
  4295.5   88.68  4320.8   88.63  4371.1   86.77  4382.3   85.79    4411   84.09
  4432.6   83.65  4682.2   84.99  4774.1   85.91  4807.6   86.25  4825.2   85.89
  4849.4   85.39  4871.5   85.21  4900.3   84.98  4905.5   85.08  4923.5   85.41
  4926.5    85.4  4937.7   85.38  4938.3   85.38  4938.4   85.38  4978.9   74.17
  4986.6    73.2    4998    73.2  5014.3   73.28  5021.2   74.17  5050.7   81.88
  5064.3   85.43  5064.6   85.43  5065.1   85.43    5074   85.41  5093.6   85.38
  5127.7   85.32  5162.8   85.26    5178    85.4  5178.6   85.38  5215.3   84.31
  5221.1   84.67  5223.1    84.8  5237.6   85.07  5267.6   84.49  5293.6   84.83
  5327.6   83.95  5342.6   84.14  5357.6    83.6  5372.6   83.43  5402.6   83.53
  5417.6   83.29  5432.6   83.53  5522.6   83.41  5530.8   82.96  5544.1   82.78
  5561.4   83.01  5582.6   82.79  5588.3      83  5607.2   82.82  5612.6    82.6
  5627.6   83.24  5642.6   83.31  5653.1   83.08  5668.4   83.12  5672.6   82.93
  5691.5   82.97  5702.6    82.7  5714.2   83.16  5729.5   83.12  5744.8   82.41
  5882.3   81.95  5882.7   81.96  5897.6   81.91  5912.7   81.32  5987.7   82.04
  6002.7   81.53  6050.4   81.33    6104    82.2  6152.7   81.22  6167.7   81.33
  6172.6   81.15  6187.9   81.46  6212.7   80.97  6227.7   81.27  6392.7   81.77
  6407.7   82.32  6554.6   82.86  6557.8   82.78  6560.8   82.85  6585.2   82.18
  6587.8    82.2  6590.3   82.12  6602.8   82.15  6615.8   81.82  6617.8    81.7
  6647.8   80.54  6663.9   81.01  6677.8   81.77  6722.7   81.42  6737.8    81.8
    6738   81.81  6752.8   81.49  6753.3   81.46  6767.8   81.37  6782.8   79.34
  6797.8   75.98  6812.8   73.42  6827.8   73.79  6842.8   77.96  6857.8   82.69
  6859.9   82.71  6872.8   83.21  6890.2   82.46  6902.8   82.39  6905.4   82.52
  6935.7   81.92  6947.8    82.2  6977.8   80.76  6992.8   81.59  7007.8   81.39
  7026.5   82.15  7157.8   81.93    7178   82.53  7232.8    82.1  7238.6   82.27
  7253.7    82.3  7262.8   82.06  7292.8   81.87  7307.8   81.48  7442.8   81.64
  7472.8   81.97  7487.8    81.5  7541.5      82    7554   81.75  7632.4   81.54
  7637.9   81.69  8012.9   81.47  8026.3   81.87  8027.9   81.87  8057.9   83.57
  8072.9   83.69  8086.8   87.12  8091.4    88.3  8102.9   91.26  8103.1   91.25
BR D #Mann= 6
  4295.5      .2  4295.5     .04  4938.4     .04  5064.3     .14  8091.4      .1
  8103.1      .2
BR D Banks=4938.4,5064.3
BC Design=,, 0 ,, 0 ,,,,,,
BC HTab HWMax=91.33
BC Use User HTab Curves=0
BC User HTab FreeFlow(D)= 0

Type RM Length L Ch R = 1 ,45829.9 ,137.4,137.4,137.4
BEGIN DESCRIPTION:
Downstream Section of Bridge/Culvert/Weir
END DESCRIPTION:
XS GIS Cut Line= 6
      3135733.14     13926702.76      3135733.14     13926294.91
      3135739.96     13926001.76      3135733.01     13925799.95
      3135774.18     13924158.29      3135777.84     13922895.88
#Sta/Elev= 30
  4295.5   88.67  4320.8   88.62  4432.6   83.64  4807.6   86.24 4930.58   85.38
 4981.35   72.69 5021.35   72.69 5072.21    85.4  5544.1   82.77  5729.5   83.11
  5912.7   81.31    6104   82.19  6212.7   80.96  6554.6   82.85  6647.8   80.53
  6677.8   81.76    6738    81.8  6767.8   81.36  6812.8   73.41  6827.8   73.78
  6857.8   82.68  6872.8    83.2  6977.8   80.75  7026.5   82.14    7178   82.52
  7307.8   81.47  8012.9   81.46  8072.9   83.68  8091.4   88.29  8103.1   91.24
#Mann= 6 ,-1 , 0
  4295.5      .2       0  4295.5     .04       0 4930.58    .028       0
 5072.21     .14       0  8091.4      .1       0  8103.1      .2       0
#XS Ineff= 2 , 0
       0  4927.5      86    5160       0      86
Permanent Ineff=
       F       F
Bank Sta=4930.58,5072.21
XS Rating Curve= 0 ,0
Exp/Cntr=0.5,0.3

Type RM Length L Ch R = 1 ,45692.5 ,400.5,400.5,400.5
BEGIN DESCRIPTION:
Cross Section 45692.5 - Interpolated
END DESCRIPTION:
XS GIS Cut Line= 6
      3135847.09     13926723.74      3135868.56     13926177.23
      3135876.78     13926009.56      3135866.69     13925871.76
      3135885.17     13924173.04      3135949.41     13922887.31
#Sta/Elev= 30
  4284.5    87.9  4520.9   85.85    4641   83.61 4938.18   85.24 4988.95   72.55
 5028.95   72.55 5077.66   84.73  5136.7   84.93  5151.7      83  5166.7   84.07
  5383.6   82.63  5595.9   83.69  5811.8   81.17  6006.8   80.88  6036.8   82.21
  6306.8   83.39  6596.9   82.87  6666.8   81.33  6711.8   82.86  6786.8   81.49
  6816.8   74.79  6831.8   74.12  6846.8   75.08  6876.9   82.98    6997   81.52
  7072.1   82.53  8056.9    82.3  8093.4   85.19  8109.3   89.17  8123.6   89.82
#Mann= 6 ,-1 , 0
  4284.5      .2       0  4284.5     .04       0 4938.18    .028       0
 5077.66     .14       0  8109.3      .1       0  8123.6      .2       0
#XS Ineff= 2 , 0
       0    4880      87    5270       0      87
Permanent Ineff=
       F       F
Bank Sta=4938.18,5077.66
XS Rating Curve= 0 ,0
Exp/Cntr=0.3,0.1

Type RM Length L Ch R = 1 ,45292.0 ,483.8,498.6,558.8
BEGIN DESCRIPTION:
Cross Section 45292.0 - Interpolated
END DESCRIPTION:
XS GIS Cut Line= 5
       3136284.7     13926779.06      3136284.44     13926634.61
      3136276.79     13926014.62      3136359.96      13924168.9
      3136385.25     13922843.72
#Sta/Elev= 30
  4245.7   89.01    4567   86.03  4672.3   83.71  4792.3   86.05  4882.3   84.65
  4936.7   85.44 4989.85   72.15 5029.85   72.15 5083.67    85.6  5122.4   86.58
  5152.4   84.11  5527.8    82.5  5703.5   83.96  5768.1   82.42  6128.4   82.92
  6203.5   81.67  6774.1   82.33  6789.1   81.46  6819.1   74.33  6834.2      74
  6879.2   82.29  6943.3   81.88  6969.2   79.66  6999.2   82.09  7254.3   81.44
  7269.3   79.76  7359.3   83.11  8034.4   82.49  8120.6   85.52  8183.2   87.93
#Mann= 6 ,-1 , 0
  4245.7      .2       0  4245.7     .04       0  4936.7    .028       0
 5083.67     .14       0  8120.6      .1       0  8183.2      .2       0
#XS Ineff= 2 , 0
       0    4792      87    5505       0      87
Permanent Ineff=
       F       F
Bank Sta=4936.7,5083.67
XS Rating Curve= 0 ,0
Exp/Cntr=0.3,0.1

Type RM Length L Ch R = 1 ,44793.4 ,18.3,50,26.8
BEGIN DESCRIPTION:
Cross Section 44793.4 - Interpolated
END DESCRIPTION:
XS GIS Cut Line= 6
      3136669.81     13926824.13      3136753.07     13926708.86
      3136775.04     13926046.33      3136778.07     13925860.48
      3136852.43     13923151.15      3136572.66     13922821.93
#Sta/Elev= 30
  4193.3   89.21  4249.1   88.18  4274.8   85.52  4300.4    84.5  4692.5   83.39
  4872.2   84.05  4932.2   85.54  4955.8   84.49  4962.2   83.81 4968.78   79.65
 4980.28    76.8 4991.88   71.75 5000.38   71.57 5005.31   72.75  5009.7   71.65
  5049.7   71.65 5097.35   83.56  5202.3   84.82  5307.3   82.95  6941.1    82.4
  7708.2   83.36  7738.2   82.75  7768.2   83.48  7795.5   82.61  7943.3   82.56
  7996.5   83.45    8071   82.71  8211.1   85.27  8240.6   86.87  8326.7   88.42
#Mann= 10 ,-1 , 0
  4193.3      .2       0  4193.3     .14       0  4692.5      .1       0
  4955.8     .04       0  4962.2     .04       0 5005.31    .028       0
 5097.35     .04       0  6941.1     .14       0  8211.1      .1       0
  8326.7      .2       0
#XS Ineff= 2 , 0
       0    4930      87    5960       0      87
Permanent Ineff=
       F       F
Bank Sta=4962.2,5097.35
XS Rating Curve= 0 ,0
Exp/Cntr=0.5,0.3

Type RM Length L Ch R = 1 ,44743.4 ,62,62,62
BEGIN DESCRIPTION:
Upstream Section of Bridge/Culvert/Weir
END DESCRIPTION:
XS GIS Cut Line= 5
      3136664.46     13926923.27      3136781.45     13926814.22
      3136867.95     13925025.24       3136944.9     13923175.89
      3136593.98     13922785.83
#Sta/Elev= 30
  4071.4   88.67  4134.6   88.67  4181.1   88.15  4207.6   85.73  4234.1   84.41
  4617.7   83.92  4647.7   83.07  4693.8   83.06  4936.5   84.26 4987.35   71.55
 5007.35   71.55 5055.83   83.67    5271   84.45  5711.7   83.12  6096.7   83.15
  6704.1   80.62  6734.1   81.62  6921.2   81.47  6945.6   80.59  6959.3    80.1
  7212.2   82.88  7400.8    82.5  7799.8   83.29  8044.5   82.57  8105.9   83.18
  8185.6   85.32  8214.4   85.09  8254.1   86.92  8357.5   88.07    8398    87.9
#Mann= 8 ,-1 , 0
  4071.4      .2       0  4134.6     .14       0  4693.8      .1       0
  4936.5    .013       0 5055.83     .04       0  6945.6     .14       0
  8214.4      .1       0  8357.5      .2       0
#XS Ineff= 2 , 0
       0    4937    85.5 5055.83       0    85.5
Permanent Ineff=
       F       F
Bank Sta=4936.5,5055.83
XS Rating Curve= 0 ,0
Exp/Cntr=0.5,0.3

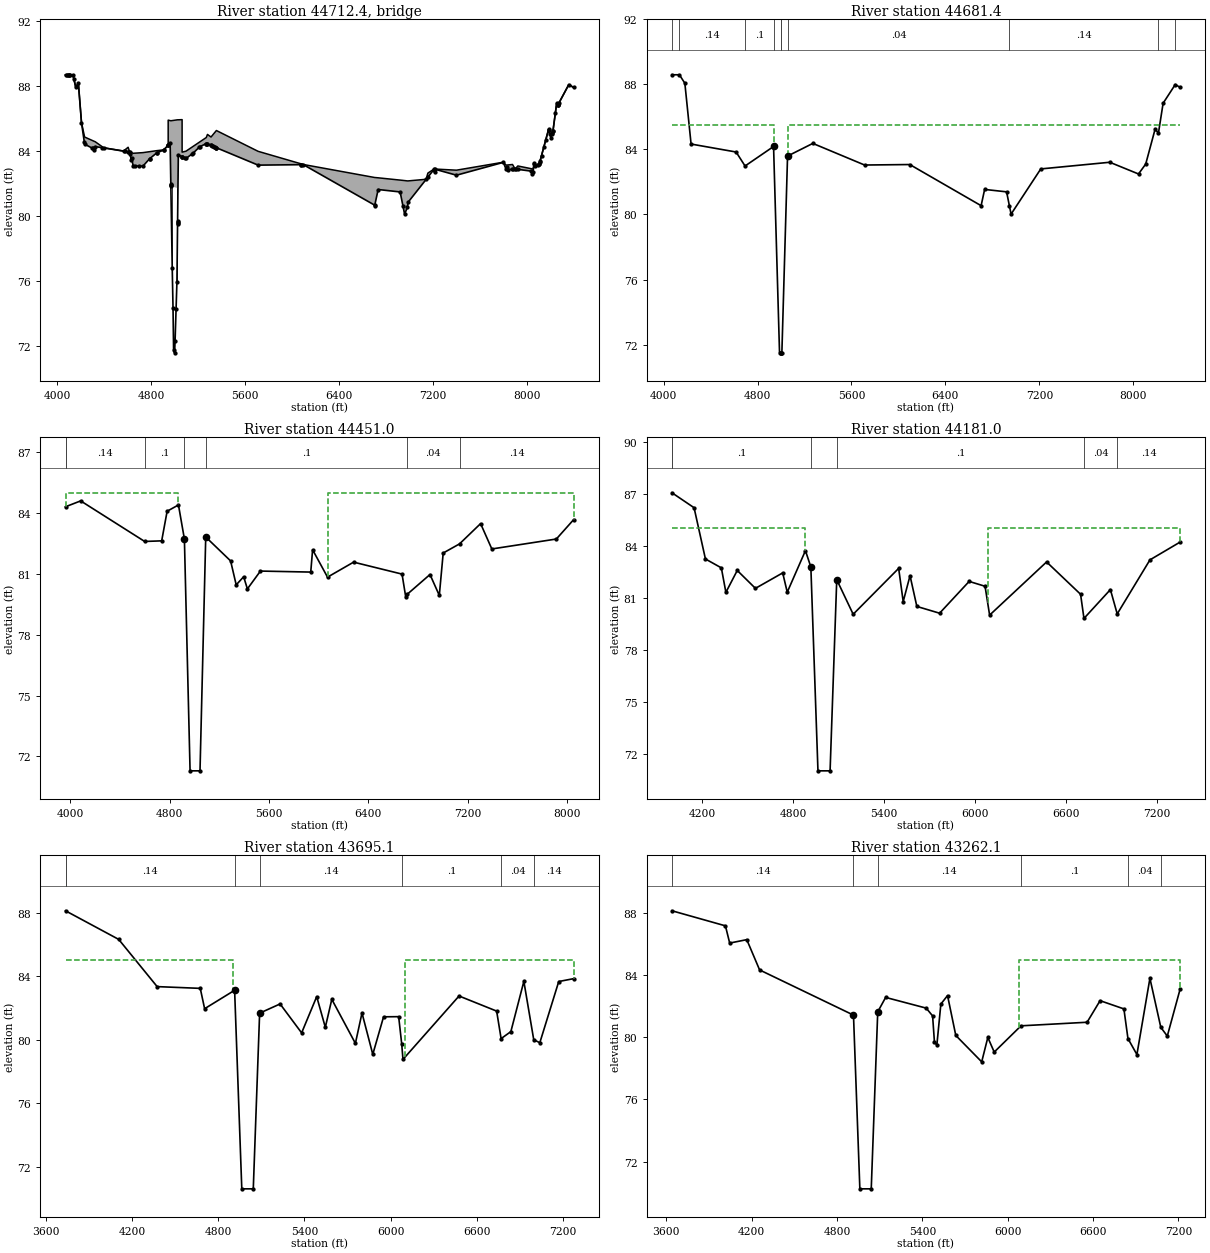
Type RM Length L Ch R = 3 ,44712.4 ,,,
BEGIN DESCRIPTION:
LEE ROAD
Structure ID: P30-22
END DESCRIPTION:
Bridge Culvert--1,0,-1,-1, 0
Deck Dist Width WeirC Skew NumUp NumDn MinLoCord MaxHiCord MaxSubmerge Is_Ogee
10,42,2.6,0, 60, 60, , , 0.95, 0, 1,1,,
  4071.4  4134.6    4158  4181.1  4207.6  4234.1  4317.6  4324.5  4396.6  4565.8
  4604.7  4617.7  4647.7  4731.1  4847.9  4907.6 4945.69  4945.8  4962.5  4968.6
 5025.79  5025.9  5032.2  5064.4 5064.51  5097.8  5270.3  5280.5  5310.6  5356.3
  5711.7  6096.7  6704.1  6734.1  6921.2  6959.3  6983.4  6989.3  7142.4  7157.4
  7212.2  7214.4  7216.8  7400.8  7799.8  7823.4  7878.4  7900.8  7923.3  8052.3
  8064.7  8073.5  8105.9  8185.6  8205.7  8222.3  8254.1  8264.7  8357.5    8398
   88.67   88.68   87.94   88.16   85.74   84.85   84.58   84.56   84.19   83.99
   84.22   83.93   83.85   83.89   84.01   84.06   84.34   85.89   85.86   85.85
   85.91   85.91   85.91   85.92   83.92   83.98   84.82   85.01   84.85   85.25
   83.97   83.16   82.36   82.34    82.2   82.17   82.15   82.15   82.25   82.63
   82.89   82.67   82.88   82.81    83.3   83.12   83.16   82.88   83.07   82.88
   83.24   83.06   83.19   85.33   84.82    85.2   86.93   86.83   88.08    87.9
   88.67   88.67   87.93   88.15   85.73   84.41   84.05   84.26   84.18   83.98
   83.94   83.92   83.07   83.06   83.87   84.05   84.33   84.34   84.46   81.83
   81.71   79.62   83.75   83.64   83.64   83.53   84.45   84.42   84.33   84.19
   83.12   83.15   80.62   81.62   81.47    80.1   80.53   80.84   82.24   82.38
   82.88   82.67   82.87    82.5   83.29   82.87   82.86   82.87   82.86   82.69
   83.23   83.05   83.18   85.32   84.81   85.19   86.92   86.82   88.07    87.9
  4071.4  4134.6    4158  4181.1  4207.6  4234.1  4317.6  4324.5  4396.6  4565.8
  4604.7  4617.7  4647.7  4731.1  4847.9  4907.6 4945.69  4945.8  4962.5  4968.6
 5025.79  5025.9  5032.2  5064.4 5064.51  5097.8  5270.3  5280.5  5310.6  5356.3
  5711.7  6096.7  6704.1  6734.1  6921.2  6959.3  6983.4  6989.3  7142.4  7157.4
  7212.2  7214.4  7216.8  7400.8  7799.8  7823.4  7878.4  7900.8  7923.3  8052.3
  8064.7  8073.5  8105.9  8185.6  8205.7  8222.3  8254.1  8264.7  8357.5    8398
   88.67   88.68   87.94   88.16   85.74   84.85   84.58   84.56   84.19   83.99
   84.22   83.93   83.85   83.89   84.01   84.06   84.34   85.89   85.86   85.85
   85.91   85.91   85.91   85.92   83.92   83.98   84.82   85.01   84.85   85.25
   83.97   83.16   82.36   82.34    82.2   82.17   82.15   82.15   82.25   82.63
   82.89   82.67   82.88   82.81    83.3   83.12   83.16   82.88   83.07   82.88
   83.24   83.06   83.19   85.33   84.82    85.2   86.93   86.83   88.08    87.9
    88.6    88.6   87.86   88.08   85.66   84.34   83.98   84.19   84.11   83.91
   83.87   83.85      83   82.99    83.8   83.98   84.26   84.27   84.39   81.76
   81.64   79.55   83.68   83.57   83.57   83.46   84.38   84.35   84.26   84.12
   83.05   83.08   80.55   81.55    81.4   80.03   80.46   80.77   82.17   82.31
   82.81    82.6    82.8   82.43   83.22    82.8   82.79    82.8   82.79   82.62
   83.16   82.98   83.11   85.25   84.74   85.12   86.85   86.75      88   87.83
Pier Skew, UpSta & Num, DnSta & Num=  ,4980.3, 2 ,4980.3, 2 , 0 , 0 , 0 ,,
     1.4     1.4
   75.54   82.67
     1.4     1.4
   75.47    82.6
Pier Skew, UpSta & Num, DnSta & Num=  ,5020.3, 2 ,5020.3, 2 , 0 , 0 , 0 ,,
     1.4     1.4
   74.78    82.7
     1.4     1.4
   74.71   82.63
BR Coef= 1 , 1 , 0 ,1.25, 0 ,,,0.8,0,2,0,
WSPro=,,,, 1 ,,,, 0 ,,,, 0 ,,,,-1 ,-1 ,-1 , 0 , 0 , 0 , 0 , 0
BR U #Sta/Elev= 136
  4071.4   88.67  4081.1   88.67  4088.4   88.67    4099   88.67  4101.6   88.67
  4109.7   88.67  4134.6   88.67  4142.6   88.42    4158   87.93  4181.1   88.15
  4207.6   85.73  4231.3   84.55  4234.1   84.41  4297.9   84.17  4302.5   84.19
  4317.6   84.05  4324.5   84.26  4379.5    84.2  4396.6   84.18  4565.8   83.98
  4574.7   83.97  4604.7   83.94  4611.5   83.93  4617.7   83.92  4618.8   83.83
  4632.7   83.46  4634.3   83.55  4647.7   83.07  4664.8   83.07  4693.8   83.06
  4731.1   83.06  4786.8   83.51    4787   83.51  4847.9   83.87  4853.4   83.89
  4907.6   84.05    4911   84.08 4945.69   84.33  4945.8   84.34 4945.91   84.34
  4962.5   84.46  4968.3   81.96 4968.41   81.92  4968.5   81.88  4968.6   81.83
  4980.3    76.8    4987   74.33  4991.9   71.75  5000.4   71.57  5004.5    72.3
  5013.1   74.26  5020.3   75.94  5025.7   79.48 5025.79   79.54  5025.9   79.62
    5026   79.68  5032.2   83.75 5064.29   83.64  5064.4   83.64 5064.51   83.64
  5085.1   83.57  5097.8   83.53  5144.7   83.79  5158.4   83.86  5209.9   84.22
  5214.4   84.25  5270.3   84.45    5271   84.45  5275.9   84.44  5280.5   84.42
  5307.5   84.34  5310.6   84.33  5323.2   84.29  5325.6   84.29    5339   84.24
  5340.6   84.24  5354.8    84.2  5355.6   84.19  5356.3   84.19  5711.7   83.12
  6076.4   83.15  6080.3   83.15  6096.7   83.15  6703.5   80.66  6704.1   80.62
  6734.1   81.62  6921.2   81.47  6945.6   80.59  6959.3    80.1  6983.4   80.53
  6989.3   80.84  7142.4   82.24  7157.4   82.38  7212.2   82.88  7214.4   82.67
  7216.8   82.87  7400.8    82.5  7799.8   83.29  7823.4   82.87  7829.8   82.99
  7835.8   82.85  7873.4   82.86  7878.4   82.86  7900.8   82.87  7908.8   82.87
  7923.3   82.86  8038.5   82.75  8044.5   82.57  8052.3   82.69  8062.9    83.2
  8064.7   83.23  8073.5   83.05  8094.9   83.15  8102.7   83.17  8105.9   83.18
  8111.6   83.33  8112.7   83.36  8125.1    83.7  8144.6   84.22  8162.1   84.69
  8185.6   85.32    8187   85.28  8197.7   85.01  8205.7   84.81  8211.6   85.06
  8214.4   85.09  8222.3   85.19  8222.6   85.21  8242.8   86.31  8254.1   86.92
  8261.4   86.85  8262.9   86.84  8264.7   86.82    8272   86.92  8357.5   88.07
    8398    87.9
BR U #Mann= 8
  4071.4      .2  4134.6     .14  4693.8      .1  4962.5     .04  5032.2     .04
  6945.6     .14  8214.4      .1  8357.5      .2
BR U Banks=4962.5,5032.2
BR D #Sta/Elev= 136
  4071.4    88.6  4081.1    88.6  4088.4    88.6    4099    88.6  4101.6    88.6
  4109.7    88.6  4134.6    88.6  4142.6   88.35    4158   87.86  4181.1   88.08
  4207.6   85.66  4231.3   84.48  4234.1   84.34  4297.9    84.1  4302.5   84.12
  4317.6   83.98  4324.5   84.19  4379.5   84.13  4396.6   84.11  4565.8   83.91
  4574.7    83.9  4604.7   83.87  4611.5   83.86  4617.7   83.85  4618.8   83.76
  4632.7   83.39  4634.3   83.48  4647.7      83  4664.8      83  4693.8   82.99
  4731.1   82.99  4786.8   83.44    4787   83.44  4847.9    83.8  4853.4   83.82
  4907.6   83.98    4911   84.01 4945.69   84.26  4945.8   84.27 4945.91   84.27
  4962.5   84.39  4968.3   81.89 4968.41   81.85  4968.5   81.81  4968.6   81.76
  4980.3   76.73    4987   74.26  4991.9   71.68  5000.4    71.5  5004.5   72.23
  5013.1   74.19  5020.3   75.87  5025.7   79.41 5025.79   79.47  5025.9   79.55
    5026   79.61  5032.2   83.68 5064.29   83.57  5064.4   83.57 5064.51   83.57
  5085.1    83.5  5097.8   83.46  5144.7   83.72  5158.4   83.79  5209.9   84.15
  5214.4   84.18  5270.3   84.38    5271   84.38  5275.9   84.37  5280.5   84.35
  5307.5   84.27  5310.6   84.26  5323.2   84.22  5325.6   84.22    5339   84.17
  5340.6   84.17  5354.8   84.13  5355.6   84.12  5356.3   84.12  5711.7   83.05
  6076.4   83.08  6080.3   83.08  6096.7   83.08  6703.5   80.59  6704.1   80.55
  6734.1   81.55  6921.2    81.4  6945.6   80.52  6959.3   80.03  6983.4   80.46
  6989.3   80.77  7142.4   82.17  7157.4   82.31  7212.2   82.81  7214.4    82.6
  7216.8    82.8  7400.8   82.43  7799.8   83.22  7823.4    82.8  7829.8   82.92
  7835.8   82.78  7873.4   82.79  7878.4   82.79  7900.8    82.8  7908.8    82.8
  7923.3   82.79  8038.5   82.68  8044.5    82.5  8052.3   82.62  8062.9   83.13
  8064.7   83.16  8073.5   82.98  8094.9   83.08  8102.7    83.1  8105.9   83.11
  8111.6   83.26  8112.7   83.29  8125.1   83.63  8144.6   84.15  8162.1   84.62
  8185.6   85.25    8187   85.21  8197.7   84.94  8205.7   84.74  8211.6   84.99
  8214.4   85.02  8222.3   85.12  8222.6   85.14  8242.8   86.24  8254.1   86.85
  8261.4   86.78  8262.9   86.77  8264.7   86.75    8272   86.85  8357.5      88
    8398   87.83
BR D #Mann= 8
  4071.4      .2  4134.6     .14  4693.8      .1  4962.5     .04  5032.2     .04
  6945.6     .14  8214.4      .1  8357.5      .2
BR D Banks=4962.5,5032.2
BC Design=,, 0 ,, 0 ,,,,,,
BC HTab HWMax=88.67
BC Use User HTab Curves=0
BC User HTab FreeFlow(D)= 0

Type RM Length L Ch R = 1 ,44681.4 ,230.4,230.4,230.4
BEGIN DESCRIPTION:
Downstream Section of Bridge/Culvert/Weir
END DESCRIPTION:
XS GIS Cut Line= 5
      3136726.42     13926925.75      3136843.41      13926816.7
      3136929.91     13925027.72      3137006.86     13923178.37
      3136655.94     13922788.31
#Sta/Elev= 30
  4071.4   88.59  4134.6   88.59  4181.1   88.07  4234.1   84.33  4617.7   83.84
  4693.8   82.98 4936.61   84.18 4987.35    71.5 4999.93    71.5  5000.4   71.49
 5000.46    71.5 5007.35    71.5 5055.71   83.59    5271   84.37  5711.7   83.04
  6096.7   83.07  6704.1   80.54  6734.1   81.54  6921.2   81.39  6945.6   80.51
  6959.3   80.02  7212.2    82.8  7799.8   83.21  8044.5   82.49  8105.9    83.1
  8185.6   85.24  8214.4   85.01  8254.1   86.84  8357.5   87.99    8398   87.82
#Mann= 10 ,-1 , 0
  4071.4      .2       0  4134.6     .14       0  4693.8      .1       0
 4936.61    .013       0 4999.93     .04       0 5000.46    .013       0
 5055.71     .04       0  6945.6     .14       0  8214.4      .1       0
  8357.5      .2       0
#XS Ineff= 2 , 0
       0    4938    85.5 5055.71       0    85.5
Permanent Ineff=
       F       F
Bank Sta=4936.61,5055.71
XS Rating Curve= 0 ,0
Exp/Cntr=0.5,0.3

Type RM Length L Ch R = 1 ,44451.0 ,321.8,270,259.9
BEGIN DESCRIPTION:
Cross Section 44451.0 - Interpolated
END DESCRIPTION:
XS GIS Cut Line= 6
      3137173.83      13927066.6      3137093.19     13926974.89
       3137117.2     13926061.39      3137118.86     13925871.75
      3137059.73     13924087.03      3137372.58     13923052.54
#Sta/Elev= 30
    3961   84.31  4083.1    84.6  4598.6    82.6  4735.7   82.63  4779.5   84.09
  4870.8    84.4 4918.63   82.72 4964.35   71.29 5044.35   71.29 5090.45   82.82
  5290.9   81.64  5335.9   80.46    5396   80.86    5426   80.26    5531   81.14
  5936.3   81.09  5951.3   82.19  6071.4   80.84  6281.5   81.58  6671.7   80.99
  6701.7   79.85  6712.5   79.99  6896.8   80.97  6971.8   79.94  7003.2   82.03
  7134.8   82.48  7304.4   83.48  7394.9   82.23  7914.6   82.72  8053.1   83.67
#Mann= 7 ,-1 , 0
    3961      .2       0    3961     .14       0  4598.6      .1       0
 4918.63     .04       0 5090.45      .1       0  6712.5     .04       0
  7134.8     .14       0
#XS Ineff= 2 , 0
       0    4870      85    6073       0      85
Permanent Ineff=
       F       F
Bank Sta=4918.63,5090.45
XS Rating Curve= 0 ,0
Exp/Cntr=0.3,0.1

Type RM Length L Ch R = 1 ,44181.0 ,639.3,485.9,483.9
BEGIN DESCRIPTION:
Cross Section 44181.0 - Interpolated
END DESCRIPTION:
XS GIS Cut Line= 5
      3137447.71      13927053.3      3137400.82     13926987.86
      3137387.11     13926069.45      3137320.95     13924256.64
      3137436.36     13923728.62
#Sta/Elev= 30
  4000.7   87.05  4146.6   86.19  4221.6   83.24  4326.6   82.73  4356.6   81.32
  4431.6   82.58  4551.6   81.55  4731.6   82.44  4761.6   81.33  4881.7   83.72
 4917.42   82.78 4964.35   71.05 5044.35   71.05 5088.33   82.05  5196.8   80.06
    5497    82.7    5527   80.79  5572.1   82.28  5617.1   80.51  5767.2   80.12
  5962.3   81.95  6067.4   81.67  6097.4   80.01  6473.5   83.07  6697.8   81.21
  6720.2   79.82  6894.7   81.48  6939.7   80.08  7155.8   83.19  7354.2   84.21
#Mann= 6 ,-1 , 0
  4000.7      .2       0  4000.7      .1       0 4917.42     .04       0
 5088.33      .1       0  6720.2     .04       0  6939.7     .14       0
#XS Ineff= 2 , 0
       0    4880      85    6085       0      85
Permanent Ineff=
       F       F
Bank Sta=4917.42,5088.33
XS Rating Curve= 0 ,0
Exp/Cntr=0.3,0.1

Type RM Length L Ch R = 1 ,43695.1 ,431.1,433,599.1
BEGIN DESCRIPTION:
Cross Section 43695.1
END DESCRIPTION:
XS GIS Cut Line= 6
      3137981.58     13927345.98      3137905.26     13926719.03
      3137871.49     13926144.96      3137882.82      13925551.9
      3137819.35     13924317.46       3137749.3     13923820.79
#Sta/Elev= 30
  3736.8   88.11  4107.3   86.31  4374.9   83.34  4675.2   83.23  4705.5   81.95
 4914.38   83.11 4964.35   70.62 5044.35   70.62 5088.55   81.67    5231   82.25
    5381   80.43    5486   82.71    5546   80.78  5591.1   82.54  5755.4   79.77
  5801.4   81.68  5876.5   79.08  5951.6   81.44  6056.7   81.45  6078.1   79.72
  6086.7   78.76  6477.2   82.75    6739    81.8  6770.1   80.07    6838   80.51
  6928.5   83.67  6997.3      80  7039.6   79.81  7171.4   83.66  7274.5   83.84
#Mann= 7 ,-1 , 0
  3736.8      .2       0  3736.8     .14       0 4914.38     .04       0
 5088.55     .14       0  6078.1      .1       0  6770.1     .04       0
  6997.3     .14       0
#XS Ineff= 2 , 0
       0    4900      85    6099       0      85
Permanent Ineff=
       F       F
Bank Sta=4914.38,5088.55
XS Rating Curve= 0 ,0
Exp/Cntr=0.3,0.1

Type RM Length L Ch R = 1 ,43262.1 ,674.4,676.2,592.5
BEGIN DESCRIPTION:
Cross Section 43262.1 - Interpolated
END DESCRIPTION:
XS GIS Cut Line= 5
      3138248.57     13927462.78      3138305.52     13926096.86
      3138305.52     13924931.71      3138174.52     13924171.91
       3138125.3     13923909.71
#Sta/Elev= 30
  3640.8   88.15  4016.4   87.18  4046.4   86.07  4166.5   86.29  4256.6   84.34
 4916.34   81.43  4961.1   70.24  5041.1   70.24 5086.71   81.64  5142.3   82.57
  5427.3   81.88  5472.3   81.38  5485.3   79.68  5502.3   79.51  5530.3   82.14
  5577.3   82.69  5635.3   80.12  5817.3   78.42  5860.3   79.99  5905.3   79.05
  6093.6   80.74  6557.9   80.97  6649.2   82.36  6816.6   81.83    6845   79.92
    6908   78.89  6999.4    83.8    7076   80.64  7121.5   80.08  7210.9   83.08
#Mann= 6 ,-1 , 0
  3640.8     .14       0 4916.34     .04       0 5086.71     .14       0
  6093.6      .1       0    6845     .04       0    7076     .14       0
#XS Ineff= 2 , 0
       0    4916    81.4    6077       0      85
Permanent Ineff=
       F       F
Bank Sta=4916.34,5086.71
XS Rating Curve= 0 ,0
Exp/Cntr=0.3,0.1

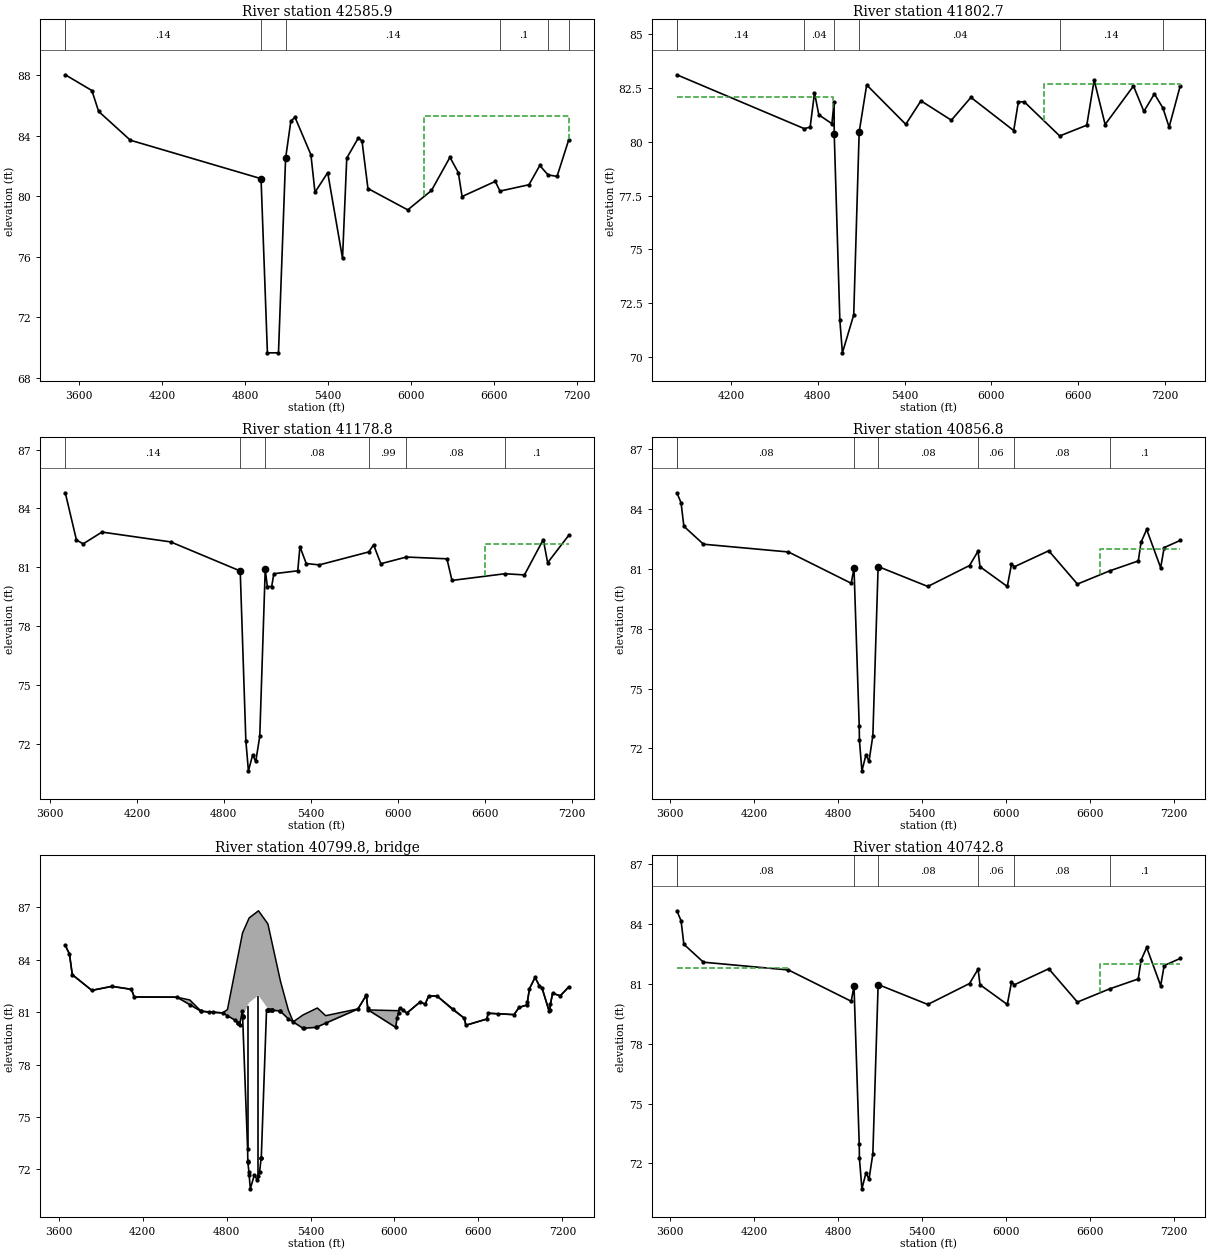
Type RM Length L Ch R = 1 ,42585.9 ,781.2,783.2,827.9
BEGIN DESCRIPTION:
Cross Section 42585.9
END DESCRIPTION:
XS GIS Cut Line= 6
      3138502.86     13927533.77      3138964.33     13926471.38
      3138985.86     13926030.99       3138994.3     13925908.58
       3138837.9     13925138.04      3138527.41     13924051.87
#Sta/Elev= 30
  3500.3   88.01  3692.5   86.97  3741.5   85.59  3970.5   83.69  4915.1   81.15
  4961.1   69.65  5041.1   69.65 5092.52    82.5  5130.6   84.96  5160.7    85.2
  5275.5   82.73  5304.9   80.25  5396.8   81.55  5503.9   75.89  5534.5   82.51
  5618.2   83.84  5644.5   83.65  5687.6    80.5  5975.3   79.09  6146.7   80.37
  6280.2   82.56  6340.8   81.55  6367.8   79.97  6607.8   80.97  6641.7   80.33
  6851.5   80.75  6929.5   82.02  6988.9    81.4  7054.3    81.3  7138.1    83.7
#Mann= 7 ,-1 , 0
  3500.3      .2       0  3500.3     .14       0  4915.1     .04       0
 5092.52     .14       0  6641.7      .1       0  6988.9     .04       0
  7138.1      .2       0
#XS Ineff= 2 , 0
       0                    6095       0    85.3
Permanent Ineff=
       F       F
Bank Sta=4915.1,5092.52
XS Rating Curve= 0 ,0
Exp/Cntr=0.3,0.1

Type RM Length L Ch R = 1 ,41802.7 ,621.8,623.9,651.1
BEGIN DESCRIPTION:
Cross Section 41802.7 - Interpolated
END DESCRIPTION:
XS GIS Cut Line= 6
      3139395.56      13927228.3       3139544.7     13927114.25
      3139728.93     13926596.65      3139764.02     13926166.77
      3139711.39     13925157.89      3139255.19     13923938.45
#Sta/Elev= 30
  3824.7   83.11  4705.7   80.61  4746.6   80.68  4776.7   82.27  4806.8   81.25
  4897.1   80.84  4912.2   81.85  4913.2   80.37    4952   71.73  4969.7    70.2
    5048   71.96  5085.7   80.45  5137.6   82.64    5408   80.81  5513.1    81.9
  5723.4      81  5858.6   82.06  6154.7   80.52    6187   81.86  6228.4   81.85
  6472.9   80.27  6660.2   80.77  6711.2   82.86    6787    80.8  6983.1   82.59
    7055   81.41  7127.7   82.22  7186.7   81.57  7229.6   80.68  7306.6    82.6
#Mann= 7 , 1 , 0
  3824.7      .2       0  3824.7     .14       0  4705.7     .04       0
  4913.2     .04       0  5085.7     .04       0  6472.9     .14       0
  7186.7     .04       0
#XS Ineff= 2 , 0
       0    4908    82.1    6365       0    82.7
Permanent Ineff=
       F       F
Bank Sta=4913.2,5085.7
XS Rating Curve= 0 ,0
Exp/Cntr=0.3,0.1

Type RM Length L Ch R = 1 ,41178.8 ,134.1,322,97.4
BEGIN DESCRIPTION:
Cross Section 41178.8 - Interpolated
END DESCRIPTION:
XS GIS Cut Line= 6
       3139833.1     13927341.71      3140046.19     13927006.21
      3140359.86     13926325.32      3140393.36     13925813.41
      3140247.63     13925287.53      3139567.78     13924220.64
#Sta/Elev= 30
    3706    84.8    3783    82.4  3829.5    82.2  3958.9    82.8  4433.4    82.3
  4913.2   80.82    4952   72.18  4969.7   70.65  4998.8   71.45  5020.4   71.13
    5048   72.41  5085.7    80.9  5100.2   80.03  5130.2   80.03  5145.2   80.68
  5310.2   80.83  5325.2   82.06  5368.5    81.2  5458.5   81.13    5800   81.79
  5833.5   82.15  5883.5   81.19    6060   81.53  6339.4   81.44  6374.4   80.34
  6739.9   80.68  6874.4   80.62  7004.4   82.42  7034.4   81.24  7179.4   82.63
#Mann= 6 , 1 , 0
    3706     .14       0  4913.2    .035       0  5085.7     .08       0
    5800     .99       0    6060     .08       0  6739.9      .1       0
#XS Ineff= 2 , 0
       0                    6603       0    82.2
Permanent Ineff=
       F       F
Bank Sta=4913.2,5085.7
XS Rating Curve= 0 ,0
Exp/Cntr=0.5,0.3

Type RM Length L Ch R = 1 ,40856.8 ,114,114,114
BEGIN DESCRIPTION:
Upstream Section of Bridge/Culvert/Weir
END DESCRIPTION:
XS GIS Cut Line= 6
     3140088.277    13927408.857     3140322.327    13927235.477
     3140586.577    13926586.617     3140842.417    13925775.727
     3140306.907    13924985.377     3139833.507    13924338.707
#Sta/Elev= 30
    3647   84.82    3677   84.32    3697   83.14    3837   82.24  4444.8   81.85
  4893.3   80.28  4913.2   81.04  4950.5   73.13    4952    72.4  4969.7   70.87
  4998.8   71.67  5020.4   71.35    5048   72.63  5085.7   81.12  5440.7   80.12
    5739   81.17    5800   81.89    5814   81.11    6009   80.12    6039   81.24
    6060   81.11  6305.3   81.91  6510.3   80.24  6739.9    80.9  6945.3    81.4
  6965.3   82.34  7005.3   82.98  7105.3   81.06  7130.3   82.07  7245.3   82.43
#Mann= 7 , 1 , 0
    3647      .2       0    3647     .08       0  4913.2    .035       0
  5085.7     .08       0    5800     .06       0    6060     .08       0
  6739.9      .1       0
#XS Ineff= 2 , 0
       0    4440    81.8    6670       0      82
Permanent Ineff=
       F       F
Bank Sta=4913.2,5085.7
XS Rating Curve= 0 ,0
Exp/Cntr=0.5,0.3

Type RM Length L Ch R = 3 ,40799.8 ,,,
BEGIN DESCRIPTION:
FUTURE LEE ROAD
Structure ID: P30-21
END DESCRIPTION:
Bridge Culvert--1,0,-1,-1, 0
Deck Dist Width WeirC Skew NumUp NumDn MinLoCord MaxHiCord MaxSubmerge Is_Ogee
10,94,2.6,0, 59, 59, , , 0.95, 0, 1,1,,
    3647    3677    3697    3837  3979.8  4119.8  4139.8  4444.8  4537.3  4617.8
    4772  4806.3  4862.7  4893.3  4913.2  4914.4  4914.7  4961.4  5028.2 5095.19
  5095.4  5185.4  5241.3  5276.5    5346  5440.7  5449.2  5508.4    5739    5799
    5809    5814    6009    6019  6029.3    6039    6089    6184    6219  6245.3
  6305.3  6500.3  6510.3  6660.3  6670.3  6855.3  6890.3  6945.3  6950.3  6965.3
  7005.3  7035.3  7055.3  7105.3  7110.3  7115.3  7130.3  7185.3  7245.3
   84.83   84.33   83.15   82.25   82.48   82.31   81.87   81.86    81.7   81.06
   80.96   81.15   83.45   84.69    85.5   85.55   85.55    86.4   86.81   86.06
   86.06   82.77   81.13   80.45   80.84   81.21   81.24    80.8   81.19   81.98
   81.25   81.13   81.09   81.09    81.1   81.25   80.95   81.59   81.46   81.93
   81.92   80.65   80.25   80.61   80.94   80.86   81.27   81.41   81.59   82.35
   82.99   82.52   82.38   81.07    81.1   81.47   82.08   81.94   82.44
   84.83   84.33   83.15   82.25   82.48   82.31   81.87   81.86   81.43   81.05
   80.96    80.8   80.53   80.29   81.05    80.8   80.73   81.55   81.96   81.21
   81.13   81.05   80.62   80.44   80.08   80.13   80.16   80.37   81.18   81.97
   81.24   81.12   80.13   80.68   80.97   81.25   80.95   81.59   81.46   81.93
   81.92   80.65   80.25   80.61   80.94   80.86   81.27   81.41   81.59   82.35
   82.99   82.52   82.38   81.07    81.1   81.47   82.08   81.94   82.44
    3647    3677    3697    3837  3979.8  4119.8  4139.8  4444.8  4537.3  4617.8
    4772  4806.3  4862.7  4893.3  4913.2  4914.4  4914.7  4961.4  5028.2 5095.19
  5095.4  5185.4  5241.3  5276.5    5346  5440.7  5449.2  5508.4    5739    5799
    5809    5814    6009    6019  6029.3    6039    6089    6184    6219  6245.3
  6305.3  6500.3  6510.3  6660.3  6670.3  6855.3  6890.3  6945.3  6950.3  6965.3
  7005.3  7035.3  7055.3  7105.3  7110.3  7115.3  7130.3  7185.3  7245.3
   84.83   84.33   83.15   82.25   82.48   82.31   81.87   81.86    81.7   81.06
   80.96   81.15   83.45   84.69    85.5   85.55   85.55    86.4   86.81   86.06
   86.06   82.77   81.13   80.45   80.84   81.21   81.24    80.8   81.19   81.98
   81.25   81.13   81.09   81.09    81.1   81.25   80.95   81.59   81.46   81.93
   81.92   80.65   80.25   80.61   80.94   80.86   81.27   81.41   81.59   82.35
   82.99   82.52   82.38   81.07    81.1   81.47   82.08   81.94   82.44
    84.7    84.2   83.02   82.12   82.35   82.18   81.74   81.73    81.3   80.92
   80.83   80.67    80.4   80.16   80.92   80.67    80.6   81.42   81.83   81.08
      81   80.92   80.49   80.31   79.95      80   80.03   80.24   81.05   81.84
   81.11   80.99      80   80.55   80.84   81.12   80.82   81.46   81.33    81.8
   81.79   80.52   80.12   80.48   80.81   80.73   81.14   81.28   81.46   82.22
   82.86   82.39   82.25   80.94   80.97   81.34   81.95   81.81   82.31
Pier Skew, UpSta & Num, DnSta & Num=  ,4950.5, 2 ,4950.5, 2 , 0 , 0 , 0 ,,
     2.8     2.8
   71.46   82.38
     2.8     2.8
   71.33   82.25
Pier Skew, UpSta & Num, DnSta & Num=  ,5020.4, 2 ,5020.4, 2 , 0 , 0 , 0 ,,
     2.8     2.8
   70.38   82.92
     2.8     2.8
   70.25   82.79
Abutment Skew #Up #Dn= , 2 , 2
  4914.5    4952
   80.73   72.41
  4914.5    4952
    80.6   72.28
Abutment Skew #Up #Dn= , 2 , 2
    5048 5095.39
   72.64   81.21
    5048 5095.39
   72.51   81.08
BR Coef= 1 , 1 , 0 ,1.25, 0 ,,,0.8,0,2,0,
WSPro=,,,, 1 ,,,, 0 ,,,, 0 ,,,,-1 ,-1 ,-1 , 0 , 0 , 0 , 0 , 0
BR U #Sta/Elev= 91
    3647   84.83    3677   84.33    3697   83.15    3837   82.25  3979.8   82.48
  4119.8   82.31  4139.8   81.87  4444.8   81.86  4537.3   81.43  4617.8   81.05
    4620   81.05  4677.1      81    4702   80.99    4772   80.96  4806.3    80.8
  4862.7   80.53 4881.29   80.38  4881.4   80.38 4881.51   80.38  4893.3   80.29
  4913.2   81.05  4914.4    80.8  4914.5   80.77 4914.61   80.75  4914.7   80.73
  4950.5   73.14  4951.9   72.46    4952   72.41  4952.6   72.39  4959.4   71.87
  4961.4   71.68  4969.7   70.88  4998.8   71.68  5020.4   71.36  5028.2   71.61
    5036   71.85  5047.4   72.66  5047.9   72.64    5048   72.64  5085.7   81.13
 5095.19   81.13  5095.3   81.13  5095.4   81.13  5112.9   81.12 5127.99   81.11
  5128.1   81.11 5128.21   81.11  5183.3   81.07  5185.4   81.05  5241.3   80.62
  5276.5   80.44    5346   80.08  5351.2   80.08  5440.7   80.13  5449.2   80.16
  5508.4   80.37    5739   81.18    5799   81.97    5800    81.9    5809   81.24
    5814   81.12    6009   80.13    6019   80.68  6029.3   80.97    6039   81.25
    6060   81.12    6089   80.95    6184   81.59    6219   81.46  6245.3   81.93
  6305.3   81.92  6415.3   81.16  6500.3   80.65  6510.3   80.25  6660.3   80.61
  6670.3   80.94  6739.9   80.91  6855.3   80.86  6890.3   81.27  6945.3   81.41
  6950.3   81.59  6965.3   82.35  7005.3   82.99  7035.3   82.52  7055.3   82.38
  7105.3   81.07  7110.3    81.1  7115.3   81.47  7130.3   82.08  7185.3   81.94
  7245.3   82.44
BR U #Mann= 7
    3647      .2    3647     .08  4913.2    .035  5085.7     .08    5800     .06
    6060     .08  6739.9      .1
BR U Banks=4913.2,5085.7
BR D #Sta/Elev= 91
    3647    84.7    3677    84.2    3697   83.02    3837   82.12  3979.8   82.35
  4119.8   82.18  4139.8   81.74  4444.8   81.73  4537.3    81.3  4617.8   80.92
    4620   80.92  4677.1   80.87    4702   80.86    4772   80.83  4806.3   80.67
  4862.7    80.4 4881.29   80.25  4881.4   80.25 4881.51   80.25  4893.3   80.16
  4913.2   80.92  4914.4   80.67  4914.5   80.64 4914.61   80.62  4914.7    80.6
  4950.5   73.01  4951.9   72.33    4952   72.28  4952.6   72.26  4959.4   71.74
  4961.4   71.55  4969.7   70.75  4998.8   71.55  5020.4   71.23  5028.2   71.48
    5036   71.72  5047.4   72.53  5047.9   72.51    5048   72.51  5085.7      81
 5095.19      81  5095.3      81  5095.4      81  5112.9   80.99 5127.99   80.98
  5128.1   80.98 5128.21   80.98  5183.3   80.94  5185.4   80.92  5241.3   80.49
  5276.5   80.31    5346   79.95  5351.2   79.95  5440.7      80  5449.2   80.03
  5508.4   80.24    5739   81.05    5799   81.84    5800   81.77    5809   81.11
    5814   80.99    6009      80    6019   80.55  6029.3   80.84    6039   81.12
    6060   80.99    6089   80.82    6184   81.46    6219   81.33  6245.3    81.8
  6305.3   81.79  6415.3   81.03  6500.3   80.52  6510.3   80.12  6660.3   80.48
  6670.3   80.81  6739.9   80.78  6855.3   80.73  6890.3   81.14  6945.3   81.28
  6950.3   81.46  6965.3   82.22  7005.3   82.86  7035.3   82.39  7055.3   82.25
  7105.3   80.94  7110.3   80.97  7115.3   81.34  7130.3   81.95  7185.3   81.81
  7245.3   82.31
BR D #Mann= 7
    3647      .2    3647     .08  4913.2    .035  5085.7     .08    5800     .06
    6060     .08  6739.9      .1
BR D Banks=4913.2,5085.7
BC Design=,, 0 ,, 0 ,,,,,,
BC HTab HWMax=84.82
BC Use User HTab Curves=0
BC User HTab FreeFlow(D)= 0

Type RM Length L Ch R = 1 ,40742.8 ,249.1,249.1,249.1
BEGIN DESCRIPTION:
Downstream Section of Bridge/Culvert/Weir
END DESCRIPTION:
XS GIS Cut Line= 6
     3140202.167    13927413.807     3140436.227    13927240.437
     3140700.477    13926591.577     3140956.317    13925780.687
     3140420.807    13924990.337     3139947.397    13924343.657
#Sta/Elev= 30
    3647   84.67    3677   84.17    3697   82.99    3837   82.09  4444.8    81.7
  4893.3   80.13  4913.2   80.89  4950.5   72.98    4952   72.25  4969.7   70.72
  4998.8   71.52  5020.4    71.2    5048   72.48  5085.7   80.97  5440.7   79.97
    5739   81.02    5800   81.74    5814   80.96    6009   79.97    6039   81.09
    6060   80.96  6305.3   81.76  6510.3   80.09  6739.9   80.75  6945.3   81.25
  6965.3   82.19  7005.3   82.83  7105.3   80.91  7130.3   81.92  7245.3   82.28
#Mann= 7 , 1 , 0
    3647      .2       0    3647     .08       0  4913.2    .035       0
  5085.7     .08       0    5800     .06       0    6060     .08       0
  6739.9      .1       0
#XS Ineff= 2 , 0
       0    4440    81.8    6670       0      82
Permanent Ineff=
       F       F
Bank Sta=4913.2,5085.7
XS Rating Curve= 0 ,0
Exp/Cntr=0.5,0.3