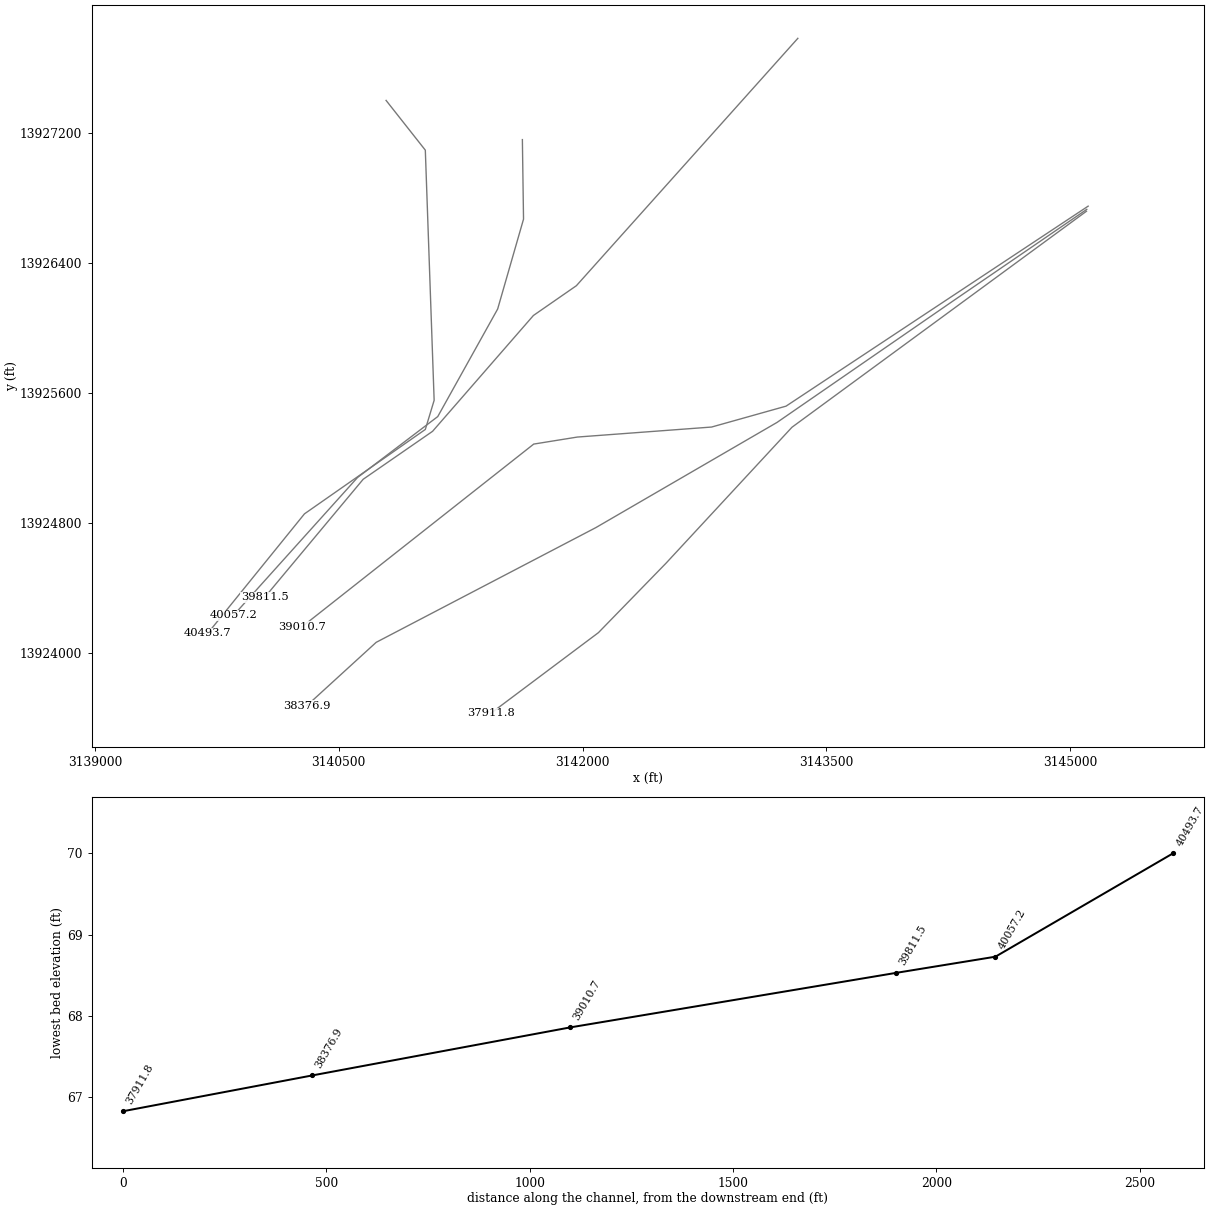
HEC-RAS study P130-00-00.prj: P130-00-00

--- P130-00-00.g01 (geometry) --- (continued)

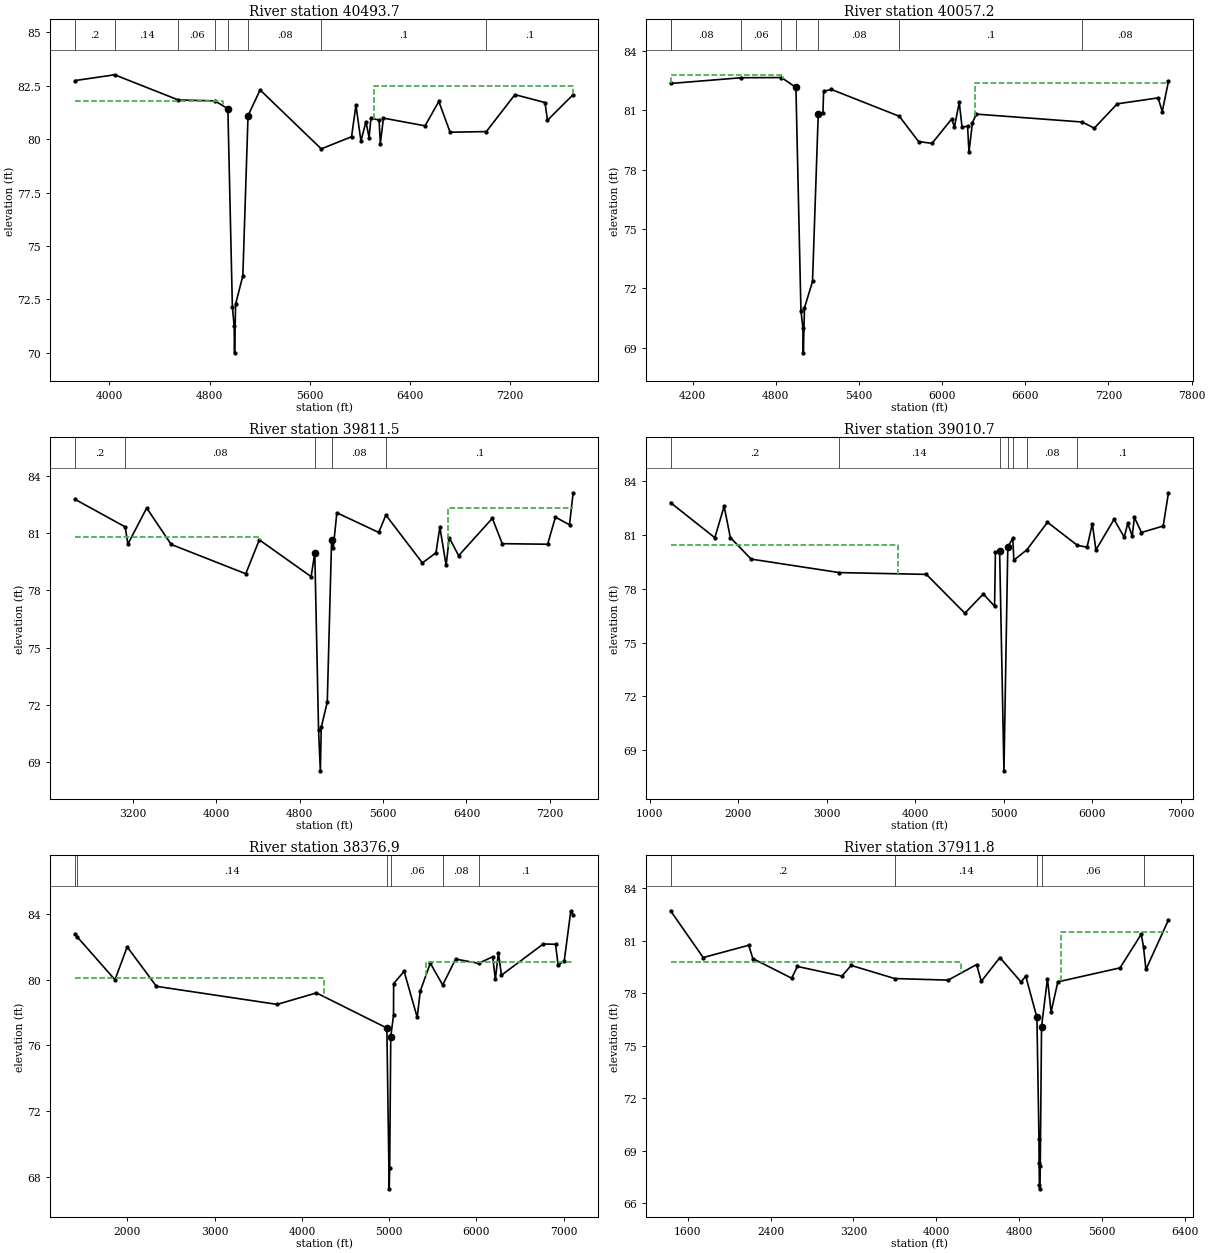
Type RM Length L Ch R = 1 ,40493.7 ,481.6,436.5,143.6
BEGIN DESCRIPTION:
Cross Section 40493.7 - Interpolated
END DESCRIPTION:
XS GIS Cut Line= 6
      3140791.11     13927399.58      3141032.55     13927093.75
      3141086.84     13925555.97      3141032.55     13925376.83
      3140288.86     13924858.04       3139693.9     13924123.83
#Sta/Elev= 30
  3726.9   82.75  4041.3   83.02  4550.1   81.84  4841.3    81.8  4945.5   81.43
  4981.6   72.14  4995.6   71.26  4998.9      70  5007.3   72.28  5065.1   73.61
  5106.6   81.11  5202.9   82.31  5691.3   79.55  5933.1   80.12  5968.1   81.59
  6008.1   79.92  6048.1   80.82  6073.1   80.08  6088.1   80.99  6152.9    80.9
  6162.9    79.8  6187.9   80.99    6520   80.63    6630   81.77    6720   80.33
  7009.3   80.36  7237.6   82.09  7477.6   81.72  7497.6   80.89  7702.6   82.09
#Mann= 8 , 1 , 0
  3726.9      .2       0  4041.3     .14       0  4550.1     .06       0
  4841.3     .08       0  4945.5    .035       0  5106.6     .08       0
  5691.3      .1       0  7009.3      .1       0
#XS Ineff= 2 , 0
       0    4903    81.8    6110       0    82.5
Permanent Ineff=
       F       F
Bank Sta=4945.5,5106.6
XS Rating Curve= 0 ,0
Exp/Cntr=0.3,0.1

Type RM Length L Ch R = 1 ,40057.2 ,545.4,245.7,80.3
BEGIN DESCRIPTION:
Cross Section 40057.2
END DESCRIPTION:
XS GIS Cut Line= 6
       3141629.8     13927158.69      3141636.88     13926669.79
      3141477.68     13926117.21      3141109.06     13925456.05
      3140615.27     13925081.37      3139852.38     13924234.25
#Sta/Elev= 30
  4041.3   82.36  4550.1   82.65  4841.3   82.66  4945.5   82.16  4981.6   70.87
  4995.6   69.99  4998.9   68.73  5007.3   71.01  5065.1   72.34  5106.6   80.84
  5140.4   80.89  5145.3   81.96  5200.3   82.06  5691.3    80.7  5830.3   79.42
  5927.3   79.33  6068.7   80.56  6088.7   80.16  6123.7    81.4  6143.7   80.16
  6183.7   80.19  6193.7   78.88  6218.7   80.38  6246.9   80.81  7009.3   80.41
  7097.8    80.1  7262.8   81.33  7557.8   81.63  7587.8   80.94  7632.8   82.47
#Mann= 8 , 1 , 0
  4041.3      .2       0  4041.3     .08       0  4550.1     .06       0
  4841.3     .08       0  4945.5    .035       0  5106.6     .08       0
  5691.3      .1       0  7009.3     .08       0
#XS Ineff= 2 , 0
       0    4854    82.8    6239       0    82.4
Permanent Ineff=
       F       F
Bank Sta=4945.5,5106.6
XS Rating Curve= 0 ,0
Exp/Cntr=0.3,0.1

Type RM Length L Ch R = 1 ,39811.5 ,1185.5,800.8,439
BEGIN DESCRIPTION:
Cross Section 39811.5 - Interpolated
END DESCRIPTION:
XS GIS Cut Line= 6
      3143324.85      13927781.2      3141962.12     13926260.54
      3141697.66     13926077.45      3141077.18     13925365.42
      3140649.97     13925070.44       3140044.3     13924345.06
#Sta/Elev= 30
  2648.4   82.77  3127.2   81.33  3153.4   80.43  3333.4   82.32  3568.4   80.41
  4283.4   78.87  4413.4   80.65  4910.3   78.72  4945.5   79.96  4981.6   70.67
  4998.9   68.53  5007.3   70.81  5065.1   72.14  5106.6   80.64    5122   80.21
    5157   82.07  5558.3   81.04  5627.2   81.95  5977.2   79.44  6107.2   79.97
  6144.8   81.32  6204.8   79.31  6234.8   80.76  6324.8   79.82    6648   81.78
    6743   80.45    7178   80.42    7253   81.84    7388   81.44    7423   83.12
#Mann= 5 , 1 , 0
  2648.4      .2       0  3127.2     .08       0  4945.5     .04       0
  5106.6     .08       0  5627.2      .1       0
#XS Ineff= 2 , 0
       0    4420   80.81    6225       0    82.3
Permanent Ineff=
       F       F
Bank Sta=4945.5,5106.6
XS Rating Curve= 0 ,0
Exp/Cntr=0.3,0.1

Type RM Length L Ch R = 1 ,39010.7 ,210.6,633.8,752.5
BEGIN DESCRIPTION:
Cross Section 39010.7
END DESCRIPTION:
XS GIS Cut Line= 6
      3145111.37      13926749.6      3143252.28      13925520.1
      3142794.16     13925391.68      3141968.11     13925330.15
       3141699.6     13925286.93       3140272.4     13924162.53
#Sta/Elev= 30
    1234   82.78    1734   80.83    1839   82.58    1909   80.84    2144   79.64
  3139.5   78.89  4123.7   78.79  4558.7   76.63    4767    77.7  4894.1   77.02
  4903.9   80.01  4951.1   80.11  5000.1   67.86  5043.7   80.32 5099.75    80.8
    5112   79.58  5259.5   80.16    5492   81.69  5828.5   80.41  5938.9    80.3
  5998.9   81.61  6038.9   80.15  6243.9   81.85  6358.9   80.86  6398.9   81.63
  6448.9   80.92  6473.9   81.96  6553.9   81.12  6798.9   81.48  6858.9   83.33
#Mann= 7 , 1 , 0
    1234      .2       0  3139.5     .14       0  4951.1     .04       0
  5043.7     .08       0 5099.75     .06       0  5259.5     .08       0
  5828.5      .1       0
#XS Ineff= 2 , 0
       0    3800    80.4    5593       0    81.3
Permanent Ineff=
       F       F
Bank Sta=4951.1,5043.7
XS Rating Curve= 0 ,0
Exp/Cntr=0.3,0.1

Type RM Length L Ch R = 1 ,38376.9 ,179.8,465.1,600.9
BEGIN DESCRIPTION:
Cross Section 38376.9 - Interpolated
END DESCRIPTION:
XS GIS Cut Line= 6
      3145102.84     13926729.82      3144278.87     13926165.99
       3143196.7     13925420.03      3142081.55     13924773.24
      3140730.04     13924068.11      3140303.84      13923679.3
#Sta/Elev= 30
    1404    82.8  1428.4    82.6    1859      80    1999      82    2334    79.6
  3716.8    78.5  4166.8    79.2  4973.2   77.06    5000   67.27  5005.6   68.56
    5018   76.54  5049.5   77.83  5050.9   79.77  5170.9   80.51  5320.9   77.71
  5355.9   79.31  5470.9   81.01  5612.7   79.68  5760.9   81.26  6023.4      81
  6185.9    81.4  6215.9   80.02  6250.9   81.65  6285.9   80.28  6765.3   82.18
  6905.3   82.16  6935.3   80.88  7005.3   81.16  7080.3    84.2  7107.2   83.93
#Mann= 6 , 1 , 0
    1404      .2       0  1428.4     .14       0  4973.2     .04       0
    5018     .06       0  5612.7     .08       0  6023.4      .1       0
#XS Ineff= 2 , 0
       0    4250    80.1    5417       0    81.1
Permanent Ineff=
       F       F
Bank Sta=4973.2,5018
XS Rating Curve= 0 ,0
Exp/Cntr=0.3,0.1

Type RM Length L Ch R = 1 ,37911.8 ,1417.6,793.7,516.2
BEGIN DESCRIPTION:
Cross Section 37911.8
END DESCRIPTION:
XS GIS Cut Line= 5
      3145100.95     13926718.35      3143288.63     13925390.32
      3142513.84     13924554.76      3142097.88     13924127.87
      3141434.94     13923631.47
#Sta/Elev= 30
  1433.9   82.71  1748.9   80.04  2188.9   80.74  2228.9   79.98  2603.9   78.86
  2658.9   79.53  3088.9   78.98  3178.9   79.59    3599   78.84  4115.7   78.75
  4390.7   79.64  4435.7   78.68  4615.7   80.04  4820.2   78.64  4865.2   78.98
  4973.2   76.62  4993.1   69.69  4994.4   68.31  4997.4   67.04    5000   66.83
  5005.6   68.12    5018    76.1  5075.2   78.83  5110.2   76.93  5175.2   78.65
  5776.3   79.45  5981.3   81.37  6003.3   80.64  6026.3   79.36  6244.4   82.19
#Mann= 5 , 1 , 0
  1433.9      .2       0    3599     .14       0  4973.2    .035       0
    5018     .06       0  6003.3      .1       0
#XS Ineff= 2 , 0
       0    4240    79.8    5207       0    81.5
Permanent Ineff=
       F       F
Bank Sta=4973.2,5018
XS Rating Curve= 0 ,0
Exp/Cntr=0.3,0.1