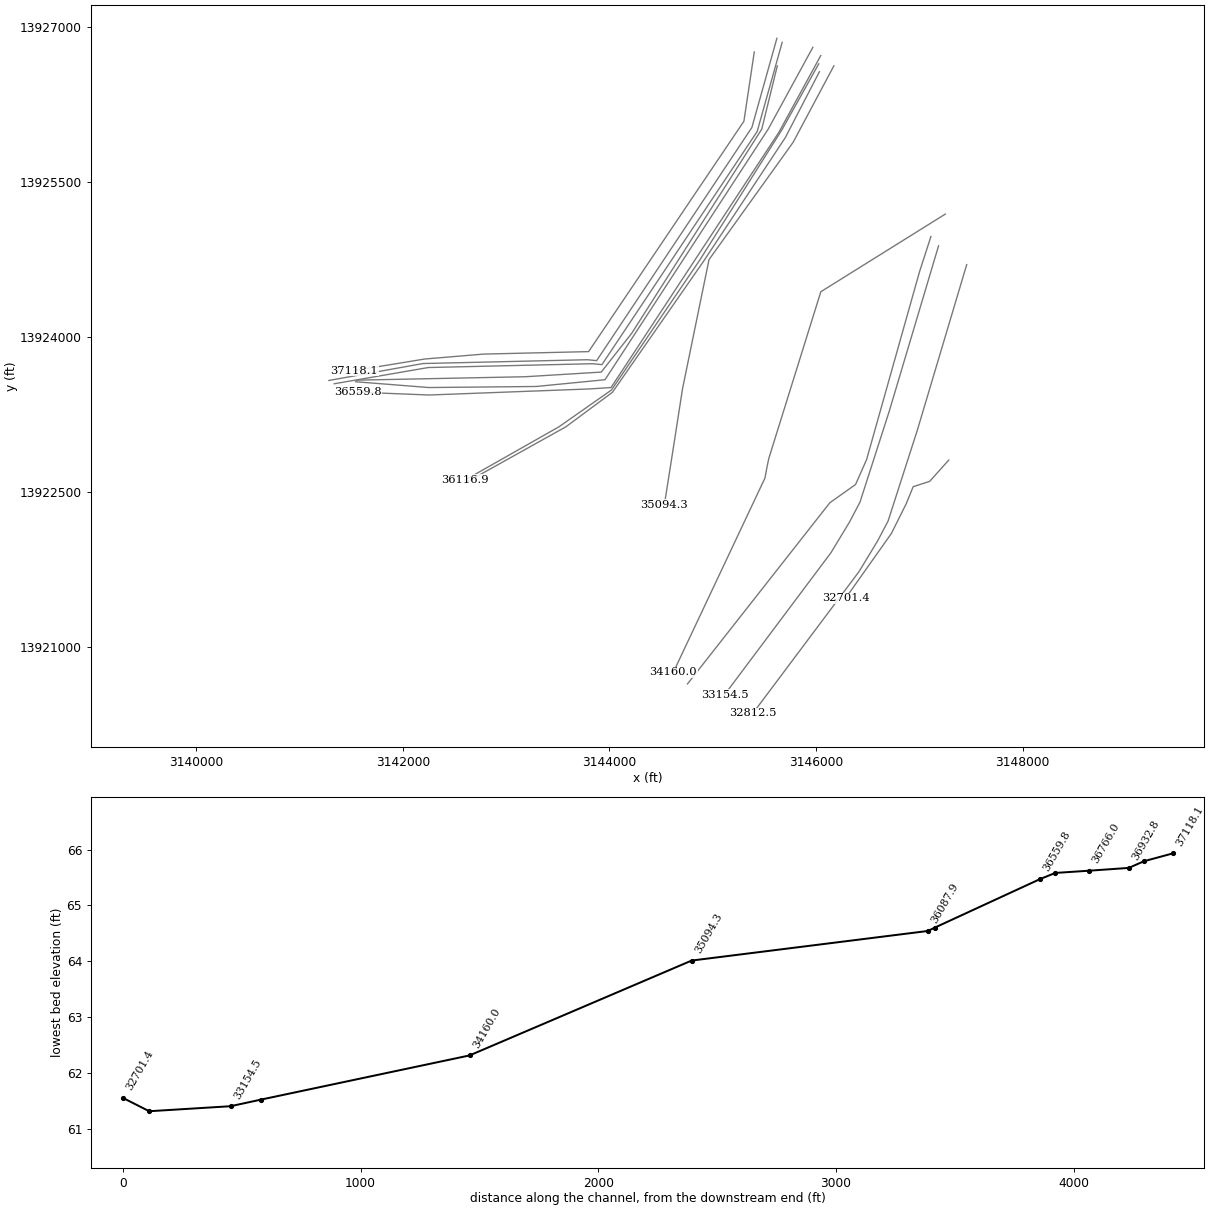
HEC-RAS study P130-00-00.prj: P130-00-00

--- P130-00-00.g01 (geometry) --- (continued)

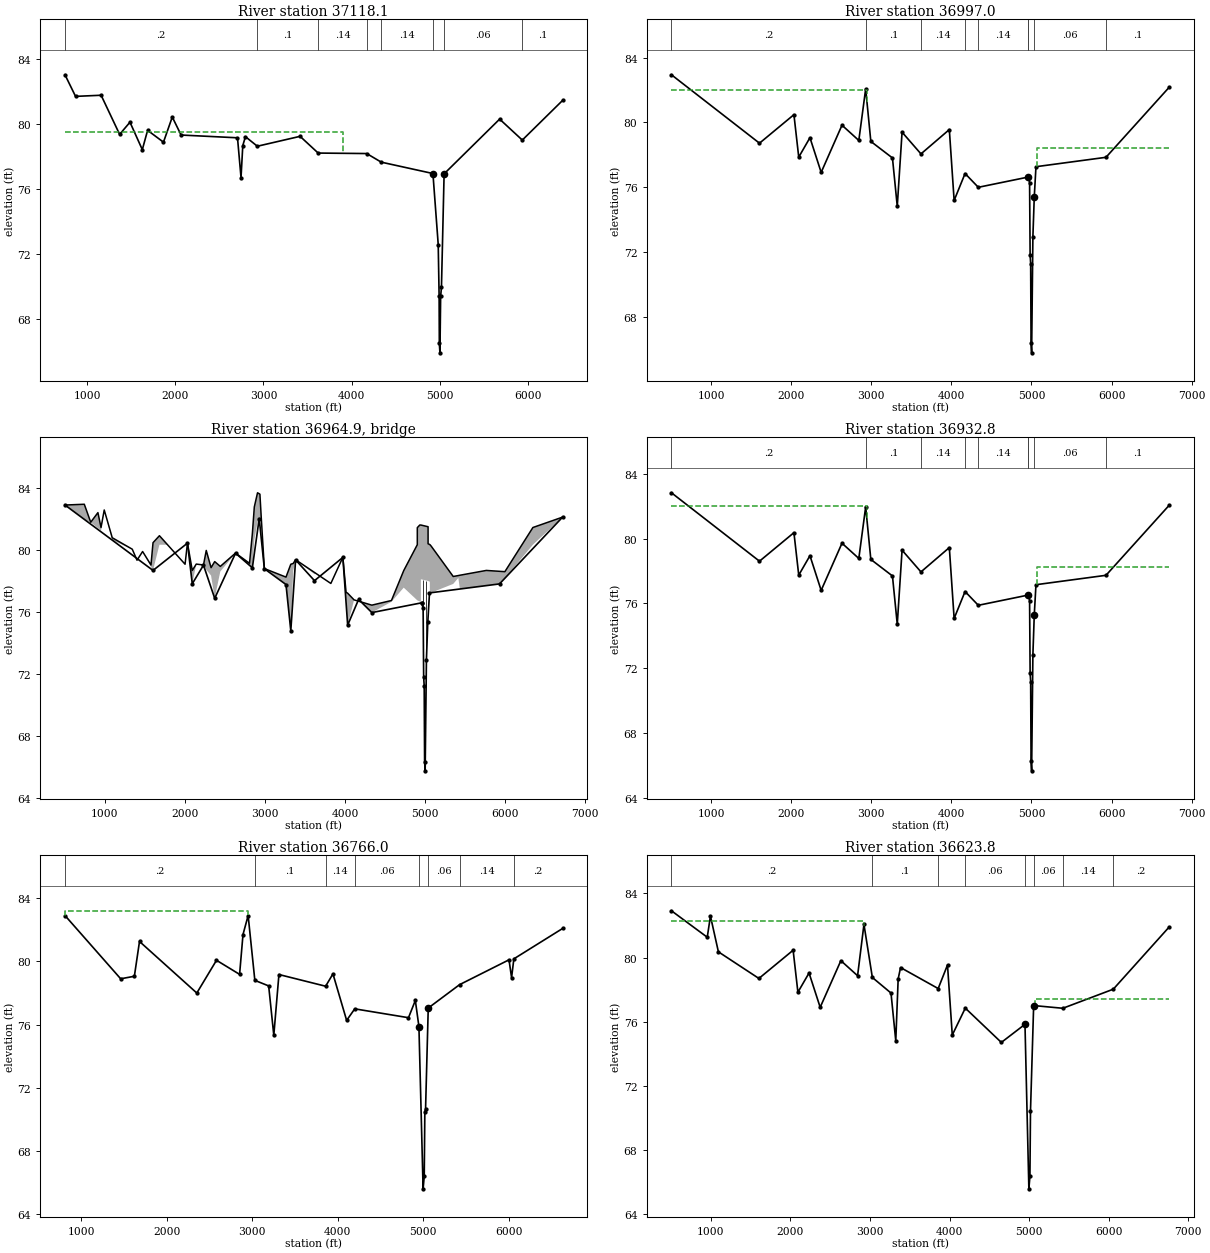
Type RM Length L Ch R = 1 ,37118.1 ,64.1,121.1,72.4
BEGIN DESCRIPTION:
Cross Section 37118.1 - Interpolated
END DESCRIPTION:
XS GIS Cut Line= 6
      3145401.77     13926757.41      3145301.42     13926087.51
      3143798.27     13923860.23      3142781.34     13923836.15
      3142210.82     13923788.51      3141528.35     13923676.47
#Sta/Elev= 30
   747.7   83.05   867.7   81.72  1157.7   81.79  1367.7   79.38  1485.1   80.13
  1625.1   78.44  1685.1   79.63  1865.1    78.9  1965.1   80.45  2065.1   79.34
  2705.1   79.17  2745.1   76.72  2765.1   78.69  2795.1   79.24  2930.3   78.65
  3415.1   79.26  3620.5   78.23  4171.1    78.2  4336.3   77.67  4922.5   76.97
  4982.5    72.6  4992.7   69.42  4995.1   66.52    5002   65.93    5010   69.41
  5019.3   69.97  5049.3   76.95  5679.4   80.32  5936.5   79.03  6393.5   81.47
#Mann= 8 , 1 , 0
   747.7      .2       0  2930.3      .1       0  3620.5     .14       0
  4171.1      .1       0  4336.3     .14       0  4922.5    .035       0
  5049.3     .06       0  5936.5      .1       0
#XS Ineff= 2 , 0
       0    3900    79.5               0
Permanent Ineff=
       F       F
Bank Sta=4922.5,5049.3
XS Rating Curve= 0 ,0
Exp/Cntr=0.5,0.3

Type RM Length L Ch R = 1 ,36997.0 ,64.2,64.2,64.2
BEGIN DESCRIPTION:
Upstream Section of Bridge/Culvert/Weir
END DESCRIPTION:
XS GIS Cut Line= 6
     3145620.609    13926889.084     3145378.609    13926027.124
     3143875.769    13923772.874     3143786.659    13923781.794
     3142194.549    13923744.864     3141283.719    13923581.074
#Sta/Elev= 30
   505.5   82.94  1604.6   78.72  2034.6   80.48  2094.6   77.86  2234.6   79.06
  2374.6   76.92  2634.6   79.83  2844.6   78.89  2930.3   82.07  2994.6   78.83
  3264.6   77.81  3324.6   74.83  3384.6    79.4  3620.5   78.06  3974.6   79.56
  4034.6   75.19  4171.1   76.85  4336.3      76  4957.8   76.63  4960.6   76.62
  4976.6   76.28  4983.3   71.82    4990   71.29  4995.1   66.38    5002   65.79
  5017.8   72.95  5034.9   75.39  5056.2   77.27  5930.3   77.85  6717.6   82.16
#Mann= 9 , 1 , 0
   505.5      .2       0  2930.3      .1       0  3620.5     .14       0
  4171.1      .1       0  4336.3     .14       0  4957.8     .06       0
  4960.6    .035       0  5034.9     .06       0  5930.3      .1       0
#XS Ineff= 2 , 0
       0    2948      82    5071       0    78.4
Permanent Ineff=
       F       F
Bank Sta=4960.6,5034.9
XS Rating Curve= 0 ,0
Exp/Cntr=0.5,0.3

Type RM Length L Ch R = 3 ,36964.9 ,,,
BEGIN DESCRIPTION:
WEST WILL CLAYTON PARKWAY
Structure ID: P30-19
END DESCRIPTION:
Bridge Culvert--1,0,-1,-1, 0
Deck Dist Width WeirC Skew NumUp NumDn MinLoCord MaxHiCord MaxSubmerge Is_Ogee
10,44.2,2.6,0, 60, 60, , , 0.95, 0, 1,1,,
   505.5   746.7   826.7   916.7   955.5   995.5  1095.5  1345.5  1404.6  1474.6
  1579.2  1604.6  1684.6  2004.6  2034.6  2094.6  2144.6  2234.6  2269.2  2329.2
  2374.6  2444.6  2634.6  2809.2  2844.6  2869.2  2909.2  2939.2  2954.6  2994.6
  3264.6  3324.6  3354.6  3384.6  3824.6  3974.6  4014.6  4024.6  4034.6  4114.6
  4336.3  4581.3  4734.5 4903.89    4904  4934.8 4948.21  4948.3  5038.5 5038.61
 5060.49  5060.6    5077  5352.4  5416.6  5435.2  5765.2  5997.2  6347.2  6717.6
   82.93   82.98   81.82   82.44   81.48   82.61   80.82   80.08   79.37   79.93
   79.06    80.5   80.95   79.11   80.48   78.71   79.12   79.06      80   78.89
   79.28   78.97   79.83   79.17   81.07   82.81   83.72   83.63   82.23   78.83
   78.28   79.11   79.16    79.4   77.87   79.56    77.3   77.27   77.24   76.81
   76.47   76.77    78.7   80.37   81.47   81.64   81.64   81.64   81.53   80.43
   80.38   80.38   80.28   78.32   78.38    78.4   78.71   78.63   81.48   82.15
   82.93   81.66   81.81   81.44   81.28    82.6   80.37   80.07   79.18   79.92
   78.95   78.71   80.37   79.06   80.47   77.85   79.11   79.05   78.76   78.38
   76.91   78.64   79.82   78.67   78.88   80.66   81.83   82.02   81.96   78.82
    77.8   74.82   78.68   79.39   77.67   79.55   76.94   75.41   75.18    76.8
   75.99   76.69    77.6   76.78   76.78   76.71   76.66   78.14   78.03   78.03
   77.98   77.06    76.3   77.84   78.23   76.48    76.9   78.08   80.37   82.15
   505.5   746.7   826.7   916.7   955.5   995.5  1095.5  1345.5  1404.6  1474.6
  1579.2  1604.6  1684.6  2004.6  2034.6  2094.6  2144.6  2234.6  2269.2  2329.2
  2374.6  2444.6  2634.6  2809.2  2844.6  2869.2  2909.2  2939.2  2954.6  2994.6
  3264.6  3324.6  3354.6  3384.6  3824.6  3974.6  4014.6  4024.6  4034.6  4114.6
  4336.3  4581.3  4734.5 4903.89    4904  4934.8 4948.21  4948.3  5038.5 5038.61
 5060.49  5060.6    5077  5352.4  5416.6  5435.2  5765.2  5997.2  6347.2  6717.6
   82.93   82.98   81.82   82.44   81.48   82.61   80.82   80.08   79.37   79.93
   79.06    80.5   80.95   79.11   80.48   78.71   79.12   79.06      80   78.89
   79.28   78.97   79.83   79.17   81.07   82.81   83.72   83.63   82.23   78.83
   78.28   79.11   79.16    79.4   77.87   79.56    77.3   77.27   77.24   76.81
   76.47   76.77    78.7   80.37   81.47   81.64   81.64   81.64   81.53   80.43
   80.38   80.38   80.28   78.32   78.38    78.4   78.71   78.63   81.48   82.15
   82.82   81.55    81.7   81.33   81.17   82.49   80.26   79.96   79.07   79.81
   78.84    78.6   80.26   78.95   80.36   77.74      79   78.94   78.65   78.27
    76.8   78.53   79.71   78.56   78.77   80.55   81.72   81.91   81.85   78.71
   77.69   74.71   78.57   79.28   77.56   79.44   76.83    75.3   75.07   76.69
   75.88   76.58   77.49   76.67   76.67    76.6   76.55   78.03   77.92   77.92
   77.87   76.95   76.19   77.73   78.12   76.37   76.79   77.97   80.26   82.04
Pier Skew, UpSta & Num, DnSta & Num=  ,4973.2, 2 ,4973.2, 2 , 0 , 0 , 0 ,,
     1.3     1.3
   75.33   79.13
     1.3     1.3
   75.22   79.02
Pier Skew, UpSta & Num, DnSta & Num=  ,5017.5, 2 ,5017.5, 2 , 0 , 0 , 0 ,,
     1.3     1.3
   71.45   79.08
     1.3     1.3
   71.34   78.97
BR Coef= 1 , 1 , 0 ,1.25, 0 ,,,0.8,0,2,0,
WSPro=,,,, 1 ,,,, 0 ,,,, 0 ,,,,-1 ,-1 ,-1 , 0 , 0 , 0 , 0 , 0
BR U #Sta/Elev= 30
   505.5   82.93  1604.6   78.71  2034.6   80.47  2094.6   77.85  2234.6   79.05
  2374.6   76.91  2634.6   79.82  2844.6   78.88  2930.3   82.06  2994.6   78.82
  3264.6    77.8  3324.6   74.82  3384.6   79.39  3620.5   78.05  3974.6   79.55
  4034.6   75.18  4171.1   76.84  4336.3   75.99  4957.8   76.62  4960.6   76.61
  4976.6   76.27  4983.3   71.81    4990   71.28  4995.1   66.37    5002   65.78
  5017.8   72.94  5034.9   75.38  5056.2   77.26  5930.3   77.84  6717.6   82.15
BR U #Mann= 9
   505.5      .2  2930.3      .1  3620.5     .14  4171.1      .1  4336.3     .14
  4957.8     .06  4960.6    .035  5034.9     .06  5930.3      .1
BR U Banks=4960.6,5034.9
BR D #Sta/Elev= 30
   505.5   82.82  1604.6    78.6  2034.6   80.36  2094.6   77.74  2234.6   78.94
  2374.6    76.8  2634.6   79.71  2844.6   78.77  2930.3   81.95  2994.6   78.71
  3264.6   77.69  3324.6   74.71  3384.6   79.28  3620.5   77.94  3974.6   79.44
  4034.6   75.07  4171.1   76.73  4336.3   75.88  4957.8   76.51  4960.6    76.5
  4976.6   76.16  4983.3    71.7    4990   71.17  4995.1   66.26    5002   65.67
  5017.8   72.83  5034.9   75.27  5056.2   77.15  5930.3   77.73  6717.6   82.04
BR D #Mann= 9
   505.5      .2  2930.3      .1  3620.5     .14  4171.1      .1  4336.3     .14
  4957.8     .06  4960.6    .035  5034.9     .06  5930.3      .1
BR D Banks=4960.6,5034.9
BC Design=,, 0 ,, 0 ,,,,,,
BC HTab HWMax=82.94
BC Use User HTab Curves=0
BC User HTab FreeFlow(D)= 0

Type RM Length L Ch R = 1 ,36932.8 ,166.8,166.8,166.8
BEGIN DESCRIPTION:
Downstream Section of Bridge/Culvert/Weir
END DESCRIPTION:
XS GIS Cut Line= 6
     3145671.859    13926850.424     3145429.869    13925988.463
     3143927.029    13923734.214     3143837.919    13923743.134
     3142245.809    13923706.204     3141335.554    13923549.348
#Sta/Elev= 30
   505.5   82.82  1604.6    78.6  2034.6   80.36  2094.6   77.74  2234.6   78.94
  2374.6    76.8  2634.6   79.71  2844.6   78.77  2930.3   81.95  2994.6   78.71
  3264.6   77.69  3324.6   74.71  3384.6   79.28  3620.5   77.94  3974.6   79.44
  4034.6   75.07  4171.1   76.73  4336.3   75.88  4957.8   76.51  4960.6    76.5
  4976.6   76.16  4983.3    71.7    4990   71.17  4995.1   66.26    5002   65.67
  5017.8   72.83  5034.9   75.27  5056.2   77.15  5930.3   77.73  6717.6   82.04
#Mann= 9 , 1 , 0
   505.5      .2       0  2930.3      .1       0  3620.5     .14       0
  4171.1      .1       0  4336.3     .14       0  4957.8     .06       0
  4960.6    .035       0  5034.9     .06       0  5930.3      .1       0
#XS Ineff= 2 , 0
       0    2948      82    5071       0   78.25
Permanent Ineff=
       F       F
Bank Sta=4960.6,5034.9
XS Rating Curve= 0 ,0
Exp/Cntr=0.5,0.3

Type RM Length L Ch R = 1 ,36766.0 ,28.8,142.2,105.1
BEGIN DESCRIPTION:
Cross Section 36766.0 - Interpolated
END DESCRIPTION:
XS GIS Cut Line= 6
      3145624.71     13926623.64      3145473.93      13926010.8
      3144214.95     13924036.64       3143920.3     13923662.18
      3143186.12     13923617.37       3141554.2     13923584.24
#Sta/Elev= 30
   810.8    82.9  1461.9    78.9  1621.9   79.06  1681.9   81.26  2351.9      78
  2581.9   80.07  2851.9   79.18  2891.9    81.7  2951.9    82.9  3030.3    78.8
  3191.9   78.45  3251.9   75.33  3311.9   79.17  3857.6   78.43  3943.4   79.21
  4103.4   76.27  4198.1      77  4826.4   76.44  4906.4   77.53  4948.4   75.88
  4997.2   65.62  5010.5   66.41  5017.5   70.46    5026   70.67  5057.3   77.05
  5423.9   78.53  6001.5    80.1  6031.5   78.97  6058.1   80.16  6627.7   82.08
#Mann= 8 , 1 , 0
   810.8      .2       0  3030.3      .1       0  3857.6     .14       0
  4198.1     .06       0  4948.4    .035       0  5057.3     .06       0
  5423.9     .14       0  6058.1      .2       0
#XS Ineff= 2 , 0
       0    2950    83.2               0
Permanent Ineff=
       F       F
Bank Sta=4948.4,5057.3
XS Rating Curve= 0 ,0
Exp/Cntr=0.5,0.3

Type RM Length L Ch R = 1 ,36623.8 ,64,64,64
BEGIN DESCRIPTION:
Upstream Section of Bridge/Culvert/Weir
END DESCRIPTION:
XS GIS Cut Line= 6
     3145968.684    13926801.994     3145537.556    13926013.035
     3143957.132    13923588.521     3143291.207    13923523.042
     3142250.892    13923512.835     3141542.571    13923568.929
#Sta/Elev= 30
   505.5   82.92   955.5   81.27   995.5   82.59  1095.5   80.36  1604.6    78.7
  2034.6   80.46  2094.6   77.84  2234.6   79.04  2374.6    76.9  2634.6   79.81
  2844.6   78.87  2924.6   82.07  3030.3   78.76  3264.6   77.79  3324.6   74.81
  3354.6   78.67  3384.6   79.38  3857.6   78.07  3974.6   79.54  4034.6   75.17
  4198.1   76.85  4651.3   74.71  4948.2   75.84  4997.2   65.58  5010.5   66.37
  5017.5   70.42  5057.3   77.01  5423.9   76.84  6058.1   78.03  6758.7    81.9
#Mann= 8 , 1 , 0
   505.5      .2       0  3030.3      .1       0  3857.6     .14       0
  4198.1     .06       0  4948.2    .035       0  5057.3     .06       0
  5423.9     .14       0  6058.1      .2       0
#XS Ineff= 2 , 0
       0    2928    82.3    5070       0    77.4
Permanent Ineff=
       F       F
Bank Sta=4948.2,5057.3
XS Rating Curve= 0 ,0
Exp/Cntr=0.5,0.3

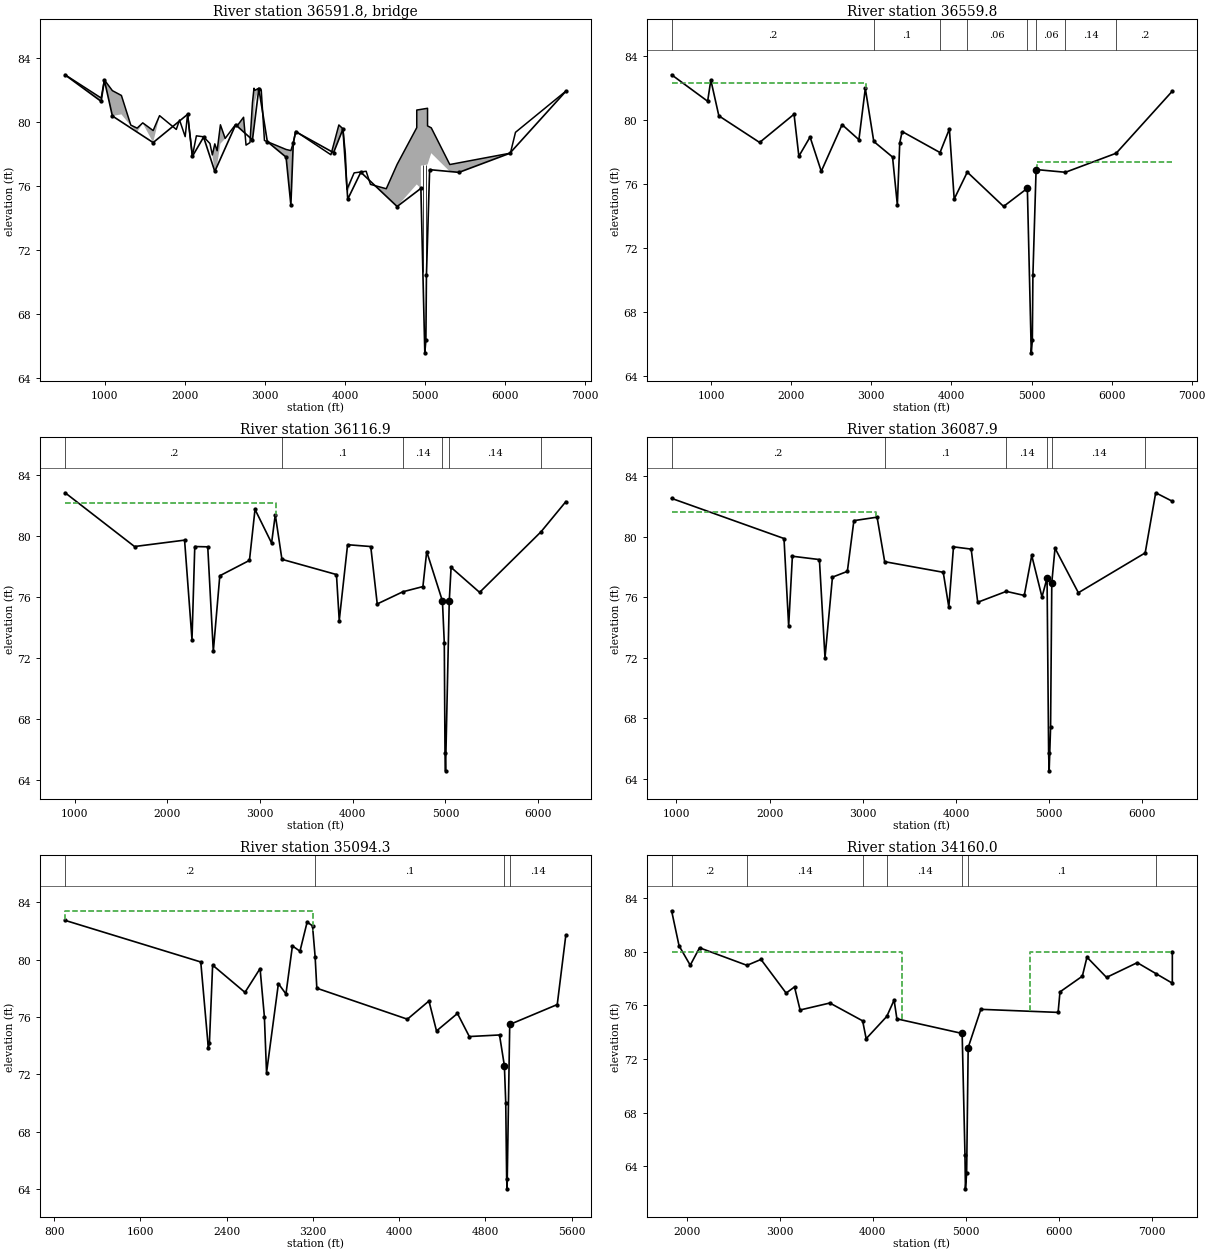
Type RM Length L Ch R = 3 ,36591.8 ,,,
BEGIN DESCRIPTION:
EAST WILL CLAYTON PARKWAY
Structure ID: P30-19
END DESCRIPTION:
Bridge Culvert--1,0,-1,-1, 0
Deck Dist Width WeirC Skew NumUp NumDn MinLoCord MaxHiCord MaxSubmerge Is_Ogee
10,44,2.6,0, 60, 60, , , 0.95, 0, 1,1,,
   505.5   955.5   995.5  1095.5  1208.2  1325.5  1404.6  1474.6  1604.6  1684.6
  1893.8  1933.8  2004.6  2034.6  2094.6  2144.6  2234.6  2313.8  2343.8  2374.6
  2403.8  2444.6  2503.8  2634.6  2654.6  2733.8  2764.6  2813.8  2844.6  2863.8
  2874.6  2924.6  2954.6  2994.6  3264.6  3324.6  3354.6  3384.6  3824.6  3923.8
  3974.6  4004.6  4024.6  4114.6  4264.6  4318.7    4516  4651.4 4896.49  4896.6
  4948.2  4948.3  5031.3 5031.41  5077.7  5309.3  5765.2    6066  6129.6  6758.7
   82.93   81.48   82.61   81.94   81.64   79.79    79.6   79.93   79.45   80.38
   79.52   80.11   79.07   80.48   77.86   79.12   79.06   78.64   77.93   78.62
   78.19   79.81   78.96   79.83   79.75   80.28   78.54    78.7   81.18   82.09
   81.96   82.09   81.97   78.83   78.27    78.2   78.69    79.4   77.94    79.8
   79.56   78.02   75.78   76.81   76.91   76.09   75.82   77.34   79.63   80.73
   80.77   80.77   80.84   79.74   79.62   77.33   77.76   78.04   79.34   81.91
   82.92   81.27   82.59   80.36   80.46   79.75   79.17   79.91    78.7   80.36
    79.5   79.34   79.05   80.46   77.84    79.1   79.04   78.62   77.91    76.9
   77.31   78.63   78.94   79.81    79.1   79.35   78.39   78.69   78.87   80.07
   81.27   82.07   81.95   78.81   77.79   74.81   78.67   79.38   77.66    78.9
   79.54      78    75.4   76.79   76.89   75.91   75.28   74.71   76.09   76.09
   75.84   77.26   77.33   77.33   78.04   76.75   76.89   78.01   79.32    81.9
   505.5   955.5   995.5  1095.5  1208.2  1325.5  1404.6  1474.6  1604.6  1684.6
  1893.8  1933.8  2004.6  2034.6  2094.6  2144.6  2234.6  2313.8  2343.8  2374.6
  2403.8  2444.6  2503.8  2634.6  2654.6  2733.8  2764.6  2813.8  2844.6  2863.8
  2874.6  2924.6  2954.6  2994.6  3264.6  3324.6  3354.6  3384.6  3824.6  3923.8
  3974.6  4004.6  4024.6  4114.6  4264.6  4318.7    4516  4651.4 4896.49  4896.6
  4948.2  4948.3  5031.3 5031.41  5077.7  5309.3  5765.2    6066  6129.6  6758.7
   82.93   81.48   82.61   81.94   81.64   79.79    79.6   79.93   79.45   80.38
   79.52   80.11   79.07   80.48   77.86   79.12   79.06   78.64   77.93   78.62
   78.19   79.81   78.96   79.83   79.75   80.28   78.54    78.7   81.18   82.09
   81.96   82.09   81.97   78.83   78.27    78.2   78.69    79.4   77.94    79.8
   79.56   78.02   75.78   76.81   76.91   76.09   75.82   77.34   79.63   80.73
   80.77   80.77   80.84   79.74   79.62   77.33   77.76   78.04   79.34   81.91
   82.83   81.18    82.5   80.27   80.37   79.66   79.08   79.82   78.61   80.27
   79.41   79.25   78.96   80.37   77.75   79.01   78.95   78.53   77.82   76.81
   77.22   78.54   78.85   79.72   79.01   79.26    78.3    78.6   78.78   79.98
   81.18   81.98   81.86   78.72    77.7   74.72   78.58   79.29   77.57   78.81
   79.45   77.91   75.31    76.7    76.8   75.82   75.19   74.62      76      76
   75.75   77.17   77.24   77.24   77.95   76.66    76.8   77.92   79.23   81.81
Pier Skew, UpSta & Num, DnSta & Num=  ,4973.2, 2 ,4973.2, 2 , 0 , 0 , 0 ,,
     1.3     1.3
   69.98   78.28
     1.3     1.3
   69.89   78.19
Pier Skew, UpSta & Num, DnSta & Num=  ,5017.5, 2 ,5017.5, 2 , 0 , 0 , 0 ,,
     1.3     1.3
   68.78   78.32
     1.3     1.3
   68.69   78.23
BR Coef= 1 , 1 , 0 ,1.25, 0 ,,,0.8,0,2,0,
WSPro=,,,, 1 ,,,, 0 ,,,, 0 ,,,,-1 ,-1 ,-1 , 0 , 0 , 0 , 0 , 0
BR U #Sta/Elev= 30
   505.5   82.92   955.5   81.27   995.5   82.59  1095.5   80.36  1604.6    78.7
  2034.6   80.46  2094.6   77.84  2234.6   79.04  2374.6    76.9  2634.6   79.81
  2844.6   78.87  2924.6   82.07  3030.3   78.76  3264.6   77.79  3324.6   74.81
  3354.6   78.67  3384.6   79.38  3857.6   78.07  3974.6   79.54  4034.6   75.17
  4198.1   76.85  4651.3   74.71  4948.2   75.84  4997.2   65.58  5010.5   66.37
  5017.5   70.42  5057.3   77.01  5423.9   76.84  6058.1   78.03  6758.7    81.9
BR U #Mann= 8
   505.5      .2  3030.3      .1  3857.6     .14  4198.1     .06  4948.2    .035
  5057.3     .06  5423.9     .14  6058.1      .2
BR U Banks=4948.2,5057.3
BR D #Sta/Elev= 30
   505.5   82.83   955.5   81.18   995.5    82.5  1095.5   80.27  1604.6   78.61
  2034.6   80.37  2094.6   77.75  2234.6   78.95  2374.6   76.81  2634.6   79.72
  2844.6   78.78  2924.6   81.98  3030.3   78.67  3264.6    77.7  3324.6   74.72
  3354.6   78.58  3384.6   79.29  3857.6   77.98  3974.6   79.45  4034.6   75.08
  4198.1   76.76  4651.3   74.62  4948.2   75.75  4997.2   65.49  5010.5   66.28
  5017.5   70.33  5057.3   76.92  5423.9   76.75  6058.1   77.94  6758.7   81.81
BR D #Mann= 8
   505.5      .2  3030.3      .1  3857.6     .14  4198.1     .06  4948.2    .035
  5057.3     .06  5423.9     .14  6058.1      .2
BR D Banks=4948.2,5057.3
BC Design=,, 0 ,, 0 ,,,,,,
BC HTab HWMax=82.92
BC Use User HTab Curves=0
BC User HTab FreeFlow(D)= 0

Type RM Length L Ch R = 1 ,36559.8 ,442.9,442.9,442.9
BEGIN DESCRIPTION:
Downstream Section of Bridge/Culvert/Weir
END DESCRIPTION:
XS GIS Cut Line= 6
     3146045.398    13926722.461     3145638.669    13925978.051
     3144015.138    13923512.921     3143805.118    13923499.181
     3142256.188    13923440.611     3141564.048    13923468.001
#Sta/Elev= 30
   505.5   82.81   955.5   81.16   995.5   82.48  1095.5   80.25  1604.6   78.59
  2034.6   80.35  2094.6   77.73  2234.6   78.93  2374.6   76.79  2634.6    79.7
  2844.6   78.76  2924.6   81.96  3030.3   78.65  3264.6   77.68  3324.6    74.7
  3354.6   78.56  3384.6   79.27  3857.6   77.96  3974.6   79.43  4034.6   75.06
  4198.1   76.74  4651.3    74.6  4948.2   75.73  4997.2   65.47  5010.5   66.26
  5017.5   70.31  5057.3    76.9  5423.9   76.73  6058.1   77.92  6758.7   81.79
#Mann= 8 , 1 , 0
   505.5      .2       0  3030.3      .1       0  3857.6     .14       0
  4198.1     .06       0  4948.2    .035       0  5057.3     .06       0
  5423.9     .14       0  6058.1      .2       0
#XS Ineff= 2 , 0
       0    2928    82.3    5070       0    77.4
Permanent Ineff=
       F       F
Bank Sta=4948.2,5057.3
XS Rating Curve= 0 ,0
Exp/Cntr=0.5,0.3

Type RM Length L Ch R = 1 ,36116.9 ,29,29,29
BEGIN DESCRIPTION:
Cross Section 36116.9 - Interpolated
END DESCRIPTION:
XS GIS Cut Line= 6
      3146026.01     13926642.75       3145670.5     13926006.68
      3144870.35     13924739.38      3144019.17     13923488.76
      3143509.88     13923132.52       3142604.4     13922619.85
#Sta/Elev= 30
   896.1   82.86  1644.8   79.33  2184.8   79.75  2264.8   73.22  2294.8   79.33
  2434.8   79.31  2494.8   72.45  2564.8   77.41  2884.8   78.42  2944.8   81.77
  3123.5   79.56  3163.5   81.42  3235.1   78.49  3823.5   77.49  3853.5   74.47
  3943.5   79.45  4193.5   79.33  4263.5   75.56  4540.6   76.36  4756.3    76.7
  4797.3      79    4967   75.75    4987      73  4994.7   65.75  5000.3    64.6
  5040.4   75.73  5060.4   77.96  5368.1   76.32  6030.9    80.3  6298.7   82.28
#Mann= 6 , 1 , 0
   896.1      .2       0  3235.1      .1       0  4540.6     .14       0
    4967     .04       0  5040.4     .14       0  6030.9     .06       0
#XS Ineff= 2 , 0
       0    3170    82.2               0
Permanent Ineff=
       F       F
Bank Sta=4967,5040.4
XS Rating Curve= 0 ,0
Exp/Cntr=0.3,0.1

Type RM Length L Ch R = 1 ,36087.9 ,609.1,993.6,1202
BEGIN DESCRIPTION:
Cross Section 36087.9
END DESCRIPTION:
XS GIS Cut Line= 6
      3146032.38     13926566.31      3145702.85     13925930.35
      3144908.62     13924730.31      3144028.72      13923466.7
      3143578.19     13923133.19      3142601.07     13922589.05
#Sta/Elev= 30
   948.2   82.53  2154.5   79.88  2204.5    74.1  2244.5   78.71  2534.5   78.49
  2594.5   72.01  2674.5   77.33  2834.5   77.71  2904.5   81.06  3153.5   81.29
  3235.1   78.35  3863.5   77.65  3923.5   75.35  3973.5   79.33  4163.5   79.18
  4233.5   75.67  4540.6   76.39  4733.3   76.12  4813.3   78.76  4923.3   76.02
  4977.8   77.27  4994.7   65.69  5000.3   64.54  5015.6   67.42  5028.6   76.97
  5063.3   79.24  5313.8    76.3  6030.9   78.93  6143.8    82.9  6322.3   82.34
#Mann= 6 , 1 , 0
   948.2      .2       0  3235.1      .1       0  4540.6     .14       0
  4977.8     .04       0  5028.6     .14       0  6030.9     .06       0
#XS Ineff= 2 , 0
       0    3140    81.6               0
Permanent Ineff=
       F       F
Bank Sta=4977.8,5028.6
XS Rating Curve= 0 ,0
Exp/Cntr=0.3,0.1

Type RM Length L Ch R = 1 ,35094.3 ,932.1,934.3,957.6
BEGIN DESCRIPTION:
Cross Section 35094.3
END DESCRIPTION:
XS GIS Cut Line= 6
      3146172.52     13926623.64       3145778.2      13925884.3
      3144963.77       13924750.      3144707.44     13923501.81
      3144607.97     13922864.05      3144531.55     13922380.06
#Sta/Elev= 30
   901.7   82.73  2159.6   79.83  2229.6   73.85  2239.6   74.15  2269.6   79.61
  2569.6   77.71  2709.6   79.37  2749.6   76.01  2769.6   72.11  2879.6   78.32
  2949.6    77.6  3009.6   80.95  3079.6   80.58    3146   82.61    3196   82.35
  3220.1   80.21    3236      78    4076   75.84    4276   77.11    4346   75.02
  4540.3   76.24  4650.3   74.63  4930.3   74.74 4975.61   72.59 4988.01   70.03
 4996.61   64.69 5000.61   64.01 5025.01   75.47  5465.7   76.86  5545.7   81.72
#Mann= 4 , 1 , 0
   901.7      .2       0  3220.1      .1       0 4975.61     .04       0
 5025.01     .14       0
#XS Ineff= 2 , 0
       0    3200    83.4               0
Permanent Ineff=
       F       F
Bank Sta=4975.61,5025.01
XS Rating Curve= 0 ,0
Exp/Cntr=0.3,0.1

Type RM Length L Ch R = 1 ,34160.0 ,1002.5,875.6,556.8
BEGIN DESCRIPTION:
Cross Section 34160.0
END DESCRIPTION:
XS GIS Cut Line= 6
       3147250.9     13925189.83      3146045.91     13924439.04
      3145542.88     13922828.94      3145526.58     13922752.88
      3145505.29     13922637.91      3144618.41     13920760.12
#Sta/Elev= 30
  1839.1   83.05  1919.1   80.44  2039.1   78.99  2139.1   80.29  2648.8   78.98
  2799.1   79.42  3069.1   76.91  3159.1   77.37  3219.1   75.65  3538.8   76.17
  3890.8   74.84  3928.8   73.51  4150.1   75.17  4228.8   76.39  4258.8   74.99
  4959.7    73.9  4989.9   64.87  4994.9   62.31  5007.9   63.47  5024.4   72.85
  5160.4    75.7  5990.4   75.47  6010.4      77  6250.4   78.17  6300.4   79.59
  6510.4   78.08  6840.4   79.18  7044.1   78.35    7217   77.65  7217.1      80
#Mann= 7 , 1 , 0
  1839.1      .2       0  2648.8     .14       0  3890.8      .1       0
  4150.1     .14       0  4959.7     .04       0  5024.4      .1       0
  7044.1      .2       0
#XS Ineff= 2 , 0
       0    4314      80    5689       0      80
Permanent Ineff=
       F       F
Bank Sta=4959.7,5024.4
XS Rating Curve= 0 ,0
Exp/Cntr=0.3,0.1

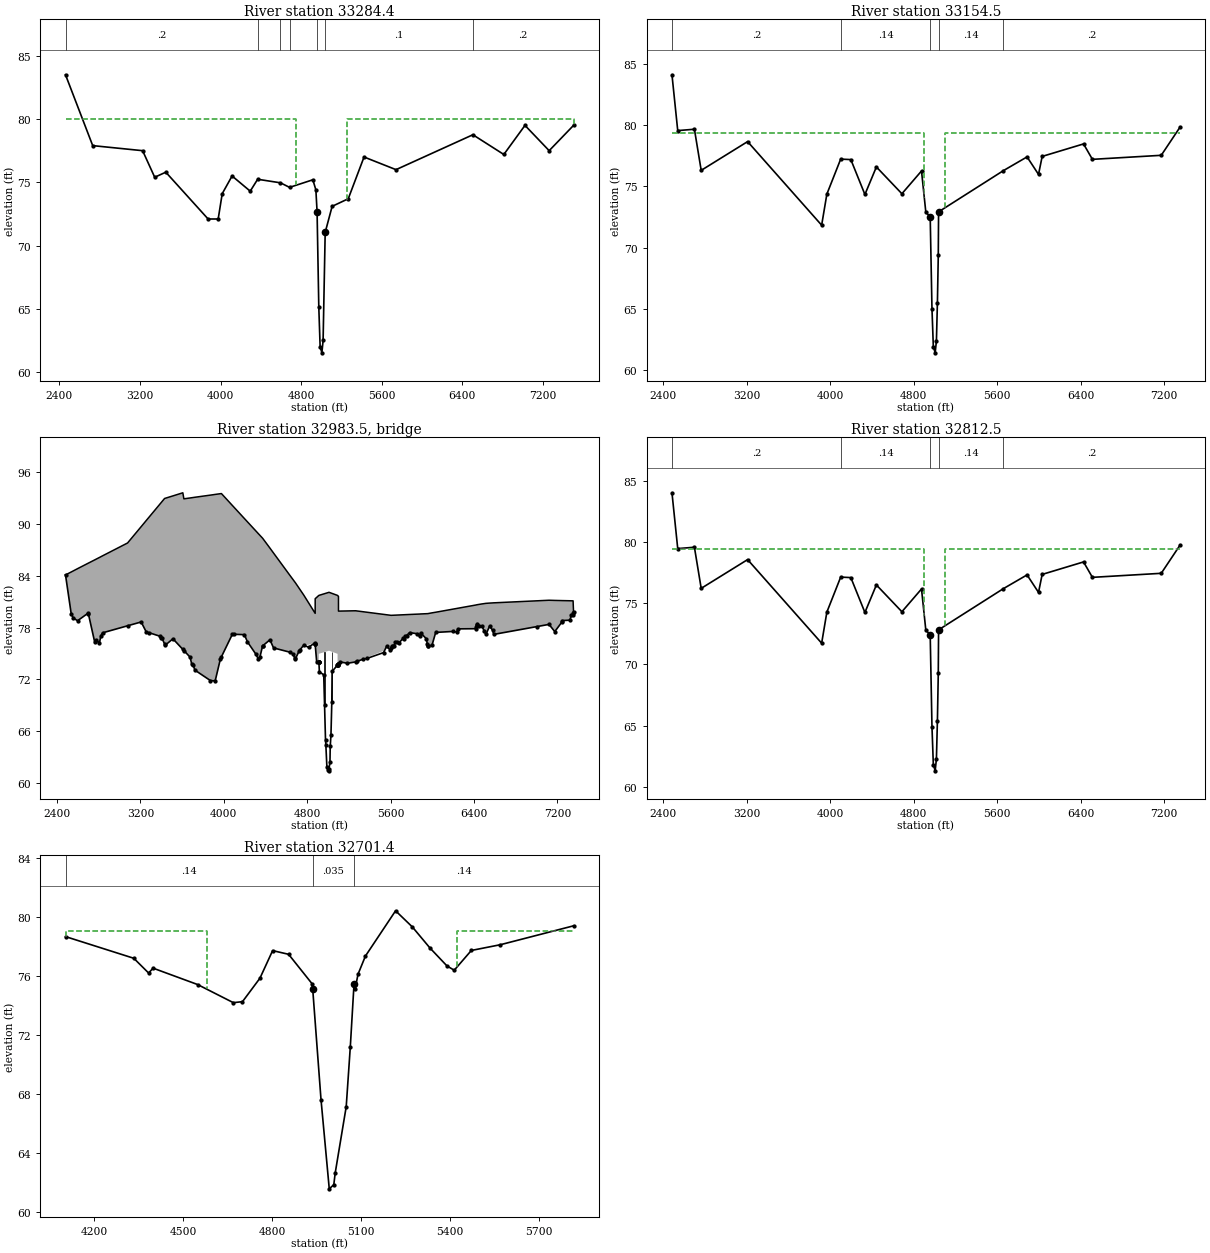
Type RM Length L Ch R = 1 ,33284.4 ,7.9,129.9,332.3
BEGIN DESCRIPTION:
Cross Section 33284.4 - Interpolated
END DESCRIPTION:
XS GIS Cut Line= 6
      3147111.67     13924972.67        3147002.     13924634.74
      3146488.94     13922816.07      3146382.32     13922575.32
       3146133.7     13922399.28      3144755.27     13920647.28
#Sta/Elev= 30
  2461.7    83.5  2731.7    77.9    3227    77.5    3347    75.4    3457    75.8
    3877    72.1    3977    72.1    4017    74.1  4114.9    75.5  4294.9    74.3
  4368.8   75.24  4595.2   74.96  4685.5    74.6  4916.6    75.2  4946.6    74.4
 4958.58   72.66 4975.58   65.14 4988.68   62.02 5006.28   61.52 5018.28    62.5
 5038.98   71.04  5107.9    73.1  5267.9    73.7  5424.6      77  5741.9      76
    6505   78.76  6811.9    77.2  7021.9    79.5  7261.9    77.5  7503.9    79.5
#Mann= 7 , 1 , 0
  2461.7      .2       0  4368.8      .1       0  4595.2     .14       0
  4685.5      .1       0 4958.58    .035       0 5038.98      .1       0
    6505      .2       0
#XS Ineff= 2 , 0
       0    4752      80    5251       0      80
Permanent Ineff=
       F       F
Bank Sta=4958.58,5038.98
XS Rating Curve= 0 ,0
Exp/Cntr=0.5,0.3

Type RM Length L Ch R = 1 ,33154.5 ,342,342,342
BEGIN DESCRIPTION:
Upstream Section of Bridge/Culvert/Weir
END DESCRIPTION:
XS GIS Cut Line= 6
     3147185.845    13924883.385     3146708.555    13923284.665
     3146425.055    13922404.825     3146323.525    13922211.975
     3146143.795    13921915.655     3145115.395    13920544.475
#Sta/Elev= 30
  2482.6   84.12  2537.8   79.56  2697.8   79.67  2762.8   76.31  3207.8   78.66
  3917.8   71.83  3967.8   74.37  4100.3   77.23  4197.6   77.19  4332.6   74.34
  4442.6   76.59  4687.3    74.4  4875.3   76.26    4917   72.87  4958.6   72.54
  4975.6   65.02  4988.7    61.9  5006.3    61.4  5018.3   62.38  5027.8    65.5
  5036.1   69.36    5039   72.92  5660.9   76.29  5887.3   77.41  5997.3   75.98
  6032.3   77.45    6429   78.47    6514   77.21    7174   77.54    7354   79.84
#Mann= 5 , 1 , 0
  2482.6      .2       0  4100.3     .14       0  4958.6    .035       0
    5039     .14       0  5660.9      .2       0
#XS Ineff= 2 , 0
       0    4902    79.4    5101       0    79.4
Permanent Ineff=
       F       F
Bank Sta=4958.6,5039
XS Rating Curve= 0 ,0
Exp/Cntr=0.5,0.3

Type RM Length L Ch R = 3 ,32983.5 ,,,
BEGIN DESCRIPTION:
HWY 59 & ACCESS ROADS
Structure ID: P30-18
END DESCRIPTION:
Bridge Culvert--1,0,-1,-1, 0
Deck Dist Width WeirC Skew NumUp NumDn MinLoCord MaxHiCord MaxSubmerge Is_Ogee
10,322,2.6,0, 60, 60, , , 0.95, 0, 1,1,,
  2482.6  2537.8  2597.8  2697.8  2762.8  2807.8  2837.8  3077.6  3207.8  3257.8
  3392.8  3432.6  3512.8  3607.6  3617.6  3677.8  3722.8  3872.8  3917.8  3977.6
  4082.6  4197.6  4332.6  4372.6  4442.6  4477.6  4633.4  4687.3  4767.1 4876.59
  4876.7  4890.8 4911.51  4911.6  5009.4 5091.09  5091.2    5100 5100.11  5263.9
  5604.7  5782.3  5877.3  5887.3  5942.3  5957.3  5997.3  6032.3    6414    6429
    6474    6514    6549    6589    7119    7174    7244    7319  7349.6    7354
   84.11   84.45   84.83   85.45   85.85   86.13   86.32   87.81    89.7   90.43
   92.39   92.97   93.27   93.63   92.93   93.03   93.11   93.36   93.44   93.54
   92.16   90.65   88.88   88.36   87.22   86.64   84.07   83.19   81.77   79.65
   81.35    81.5   81.73   81.73   82.09   81.73   81.73   81.61   79.91   79.95
   79.42   79.52   79.57   79.58   79.61   79.62   79.71   79.78   80.61   80.65
   80.74   80.81   80.84   80.87   81.17   81.15   81.13   81.11    81.1   79.83
   84.11   79.55   78.79   79.66    76.3   76.22   77.39   78.21   78.65   77.47
   76.98   76.09    76.7   75.47   75.34   74.56   73.07   71.85   71.82   74.61
   77.23   77.18   74.33   75.88   76.58   75.64   75.15   74.39   75.96   76.07
   76.05   74.05   73.97   74.96   75.32   74.96   73.65   73.79   73.79   74.02
   75.63   77.42   76.97    77.4    76.7   75.86   75.97   77.44   77.87   78.46
   78.19    77.2   78.17   77.21   78.37   77.53   78.81   78.86   79.69   79.83
  2482.6  2537.8  2597.8  2697.8  2762.8  2807.8  2837.8  3077.6  3207.8  3257.8
  3392.8  3432.6  3512.8  3607.6  3617.6  3677.8  3722.8  3872.8  3917.8  3977.6
  4082.6  4197.6  4332.6  4372.6  4442.6  4477.6  4633.4  4687.3  4767.1 4876.59
  4876.7  4890.8 4911.51  4911.6  5009.4 5091.09  5091.2    5100 5100.11  5263.9
  5604.7  5782.3  5877.3  5887.3  5942.3  5957.3  5997.3  6032.3    6414    6429
    6474    6514    6549    6589    7119    7174    7244    7319  7349.6    7354
   84.11   84.45   84.83   85.45   85.85   86.13   86.32   87.81    89.7   90.43
   92.39   92.97   93.27   93.63   92.93   93.03   93.11   93.36   93.44   93.54
   92.16   90.65   88.88   88.36   87.22   86.64   84.07   83.19   81.77   79.65
   81.35    81.5   81.73   81.73   82.09   81.73   81.73   81.61   79.91   79.95
   79.42   79.52   79.57   79.58   79.61   79.62   79.71   79.78   80.61   80.65
   80.74   80.81   80.84   80.87   81.17   81.15   81.13   81.11    81.1   79.83
   84.01   79.45   78.69   79.56    76.2   76.12   77.29   78.11   78.55   77.37
   76.88   75.99    76.6   75.37   75.24   74.46   72.97   71.75   71.72   74.51
   77.13   77.08   74.23   75.78   76.48   75.54   75.05   74.29   75.86   75.97
   75.95   73.95   73.87   74.86   75.22   74.86   73.55   73.69   73.69   73.92
   75.53   77.32   76.87    77.3    76.6   75.76   75.87   77.34   77.77   78.36
   78.09    77.1   78.07   77.11   78.27   77.43   78.71   78.76   79.59   79.73
Pier Skew, UpSta & Num, DnSta & Num=  ,4966.1, 2 ,4966.1, 2 , 0 , 0 , 0 ,,
     3.3     3.3
   67.35   76.17
     3.3     3.3
   67.25   76.07
Pier Skew, UpSta & Num, DnSta & Num=  ,5036, 2 ,5036, 2 , 0 , 0 , 0 ,,
     3.3     3.3
   67.54   76.21
     3.3     3.3
   67.44   76.11
Abutment Skew #Up #Dn= , 2 , 2
  5089.6 5091.29
   73.63   74.96
  5089.6 5091.29
   73.53   74.86
BR Coef= 1 , 1 , 0 ,1.25, 0 ,,,0.8,0,2,0,
WSPro=,,,, 1 ,,,, 0 ,,,, 0 ,,,,-1 ,-1 ,-1 , 0 , 0 , 0 , 0 , 0
BR U #Sta/Elev= 136
  2482.6   84.11  2537.8   79.55  2557.8   79.12  2597.8   78.79  2697.8   79.66
  2702.8   79.55  2762.8    76.3  2777.8   76.53  2807.8   76.22  2822.8   77.07
  2837.8   77.39  3077.6   78.21  3207.8   78.65  3257.8   77.47  3287.8   77.39
  3392.8   76.98  3397.8   76.82  3407.8   76.77  3432.6   76.09  3437.8   75.95
  3512.8    76.7  3607.6   75.47  3617.6   75.34  3677.8   74.56  3692.8   73.76
  3707.8   73.63  3722.8   73.07  3872.8   71.85  3917.8   71.82  3967.8   74.36
  3977.6   74.61  4082.6   77.23  4100.3   77.22  4197.6   77.18  4227.6   76.34
  4307.6   74.92  4332.6   74.33  4347.6   74.63  4372.6   75.88  4376.1   75.91
  4442.6   76.58  4477.6   75.64  4633.4   75.15  4663.4   74.94  4678.4   74.53
  4687.3   74.39  4725.1   75.34  4730.9   75.43  4767.1   75.96  4813.8   75.72
  4875.3   76.25 4876.59   76.07  4876.7   76.05 4876.81   76.04  4890.8   74.05
  4911.4   73.97 4911.51   73.97  4911.6   73.97  4912.2   73.97  4912.3   73.97
    4917   72.86  4958.6   72.53  4966.1   69.05  4975.6   65.01  4979.1   64.36
  4988.7   61.89    4997   61.52  5006.3   61.39  5009.4   61.64  5018.3   62.37
    5021   64.25  5027.8   65.49  5036.1   69.35    5039   72.91  5089.5   73.63
  5089.6   73.63 5091.09   73.65  5091.2   73.65  5091.3   73.66 5099.89   73.78
    5100   73.79 5100.11   73.79  5115.5   74.02  5185.9   73.86  5263.9   74.02
  5281.9    74.1  5330.6   74.31  5377.3   74.44  5532.3    75.1  5562.3   75.84
  5597.3   75.38  5604.7   75.63  5612.3   75.89  5626.7   75.86  5631.7   75.81
  5646.7   76.37  5660.9   76.28  5676.7   76.18  5721.7   76.78  5731.7   76.65
  5736.7   76.98  5752.3   77.07  5782.3   77.42  5857.3   77.28  5877.3   76.97
  5887.3    77.4  5942.3    76.7  5952.3   76.05  5957.2   75.86  5957.3   75.86
  5997.3   75.97  6032.3   77.44    6194   77.55    6234    77.5    6244   77.85
    6414   77.87    6419   78.02    6424   78.33    6429   78.46    6444    78.2
    6474   78.19  6499.6   77.56    6514    77.2    6549   78.17    6579   77.67
    6589   77.21  6999.6   78.11    7119   78.37    7174   77.53    7239   78.59
    7244   78.81    7319   78.86    7334   79.45    7344   79.51  7349.6   79.69
    7354   79.83
BR U #Mann= 5
  2482.6      .2  4100.3     .14  4958.6    .035    5039     .14  5660.9      .2
BR U Banks=4958.6,5039
BR D #Sta/Elev= 136
  2482.6   84.01  2537.8   79.45  2557.8   79.02  2597.8   78.69  2697.8   79.56
  2702.8   79.45  2762.8    76.2  2777.8   76.43  2807.8   76.12  2822.8   76.97
  2837.8   77.29  3077.6   78.11  3207.8   78.55  3257.8   77.37  3287.8   77.29
  3392.8   76.88  3397.8   76.72  3407.8   76.67  3432.6   75.99  3437.8   75.85
  3512.8    76.6  3607.6   75.37  3617.6   75.24  3677.8   74.46  3692.8   73.66
  3707.8   73.53  3722.8   72.97  3872.8   71.75  3917.8   71.72  3967.8   74.26
  3977.6   74.51  4082.6   77.13  4100.3   77.12  4197.6   77.08  4227.6   76.24
  4307.6   74.82  4332.6   74.23  4347.6   74.53  4372.6   75.78  4376.1   75.81
  4442.6   76.48  4477.6   75.54  4633.4   75.05  4663.4   74.84  4678.4   74.43
  4687.3   74.29  4725.1   75.24  4730.9   75.33  4767.1   75.86  4813.8   75.62
  4875.3   76.15 4876.59   75.97  4876.7   75.95 4876.81   75.94  4890.8   73.95
  4911.4   73.87 4911.51   73.87  4911.6   73.87  4912.2   73.87  4912.3   73.87
    4917   72.76  4958.6   72.43  4966.1   68.95  4975.6   64.91  4979.1   64.26
  4988.7   61.79    4997   61.42  5006.3   61.29  5009.4   61.54  5018.3   62.27
    5021   64.15  5027.8   65.39  5036.1   69.25    5039   72.81  5089.5   73.53
  5089.6   73.53 5091.09   73.55  5091.2   73.55  5091.3   73.56 5099.89   73.68
    5100   73.69 5100.11   73.69  5115.5   73.92  5185.9   73.76  5263.9   73.92
  5281.9      74  5330.6   74.21  5377.3   74.34  5532.3      75  5562.3   75.74
  5597.3   75.28  5604.7   75.53  5612.3   75.79  5626.7   75.76  5631.7   75.71
  5646.7   76.27  5660.9   76.18  5676.7   76.08  5721.7   76.68  5731.7   76.55
  5736.7   76.88  5752.3   76.97  5782.3   77.32  5857.3   77.18  5877.3   76.87
  5887.3    77.3  5942.3    76.6  5952.3   75.95  5957.2   75.76  5957.3   75.76
  5997.3   75.87  6032.3   77.34    6194   77.45    6234    77.4    6244   77.75
    6414   77.77    6419   77.92    6424   78.23    6429   78.36    6444    78.1
    6474   78.09  6499.6   77.46    6514    77.1    6549   78.07    6579   77.57
    6589   77.11  6999.6   78.01    7119   78.27    7174   77.43    7239   78.49
    7244   78.71    7319   78.76    7334   79.35    7344   79.41  7349.6   79.59
    7354   79.73
BR D #Mann= 5
  2482.6      .2  4100.3     .14  4958.6    .035    5039     .14  5660.9      .2
BR D Banks=4958.6,5039
BC Design=,, 0 ,, 0 ,,,,,,
BC HTab HWMax=84.12
BC Use User HTab Curves=0
BC User HTab FreeFlow(D)= 0

Type RM Length L Ch R = 1 ,32812.5 ,111.1,111.1,111.1
BEGIN DESCRIPTION:
Downstream Section of Bridge/Culvert/Weir
END DESCRIPTION:
XS GIS Cut Line= 6
     3147458.139     13924701.39     3146980.849     13923102.67
     3146697.349     13922222.83     3146595.819     13922029.98
     3146416.089     13921733.66     3145387.689     13920362.48
#Sta/Elev= 30
  2482.6   84.03  2537.8   79.47  2697.8   79.58  2762.8   76.22  3207.8   78.57
  3917.8   71.74  3967.8   74.28  4100.3   77.14  4197.6    77.1  4332.6   74.25
  4442.6    76.5  4687.3   74.31  4875.3   76.17    4917   72.78  4958.6   72.45
  4975.6   64.93  4988.7   61.81  5006.3   61.31  5018.3   62.29  5027.8   65.41
  5036.1   69.27    5039   72.83  5660.9    76.2  5887.3   77.32  5997.3   75.89
  6032.3   77.36    6429   78.38    6514   77.12    7174   77.45    7354   79.75
#Mann= 5 , 1 , 0
  2482.6      .2       0  4100.3     .14       0  4958.6    .035       0
    5039     .14       0  5660.9      .2       0
#XS Ineff= 2 , 0
       0    4902    79.4    5101       0    79.4
Permanent Ineff=
       F       F
Bank Sta=4958.6,5039
XS Rating Curve= 0 ,0
Exp/Cntr=0.5,0.3

Type RM Length L Ch R = 1 ,32701.4 ,80,80,80
BEGIN DESCRIPTION:
Upstream Section of Bridge/Culvert/Weir
END DESCRIPTION:
XS GIS Cut Line= 6
      3147284.41     13922811.71       3147099.8     13922605.75
      3146939.98     13922554.04      3146872.44     13922388.94
      3146728.65     13922101.35      3146285.48     13921475.45
#Sta/Elev= 30
  4104.4   78.65  4334.4   77.18  4384.4   76.18  4399.4   76.51  4549.4    75.4
  4669.9   74.17  4700.6   74.24  4759.4   75.83  4802.1    77.7  4855.9   77.45
  4935.5   75.44    4937   75.13  4965.1    67.6  4992.9   61.55  5008.2   61.83
  5012.8   62.61    5050   67.12  5063.8   71.18  5076.3   75.43  5079.8   75.08
  5089.8    76.1  5114.7   77.33  5216.3    80.4    5273    79.3    5332   77.88
  5389.5   76.66  5413.9   76.37  5471.5   77.71  5569.5    78.1  5815.8   79.38
#Mann= 3 , 1 , 0
  4104.4     .14       0    4937    .035       0  5076.3     .14       0
#XS Ineff= 2 , 0
       0    4580      79    5423       0      79
Permanent Ineff=
       F       F
Bank Sta=4937,5076.3
XS Rating Curve= 0 ,0
Exp/Cntr=0.5,0.3