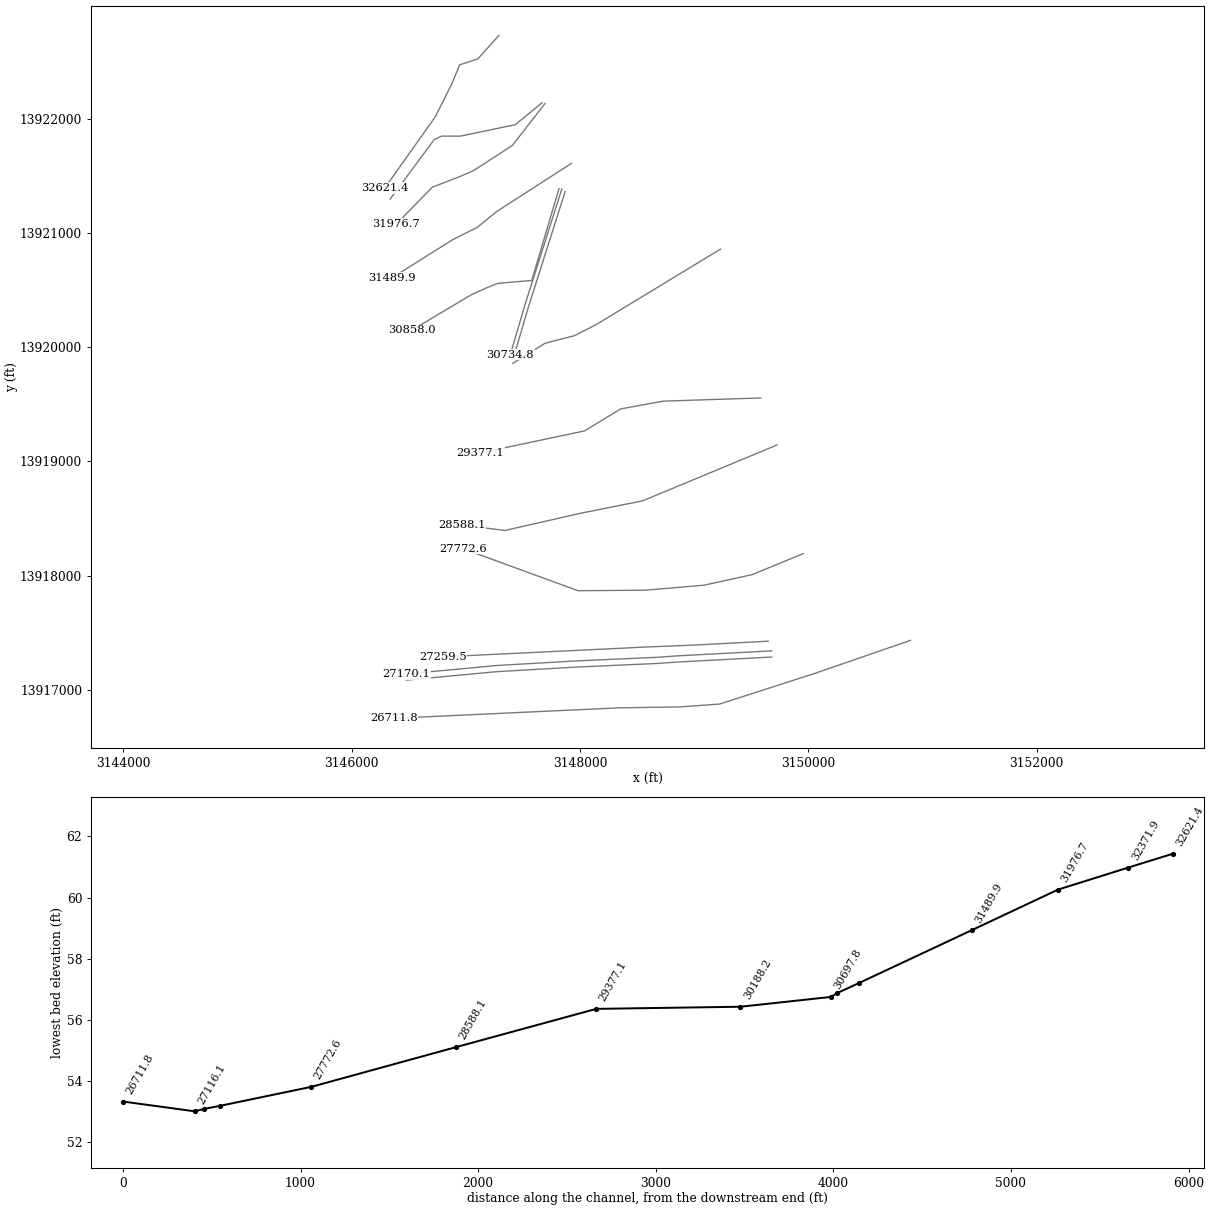
HEC-RAS study P130-00-00.prj: P130-00-00

--- P130-00-00.g01 (geometry) --- (continued)

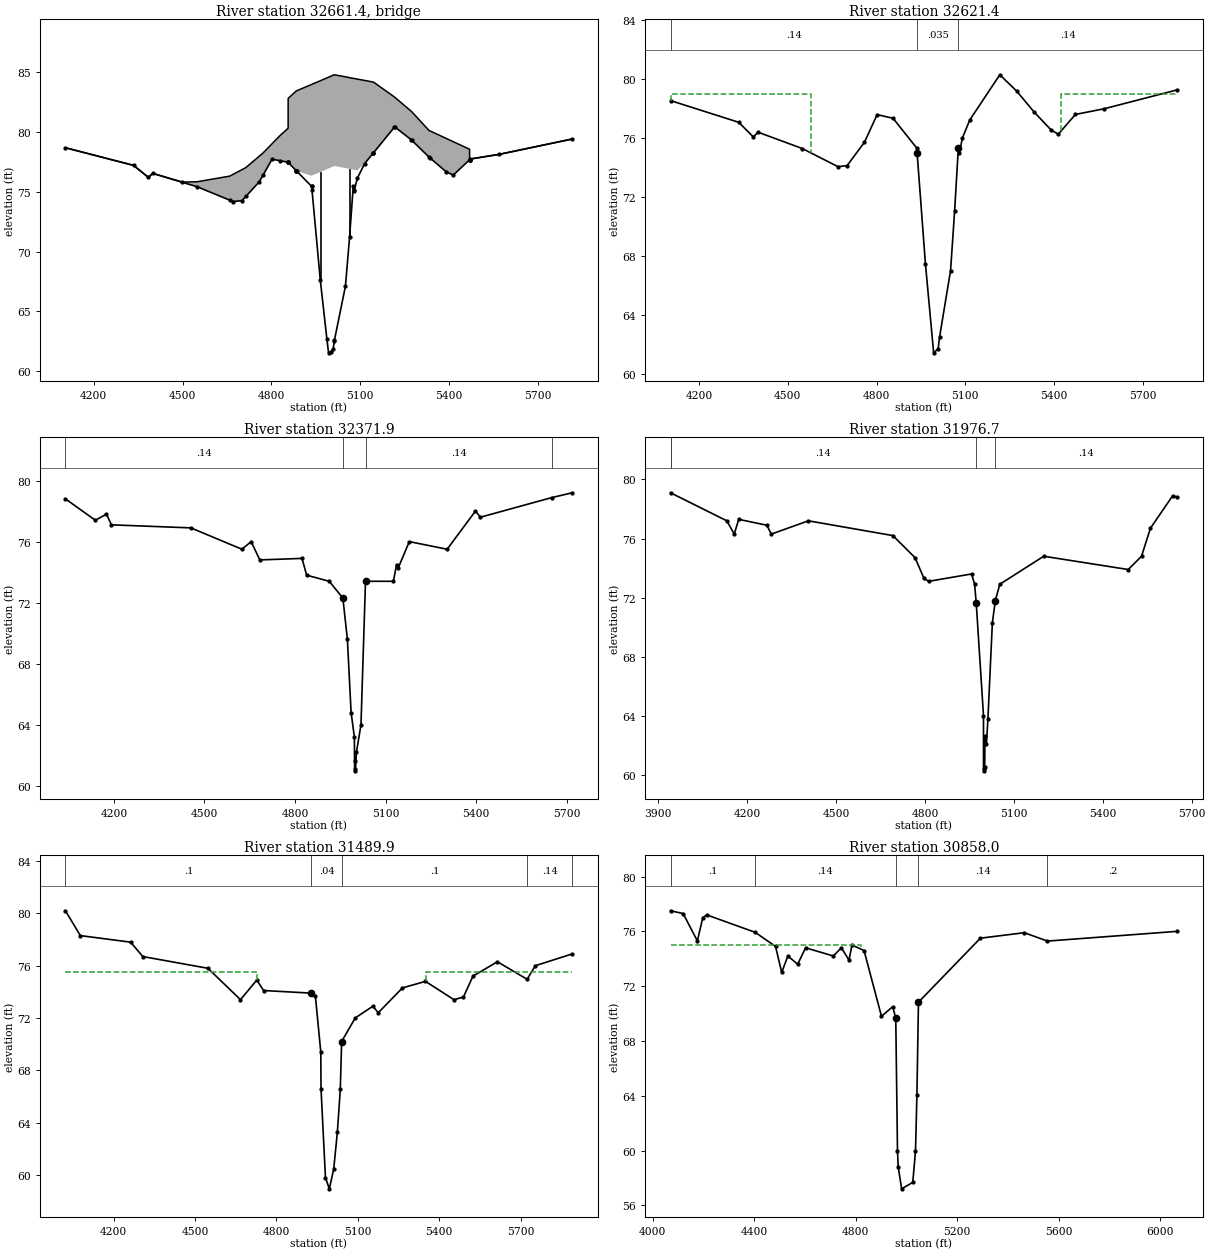
Type RM Length L Ch R = 3 ,32661.4 ,,,
BEGIN DESCRIPTION:
HIGHWAY 59 FRONTAGE ROAD
Structure ID: P30-16
END DESCRIPTION:
Bridge Culvert--1,0,-1,-1, 0
Deck Dist Width WeirC Skew NumUp NumDn MinLoCord MaxHiCord MaxSubmerge Is_Ogee
10,60,2.6,0, 57, 57, , , 0.95, 0, 1,1,,
  4104.4  4334.4  4384.4  4399.4  4499.5  4549.4  4659.4  4669.9  4700.6  4713.5
  4759.4  4771.3  4802.1  4829.8  4855.9 4856.39  4856.5 4856.61  4884.4 4884.51
  4884.6  4884.7  4935.4  4935.5    4937  4965.1  4987.2  4992.9  5000.1  5008.2
  5012.2  5012.8    5050  5063.8  5076.3  5079.7  5079.8  5089.8  5114.7 5144.39
  5144.5  5144.6  5215.3  5216.3    5273  5274.2    5332  5333.8  5389.5  5413.9
 5469.09  5469.2 5469.31  5469.5  5471.5  5569.5  5815.8
   78.66   77.19   76.19   76.52   75.79   75.82   76.29   76.43   76.83      77
   77.96   78.21   78.99   79.69   80.27   80.28   82.78   82.78    83.4    83.4
    83.4    83.4   83.93   83.93   83.95   84.24   84.48   84.54   84.61    84.7
   84.74   84.74   84.57    84.5   84.44   84.43   84.43   84.38   84.27   84.13
   84.13   84.13   82.89   82.87   81.68   81.65    80.1   80.08   79.44   79.16
   78.53   78.53   77.68   77.68   77.72   78.11   79.39
   78.65   77.18   76.18   76.51   75.77    75.4   74.28   74.17   74.24   74.59
   75.83   76.35    77.7   77.57   77.45   77.44   77.43   77.43   76.73   76.73
   76.73   76.72   76.32   76.32   76.34   76.63   76.87   76.93      77   77.09
   77.13   77.13   76.96   76.89   76.83   76.82   76.82   76.77   77.33   78.23
   78.23   78.23   80.37    80.4    79.3   79.27   77.88   77.84   76.66   76.37
   77.65   77.66   77.66   77.66   77.71    78.1   79.38
  4104.4  4334.4  4384.4  4399.4  4499.5  4549.4  4659.4  4669.9  4700.6  4713.5
  4759.4  4771.3  4802.1  4829.8  4855.9 4856.39  4856.5 4856.61  4884.4 4884.51
  4884.6  4884.7  4935.4  4935.5    4937  4965.1  4987.2  4992.9  5000.1  5008.2
  5012.2  5012.8    5050  5063.8  5076.3  5079.7  5079.8  5089.8  5114.7 5144.39
  5144.5  5144.6  5215.3  5216.3    5273  5274.2    5332  5333.8  5389.5  5413.9
 5469.09  5469.2 5469.31  5469.5  5471.5  5569.5  5815.8
   78.66   77.19   76.19   76.52   75.79   75.82   76.29   76.43   76.83      77
   77.96   78.21   78.99   79.69   80.27   80.28   82.78   82.78    83.4    83.4
    83.4    83.4   83.93   83.93   83.95   84.24   84.48   84.54   84.61    84.7
   84.74   84.74   84.57    84.5   84.44   84.43   84.43   84.38   84.27   84.13
   84.13   84.13   82.89   82.87   81.68   81.65    80.1   80.08   79.44   79.16
   78.53   78.53   77.68   77.68   77.72   78.11   79.39
   78.55   77.08   76.08   76.41   75.67    75.3   74.18   74.07   74.14   74.49
   75.73   76.25    77.6   77.47   77.35   77.34   77.33   77.33   76.63   76.63
   76.63   76.62   76.22   76.22   76.24   76.53   76.77   76.83    76.9   76.99
   77.03   77.03   76.86   76.79   76.73   76.72   76.72   76.67   77.23   78.13
   78.13   78.13   80.27    80.3    79.2   79.17   77.78   77.74   76.56   76.27
   77.55   77.56   77.56   77.56   77.61      78   79.28
Pier Skew, UpSta & Num, DnSta & Num=  ,4965.1, 2 ,4965.1, 2 , 0 , 0 , 0 ,,
       3       3
   66.27   77.65
       3       3
   66.17   77.55
Pier Skew, UpSta & Num, DnSta & Num=  ,5063.8, 2 ,5063.8, 2 , 0 , 0 , 0 ,,
       3       3
   69.74    77.9
       3       3
   69.64    77.8
Abutment Skew #Up #Dn= , 2 , 2
  4884.4  4935.5
   76.73   75.44
  4884.4  4935.5
   76.63   75.34
Abutment Skew #Up #Dn= , 2 , 2
  5079.8 5144.59
   75.08   78.23
  5079.8 5144.59
   74.98   78.13
BR Coef= 1 , 1 , 0 ,1.25, 0 ,,,0.8,0,2,0,
WSPro=,,,, 1 ,,,, 0 ,,,, 0 ,,,,-1 ,-1 ,-1 , 0 , 0 , 0 , 0 , 0
BR U #Sta/Elev= 57
  4104.4   78.65  4334.4   77.18  4384.4   76.18  4399.4   76.51  4499.5   75.77
  4549.4    75.4  4659.4   74.28  4669.9   74.17  4700.6   74.24  4713.5   74.59
  4759.4   75.83  4771.3   76.35  4802.1    77.7  4829.8   77.57  4855.9   77.45
 4856.39   77.44  4856.5   77.43 4856.61   77.43  4884.4   76.73 4884.51   76.73
  4884.6   76.73  4884.7   76.72  4935.4   75.44  4935.5   75.44    4937   75.13
  4965.1    67.6  4987.2   62.72  4992.9   61.55  5000.1   61.66  5008.2   61.83
  5012.2   62.51  5012.8   62.61    5050   67.12  5063.8   71.18  5076.3   75.43
  5079.7   75.09  5079.8   75.08  5089.8    76.1  5114.7   77.33 5144.39   78.23
  5144.5   78.23  5144.6   78.23  5215.3   80.37  5216.3    80.4    5273    79.3
  5274.2   79.27    5332   77.88  5333.8   77.84  5389.5   76.66  5413.9   76.37
 5469.09   77.65  5469.2   77.66 5469.31   77.66  5469.5   77.66  5471.5   77.71
  5569.5    78.1  5815.8   79.38
BR U #Mann= 3
  4104.4     .14    4937    .035  5076.3     .14
BR U Banks=4937,5076.3
BR D #Sta/Elev= 57
  4104.4   78.55  4334.4   77.08  4384.4   76.08  4399.4   76.41  4499.5   75.67
  4549.4    75.3  4659.4   74.18  4669.9   74.07  4700.6   74.14  4713.5   74.49
  4759.4   75.73  4771.3   76.25  4802.1    77.6  4829.8   77.47  4855.9   77.35
 4856.39   77.34  4856.5   77.33 4856.61   77.33  4884.4   76.63 4884.51   76.63
  4884.6   76.63  4884.7   76.62  4935.4   75.34  4935.5   75.34    4937   75.03
  4965.1    67.5  4987.2   62.62  4992.9   61.45  5000.1   61.56  5008.2   61.73
  5012.2   62.41  5012.8   62.51    5050   67.02  5063.8   71.08  5076.3   75.33
  5079.7   74.99  5079.8   74.98  5089.8      76  5114.7   77.23 5144.39   78.13
  5144.5   78.13  5144.6   78.13  5215.3   80.27  5216.3    80.3    5273    79.2
  5274.2   79.17    5332   77.78  5333.8   77.74  5389.5   76.56  5413.9   76.27
 5469.09   77.55  5469.2   77.56 5469.31   77.56  5469.5   77.56  5471.5   77.61
  5569.5      78  5815.8   79.28
BR D #Mann= 3
  4104.4     .14    4937    .035  5076.3     .14
BR D Banks=4937,5076.3
BC Design=,, 0 ,, 0 ,,,,,,
BC HTab HWMax=80.4
BC Use User HTab Curves=0
BC User HTab FreeFlow(D)= 0

Type RM Length L Ch R = 1 ,32621.4 ,249.5,249.5,249.5
BEGIN DESCRIPTION:
Downstream Section of Bridge/Culvert/Weir
END DESCRIPTION:
XS GIS Cut Line= 6
      3147290.02     13922731.91      3147105.42     13922525.95
       3146945.6     13922474.24      3146878.06     13922309.14
      3146734.27     13922021.55      3146291.09     13921395.65
#Sta/Elev= 30
  4104.4   78.53  4334.4   77.06  4384.4   76.06  4399.4   76.39  4549.4   75.28
  4669.9   74.05  4700.6   74.12  4759.4   75.71  4802.1   77.58  4855.9   77.33
  4935.5   75.32    4937   75.01  4965.1   67.48  4992.9   61.43  5008.2   61.71
  5012.8   62.49    5050      67  5063.8   71.06  5076.3   75.31  5079.8   74.96
  5089.8   75.98  5114.7   77.21  5216.3   80.28    5273   79.18    5332   77.76
  5389.5   76.54  5413.9   76.25  5471.5   77.59  5569.5   77.98  5815.8   79.26
#Mann= 3 , 1 , 0
  4104.4     .14       0    4937    .035       0  5076.3     .14       0
#XS Ineff= 2 , 0
       0    4580      79    5423       0      79
Permanent Ineff=
       F       F
Bank Sta=4937,5076.3
XS Rating Curve= 0 ,0
Exp/Cntr=0.5,0.3

Type RM Length L Ch R = 1 ,32371.9 ,373.5,395.2,425.9
BEGIN DESCRIPTION:
Cross Section 32371.9 - Interpolated
END DESCRIPTION:
XS GIS Cut Line= 6
      3147667.85     13922141.63      3147432.77     13921949.59
      3146952.08     13921849.85      3146789.32     13921849.85
      3146724.52     13921820.61      3146336.56     13921297.71
#Sta/Elev= 30
  4039.5    78.8  4138.6    77.4  4175.5    77.8  4191.9    77.1    4455    76.9
  4624.2    75.5  4654.8      76  4683.4    74.8  4823.3    74.9  4838.6    73.8
  4913.6    73.4  4958.6    72.3  4973.6    69.6  4985.9    64.8  4996.7    63.2
  4997.3    61.6  4997.8   61.09  5000.2   60.98  5003.6    62.2  5018.6      64
  5033.6    73.4  5125.9    73.4  5136.6    74.5  5142.6    74.3  5178.7      76
  5304.1    75.5  5397.8      78  5414.4    77.6  5651.7   78.89  5718.5    79.2
#Mann= 4 , 1 , 0
  4039.5     .14       0  4958.6     .04       0  5033.6     .14       0
  5651.7      .2       0
Bank Sta=4958.6,5033.6
XS Rating Curve= 0 ,0
Exp/Cntr=0.3,0.1

Type RM Length L Ch R = 1 ,31976.7 ,456.8,486.8,498.1
BEGIN DESCRIPTION:
Cross Section 31976.7
END DESCRIPTION:
XS GIS Cut Line= 6
      3147694.07      13922135.7      3147408.52     13921768.57
      3147068.17     13921547.64      3146934.98     13921490.21
      3146707.76     13921403.19      3146392.51      13921081.1
#Sta/Elev= 30
  3941.8    79.1  4131.8    77.2  4156.8    76.3  4171.8    77.3  4266.8    76.9
  4281.8    76.3  4406.9    77.2  4691.9    76.2  4766.9    74.7  4796.9    73.3
  4812.7    73.1  4957.7    73.6  4967.7    72.9  4973.2   71.64  4997.7      64
  4997.8   60.37  5000.2   60.26  5001.8   60.51  5002.7    62.6  5007.7    62.1
  5012.7    63.8  5027.7    70.3  5037.7    71.8  5052.7    72.9    5201    74.8
    5486    73.9    5531    74.8    5561    76.7    5636    78.9  5651.7    78.8
#Mann= 4 , 1 , 0
  3941.8      .2       0  3941.8     .14       0  4973.2     .04       0
  5037.7     .14       0
Bank Sta=4973.2,5037.7
XS Rating Curve= 0 ,0
Exp/Cntr=0.3,0.1

Type RM Length L Ch R = 1 ,31489.9 ,681.7,631.9,580.8
BEGIN DESCRIPTION:
Cross Section 31489.9 - Interpolated
END DESCRIPTION:
XS GIS Cut Line= 5
      3147924.89     13921610.69      3147268.48     13921187.92
      3147100.63     13921050.59      3146887.01     13920943.77
      3146352.95     13920608.08
#Sta/Elev= 30
  4022.8    80.2  4077.8    78.3  4262.8    77.8  4307.8    76.7  4547.8    75.8
  4667.8    73.4  4727.8    74.9  4752.8    74.1  4928.6    73.9  4943.6    73.7
  4963.6    69.4  4964.5   66.58  4980.8   59.79  4995.1   58.93  5011.2   60.44
  5024.7   63.26  5035.5   66.53  5040.5    70.2  5090.5      72  5155.5    72.9
  5175.5    72.4  5264.3    74.3  5349.3    74.8  5454.3    73.4  5489.3    73.6
  5524.3    75.2  5614.3    76.3  5723.9   74.96  5754.3      76  5890.1    76.9
#Mann= 5 , 1 , 0
  4022.8      .1       0  4928.6     .04       0  5040.5      .1       0
  5723.9     .14       0  5890.1      .2       0
#XS Ineff= 2 , 0
       0    4728    75.5    5350       0    75.5
Permanent Ineff=
       F       F
Bank Sta=4928.6,5040.5
XS Rating Curve= 0 ,0
Exp/Cntr=0.3,0.1

Type RM Length L Ch R = 1 ,30858.0 ,123.2,123.2,123.2
BEGIN DESCRIPTION:
Cross Section 30858.0 - Interpolated
END DESCRIPTION:
XS GIS Cut Line= 6
      3147816.35     13921389.84      3147578.26     13920585.79
       3147282.4     13920560.28      3147174.68      13920517.8
      3147044.83     13920458.07      3146526.25     13920149.24
#Sta/Elev= 30
  4069.7    77.5  4119.3    77.3  4175.5    75.3  4196.9      77  4212.5    77.2
  4403.1   75.93  4483.7    74.9    4508      73  4532.3    74.2    4571    73.6
  4602.2    74.8  4711.6    74.2  4743.3    74.8  4773.3    73.9  4785.1      75
  4832.6    74.6  4901.4    69.8  4945.7    70.5  4957.7   69.66  4964.5      60
  4967.2   58.83  4980.8   57.21  5024.7   57.68  5035.5   59.95  5041.1   64.06
  5047.2   70.83  5291.4    75.5  5464.2    75.9  5555.9   75.29  6067.8      76
#Mann= 5 , 1 , 0
  4069.7      .1       0  4403.1     .14       0  4957.7    .035       0
  5047.2     .14       0  5555.9      .2       0
#XS Ineff= 2 , 0
       0    4820      75               0
Permanent Ineff=
       F       F
Bank Sta=4957.7,5047.2
XS Rating Curve= 0 ,0
Exp/Cntr=0.5,0.3

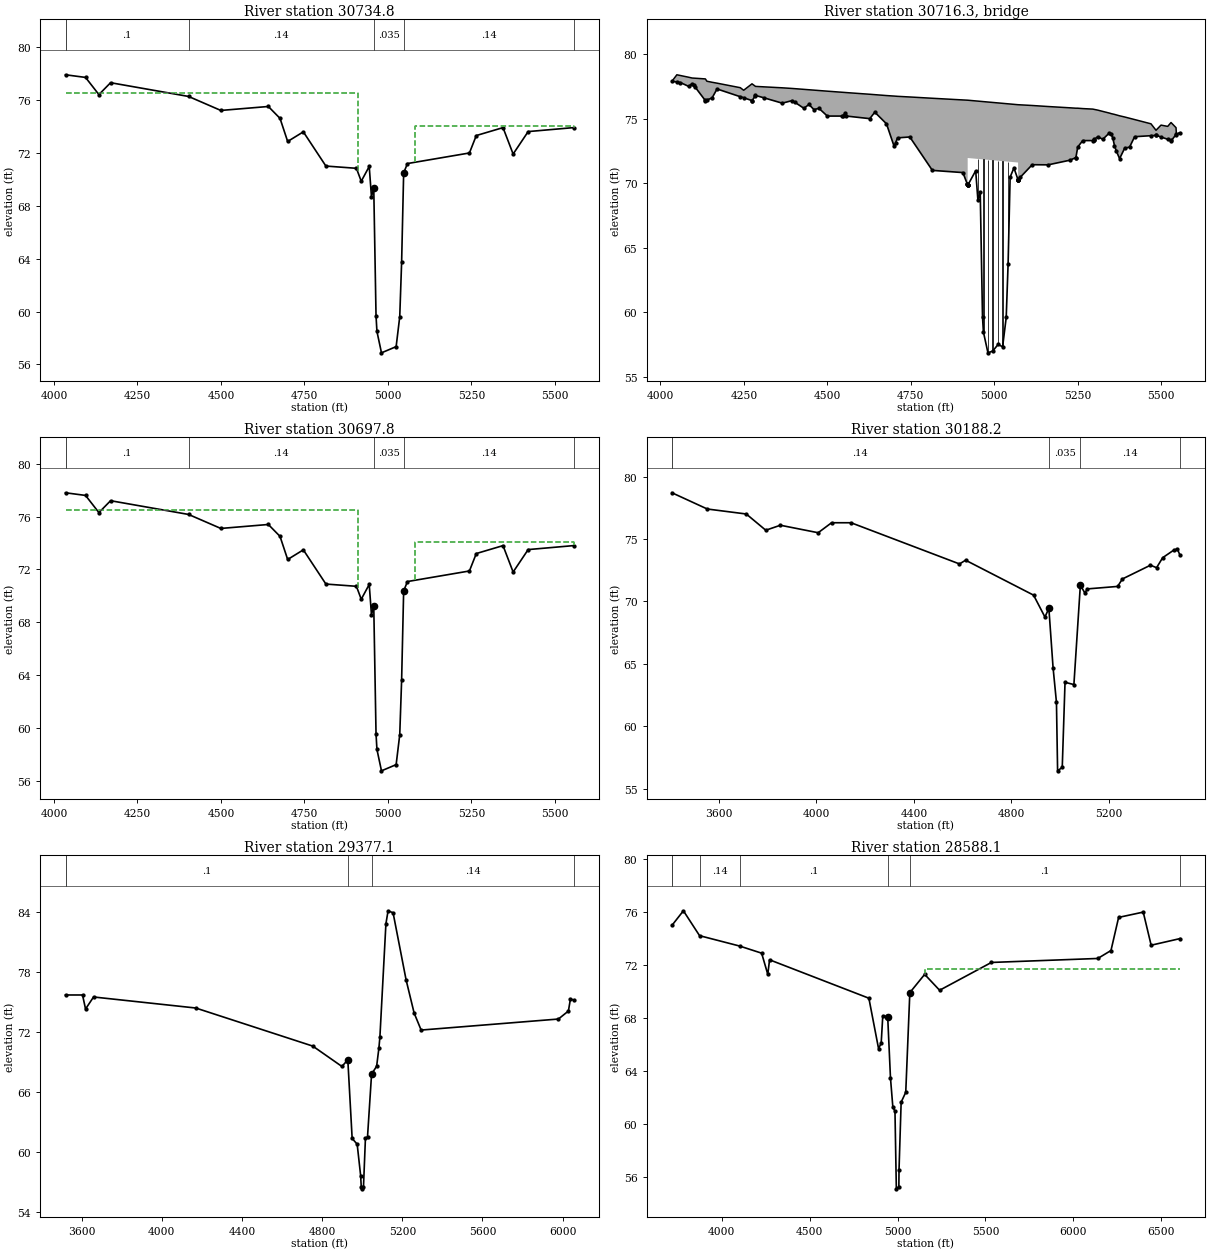
Type RM Length L Ch R = 1 ,30734.8 ,37,37,37
BEGIN DESCRIPTION:
Upstream Section of Bridge/Culvert/Weir
END DESCRIPTION:
XS GIS Cut Line= 3
      3147841.32     13921386.84      3147520.12     13920377.34
      3147389.71      13919934.3
#Sta/Elev= 30
  4034.7   77.93  4094.7   77.73  4134.7   76.43  4169.7   77.33  4403.1   76.29
  4499.8   75.23    4642   75.53    4677   74.63  4699.9   72.88  4746.8   73.61
  4814.4   71.02  4905.8   70.85  4920.2   69.87  4944.1   70.99  4950.8    68.7
  4957.7   69.33  4964.5   59.67  4967.2    58.5  4980.8   56.88  5024.7   57.35
  5035.5   59.62  5041.1   63.73  5047.2    70.5  5058.6   71.21  5244.1   72.01
  5264.7   73.33  5344.7   73.93    5375   71.93    5420   73.63  5555.9   73.93
#Mann= 6 , 1 , 0
  4034.7      .2       0  4034.7      .1       0  4403.1     .14       0
  4957.7    .035       0  5047.2     .14       0  5555.9      .2       0
#XS Ineff= 2 , 0
       0    4910   76.53    5080       0   74.06
Permanent Ineff=
       F       F
Bank Sta=4957.7,5047.2
XS Rating Curve= 0 ,0
Exp/Cntr=0.5,0.3

Type RM Length L Ch R = 3 ,30716.3 ,,,
BEGIN DESCRIPTION:
SOUTHERN PACIFIC RAILROAD
Structure ID: P30-14
END DESCRIPTION:
Bridge Culvert--1,0,-1,-1, 0
Deck Dist Width WeirC Skew NumUp NumDn MinLoCord MaxHiCord MaxSubmerge Is_Ogee
10,17,2.6,0, 60, 60, , , 0.95, 0, 1,1,,
  4034.7  4049.3  4084.7  4094.7  4134.7  4139.3  4154.7  4169.7  4239.3  4249.3
  4274.3  4284.8  4364.8  4394.8  4429.8  4444.8  4459.8  4474.8  4499.8    4547
    4552    4557    4627    4642    4677  4699.9  4710.1  4746.8  4814.4  4905.8
 4920.01  4920.1 5070.99  5071.1  5071.2  5113.4    5161  5226.4  5244.1  5249.7
  5264.7  5294.7  5309.7  5324.7  5344.7  5349.7  5354.7  5359.7    5375    5390
    5405    5420    5469    5484    5499    5519    5529    5544    5545  5555.9
    77.9    78.4   78.21   78.15   78.08    77.9   77.82   77.75    77.4    77.2
    77.7    77.5   77.39   77.34   77.27   77.24   77.21   77.18   77.13   77.04
   77.03   77.02   76.89   76.86   76.79   76.75   76.73   76.68   76.58   76.45
   76.43   76.43   76.08   76.08   76.08   76.02   75.94   75.84   75.81   75.81
   75.78   75.74   75.66   75.56   75.43   75.39   75.36   75.33   75.22   75.13
   75.03   74.93    74.6    74.1    74.5    74.4    74.7    74.3    73.8    73.9
    77.9   77.84    77.5    77.7    76.4   76.45    76.6    77.3    76.7   76.62
    76.4    76.8    76.2    76.4    75.8    76.1    75.7    75.8    75.2    75.2
    75.4    75.2      75    75.5    74.6   72.85   73.51   73.58   70.99   70.82
   69.85   71.95    71.6   70.28   70.28   71.43   71.42   71.78   71.98    72.8
    73.3    73.3    73.6    73.4    73.9    73.8    73.5    72.9    71.9    72.7
    72.8    73.6   73.68    73.7   73.58    73.4   73.31   73.77    73.8    73.9
  4034.7  4049.3  4084.7  4094.7  4134.7  4139.3  4154.7  4169.7  4239.3  4249.3
  4274.3  4284.8  4364.8  4394.8  4429.8  4444.8  4459.8  4474.8  4499.8    4547
    4552    4557    4627    4642    4677  4699.9  4710.1  4746.8  4814.4  4905.8
 4920.01  4920.1 5070.99  5071.1  5071.2  5113.4    5161  5226.4  5244.1  5249.7
  5264.7  5294.7  5309.7  5324.7  5344.7  5349.7  5354.7  5359.7    5375    5390
    5405    5420    5469    5484    5499    5519    5529    5544    5545  5555.9
    77.9    78.4   78.21   78.15   78.08    77.9   77.82   77.75    77.4    77.2
    77.7    77.5   77.39   77.34   77.27   77.24   77.21   77.18   77.13   77.04
   77.03   77.02   76.89   76.86   76.79   76.75   76.73   76.68   76.58   76.45
   76.43   76.43   76.08   76.08   76.08   76.02   75.94   75.84   75.81   75.81
   75.78   75.74   75.66   75.56   75.43   75.39   75.36   75.33   75.22   75.13
   75.03   74.93    74.6    74.1    74.5    74.4    74.7    74.3    73.8    73.9
   77.81   77.75   77.41   77.61   76.31   76.36   76.51   77.21   76.61   76.53
   76.31   76.71   76.11   76.31   75.71   76.01   75.61   75.71   75.11   75.11
   75.31   75.11   74.91   75.41   74.51   72.76   73.42   73.49    70.9   70.73
   69.76   71.86   71.51   70.19   70.19   71.34   71.33   71.69   71.89   72.71
   73.21   73.21   73.51   73.31   73.81   73.71   73.41   72.81   71.81   72.61
   72.71   73.51   73.59   73.61   73.49   73.31   73.22   73.68   73.71   73.81
Pier Skew, UpSta & Num, DnSta & Num=  ,4950.8, 2 ,4950.8, 2 , 0 , 0 , 0 ,,
       2       2
   67.76   72.88
       2       2
   67.67   72.79
Pier Skew, UpSta & Num, DnSta & Num=  ,4967.2, 2 ,4967.2, 2 , 0 , 0 , 0 ,,
     1.2     1.2
    57.4   72.84
     1.2     1.2
   57.31   72.75
Pier Skew, UpSta & Num, DnSta & Num=  ,4980.8, 2 ,4980.8, 2 , 0 , 0 , 0 ,,
     1.2     1.2
   55.86   72.81
     1.2     1.2
   55.77   72.72
Pier Skew, UpSta & Num, DnSta & Num=  ,4995.1, 2 ,4995.1, 2 , 0 , 0 , 0 ,,
       3       3
   55.98   72.78
       3       3
   55.89   72.69
Pier Skew, UpSta & Num, DnSta & Num=  ,5011.2, 2 ,5011.2, 2 , 0 , 0 , 0 ,,
     1.2     1.2
   56.48   72.74
     1.2     1.2
   56.39   72.65
Pier Skew, UpSta & Num, DnSta & Num=  ,5024.7, 2 ,5024.7, 2 , 0 , 0 , 0 ,,
     1.2     1.2
   56.33   72.71
     1.2     1.2
   56.24   72.62
Pier Skew, UpSta & Num, DnSta & Num=  ,5041.1, 2 ,5041.1, 2 , 0 , 0 , 0 ,,
     1.2     1.2
   62.26   72.67
     1.2     1.2
   62.17   72.58
BR Coef= 1 , 1 , 0 ,1.25, 0 ,,,0.8,0,2,0,
WSPro=,,,, 1 ,,,, 0 ,,,, 0 ,,,,-1 ,-1 ,-1 , 0 , 0 , 0 , 0 , 0
BR U #Sta/Elev= 100
  4034.7    77.9  4049.3   77.84  4059.7    77.8  4084.7    77.5  4094.7    77.7
  4099.7    77.6  4104.3   77.44  4134.3   76.41  4134.7    76.4  4139.3   76.45
  4154.7    76.6  4169.7    77.3  4239.3    76.7  4249.3   76.62  4274.3    76.4
  4274.8    76.4  4284.3   76.78  4284.8    76.8  4309.3   76.62  4364.8    76.2
  4394.8    76.4  4403.1   76.26  4429.8    75.8  4444.8    76.1  4459.8    75.7
  4474.8    75.8  4499.8    75.2  4544.8    75.2    4547    75.2    4552    75.4
    4557    75.2    4627      75    4642    75.5    4677    74.6  4699.9   72.85
  4704.4   73.14  4710.1   73.51  4746.8   73.58  4814.4   70.99  4905.8   70.82
 4919.09   69.92  4919.2   69.91 4919.31    69.9  4919.9   69.86 4920.01   69.85
  4920.1   69.85  4920.2   69.84  4920.3   69.84  4944.1   70.96  4950.8   68.67
  4957.7    69.3  4964.5   59.64  4967.2   58.47  4980.8   56.85  4995.1   56.99
  5011.2    57.5  5024.7   57.32  5035.5   59.59  5041.1    63.7  5047.2   70.47
  5058.6   71.18  5070.7   70.28  5070.8   70.27 5070.99   70.28  5071.1   70.28
  5071.2   70.28  5071.9    70.3  5078.1   70.47  5113.4   71.43    5161   71.42
  5226.4   71.78  5243.9   71.98  5244.1   71.98  5249.7    72.8  5264.7    73.3
  5294.7    73.3 5298.79   73.38  5298.9   73.38 5299.01   73.39  5309.7    73.6
  5324.7    73.4  5344.7    73.9  5349.7    73.8  5354.7    73.5  5359.7    72.9
    5365    72.5    5375    71.9    5390    72.7    5405    72.8    5420    73.6
    5469   73.68    5484    73.7    5485    73.7    5499   73.58    5519    73.4
    5529   73.31    5530    73.3    5544   73.77    5545    73.8  5555.9    73.9
BR U #Mann= 6
  4034.7      .2  4034.7      .1  4403.1     .14  4957.7    .035  5047.2     .14
  5555.9      .2
BR U Banks=4957.7,5047.2
BR D #Sta/Elev= 100
  4034.7   77.81  4049.3   77.75  4059.7   77.71  4084.7   77.41  4094.7   77.61
  4099.7   77.51  4104.3   77.35  4134.3   76.32  4134.7   76.31  4139.3   76.36
  4154.7   76.51  4169.7   77.21  4239.3   76.61  4249.3   76.53  4274.3   76.31
  4274.8   76.31  4284.3   76.69  4284.8   76.71  4309.3   76.53  4364.8   76.11
  4394.8   76.31  4403.1   76.17  4429.8   75.71  4444.8   76.01  4459.8   75.61
  4474.8   75.71  4499.8   75.11  4544.8   75.11    4547   75.11    4552   75.31
    4557   75.11    4627   74.91    4642   75.41    4677   74.51  4699.9   72.76
  4704.4   73.05  4710.1   73.42  4746.8   73.49  4814.4    70.9  4905.8   70.73
 4919.09   69.83  4919.2   69.82 4919.31   69.81  4919.9   69.77 4920.01   69.76
  4920.1   69.76  4920.2   69.75  4920.3   69.75  4944.1   70.87  4950.8   68.58
  4957.7   69.21  4964.5   59.55  4967.2   58.38  4980.8   56.76  4995.1    56.9
  5011.2   57.41  5024.7   57.23  5035.5    59.5  5041.1   63.61  5047.2   70.38
  5058.6   71.09  5070.7   70.19  5070.8   70.18 5070.99   70.19  5071.1   70.19
  5071.2   70.19  5071.9   70.21  5078.1   70.38  5113.4   71.34    5161   71.33
  5226.4   71.69  5243.9   71.89  5244.1   71.89  5249.7   72.71  5264.7   73.21
  5294.7   73.21 5298.79   73.29  5298.9   73.29 5299.01    73.3  5309.7   73.51
  5324.7   73.31  5344.7   73.81  5349.7   73.71  5354.7   73.41  5359.7   72.81
    5365   72.41    5375   71.81    5390   72.61    5405   72.71    5420   73.51
    5469   73.59    5484   73.61    5485   73.61    5499   73.49    5519   73.31
    5529   73.22    5530   73.21    5544   73.68    5545   73.71  5555.9   73.81
BR D #Mann= 6
  4034.7      .2  4034.7      .1  4403.1     .14  4957.7    .035  5047.2     .14
  5555.9      .2
BR D Banks=4957.7,5047.2
BC Design=,, 0 ,, 0 ,,,,,,
BC HTab HWMax=77.93
BC Use User HTab Curves=0
BC User HTab FreeFlow(D)= 0

Type RM Length L Ch R = 1 ,30697.8 ,509.6,509.6,509.6
BEGIN DESCRIPTION:
Downstream Section of Bridge/Culvert/Weir
END DESCRIPTION:
XS GIS Cut Line= 3
      3147870.33     13921363.86      3147549.12     13920354.36
      3147418.72     13919911.32
#Sta/Elev= 30
  4034.7    77.8  4094.7    77.6  4134.7    76.3  4169.7    77.2  4403.1   76.16
  4499.8    75.1    4642    75.4    4677    74.5  4699.9   72.75  4746.8   73.48
  4814.4   70.89  4905.8   70.72  4920.2   69.74  4944.1   70.86  4950.8   68.57
  4957.7    69.2  4964.5   59.54  4967.2   58.37  4980.8   56.75  5024.7   57.22
  5035.5   59.49  5041.1    63.6  5047.2   70.37  5058.6   71.08  5244.1   71.88
  5264.7    73.2  5344.7    73.8    5375    71.8    5420    73.5  5555.9    73.8
#Mann= 6 , 1 , 0
  4034.7      .2       0  4034.7      .1       0  4403.1     .14       0
  4957.7    .035       0  5047.2     .14       0  5555.9      .2       0
#XS Ineff= 2 , 0
       0    4910   76.53    5080       0   74.06
Permanent Ineff=
       F       F
Bank Sta=4957.7,5047.2
XS Rating Curve= 0 ,0
Exp/Cntr=0.5,0.3

Type RM Length L Ch R = 1 ,30188.2 ,763,811.1,835.7
BEGIN DESCRIPTION:
Cross Section 30188.2
END DESCRIPTION:
XS GIS Cut Line= 5
      3149231.08     13920859.68      3148143.59     13920199.42
      3147955.05     13920102.73      3147693.99     13920035.05
      3147413.05      13919859.7
#Sta/Elev= 30
  3407.1    78.7  3552.1    77.4  3712.1      77  3792.1    75.7  3852.1    76.1
  4007.1    75.5  4062.1    76.3  4142.1    76.3  4587.1      73  4612.1    73.3
  4891.2    70.5  4937.7   68.75  4953.9   69.44  4971.1    64.7    4985   61.92
  4989.7   56.43  5008.8   56.71  5020.2   63.52  5056.6   63.34  5083.1    71.3
    5102   70.66  5111.2      71  5235.9    71.2  5255.9    71.8  5370.9    72.9
  5395.9    72.7  5420.9    73.5  5465.9    74.1  5480.9    74.2  5492.1    73.7
#Mann= 5 , 1 , 0
  3407.1      .2       0  3407.1     .14       0  4953.9    .035       0
  5083.1     .14       0  5492.1      .2       0
Bank Sta=4953.9,5083.1
XS Rating Curve= 0 ,0
Exp/Cntr=0.3,0.1

Type RM Length L Ch R = 1 ,29377.1 ,812.5,789,738.8
BEGIN DESCRIPTION:
Cross Section 29377.1
END DESCRIPTION:
XS GIS Cut Line= 5
      3149584.04     13919556.11       3148729.7     13919528.03
      3148356.68     13919459.85      3148039.81     13919267.32
      3147129.32     13919074.79
#Sta/Elev= 30
  3519.1    75.7  3604.1    75.7  3619.1    74.3  3659.1    75.5  4169.1    74.4
  4753.1    70.6  4898.5   68.57    4928   69.23  4949.6   61.39  4974.7   60.81
    4992   57.68    4995   56.57  4999.6   56.36  5006.1   56.52  5015.9   61.41
  5026.3   61.55  5046.5    67.8  5071.8   68.59  5083.1    70.4  5088.1    71.5
  5118.1    82.8  5128.9    84.1  5153.9    83.9  5218.9    77.2  5258.9    73.9
  5293.9    72.2  5978.9    73.3  6028.9    74.1  6038.9    75.3  6054.5    75.2
#Mann= 5 , 1 , 0
  3519.1      .2       0  3519.1      .1       0    4928    .035       0
  5046.5     .14       0  6054.5      .2       0
Bank Sta=4928,5046.5
XS Rating Curve= 0 ,0
Exp/Cntr=0.3,0.1

Type RM Length L Ch R = 1 ,28588.1 ,860.9,815.5,787.9
BEGIN DESCRIPTION:
Cross Section 28588.1 - Interpolated
END DESCRIPTION:
XS GIS Cut Line= 5
      3149725.14     13919143.24      3148550.22     13918654.96
      3148016.16     13918548.15      3147344.77     13918395.56
       3146963.3     13918441.33
#Sta/Elev= 30
  3716.8      75  3781.8    76.1  3873.8   74.22    4101   73.44  4226.8    72.9
  4261.8    71.3  4271.8    72.4  4836.8    69.5  4891.8    65.7  4906.8    66.1
  4915.7   68.14  4943.8   68.11  4959.6   63.49  4973.1   61.28  4985.2   60.97
    4993   55.11  5007.3   55.28  5008.2   56.53  5020.3   61.65  5046.5    62.4
  5069.7   69.92  5154.1    71.3  5239.1    70.1  5533.8    72.2  6138.8    72.5
  6213.8    73.1  6257.3    75.6  6397.3      76  6442.3    73.5  6606.5      74
#Mann= 7 , 1 , 0
  3716.8      .2       0  3716.8      .1       0  3873.8     .14       0
    4101      .1       0  4943.8    .035       0  5069.7      .1       0
  6606.5      .2       0
#XS Ineff= 2 , 0
       0                    5155       0    71.7
Permanent Ineff=
       F       F
Bank Sta=4943.8,5069.7
XS Rating Curve= 0 ,0
Exp/Cntr=0.3,0.1

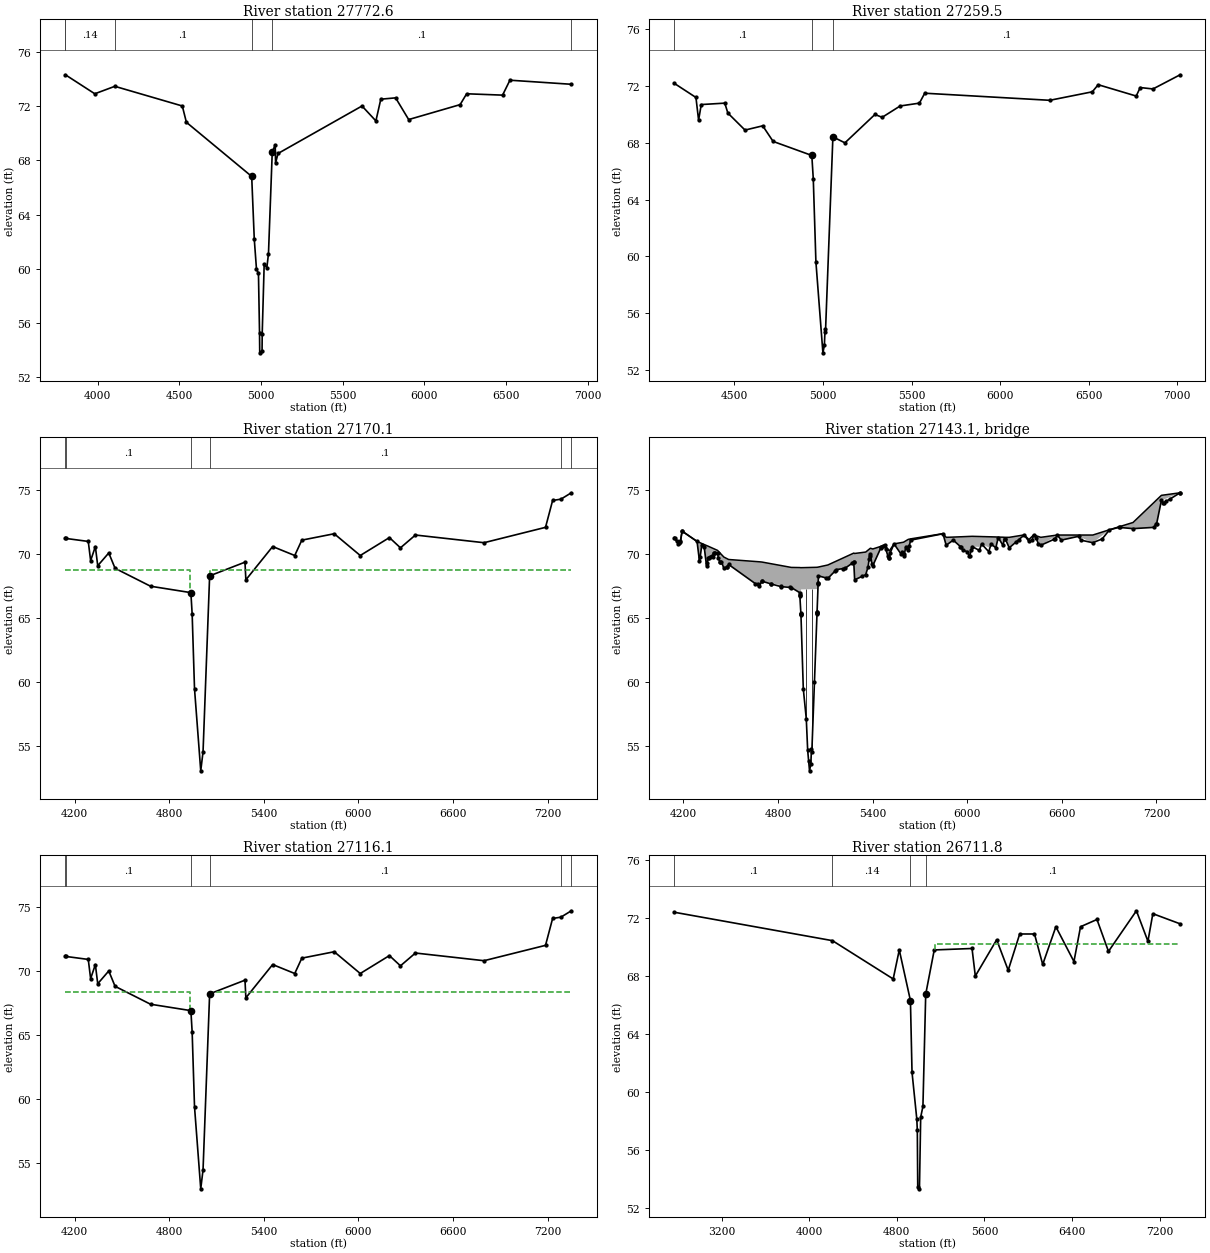
Type RM Length L Ch R = 1 ,27772.6 ,516.3,513.1,504.9
BEGIN DESCRIPTION:
Cross Section 27772.6
END DESCRIPTION:
XS GIS Cut Line= 6
      3149957.06     13918192.38      3149507.83     13918007.87
      3149086.68     13917915.62      3148569.26      13917871.5
      3147983.66     13917867.49      3146972.89      13918236.5
#Sta/Elev= 30
  3803.1    74.3  3983.1    72.9  4105.7   73.45  4518.9      72  4543.9    70.8
  4943.8   66.81  4959.6   62.19  4973.1   59.98  4985.2   59.67  4991.8   55.27
    4993   53.81  5007.3   53.98  5008.2   55.23  5020.3   60.35  5036.5   60.08
  5046.5    61.1  5069.7   68.62  5087.8   69.14    5090    67.8    5105    68.5
  5619.3      72  5704.3    70.9  5734.3    72.5    5825    72.6    5905      71
    6220    72.1    6260    72.9    6480    72.8    6525    73.9    6901    73.6
#Mann= 6 , 1 , 0
  3803.1      .2       0  3803.1     .14       0  4105.7      .1       0
  4943.8    .035       0  5069.7      .1       0    6901      .2       0
Bank Sta=4943.8,5069.7
XS Rating Curve= 0 ,0
Exp/Cntr=0.3,0.1

Type RM Length L Ch R = 1 ,27259.5 ,84.1,89.4,97
BEGIN DESCRIPTION:
Cross Section 27259.5 - Interpolated
END DESCRIPTION:
XS GIS Cut Line= 6
      3149650.13     13917425.01      3149005.62     13917391.36
      3148812.84     13917383.26       3148526.4     13917372.09
      3148385.34     13917364.49      3146797.57     13917288.22
#Sta/Elev= 30
  4160.2    72.2    4283    71.2    4298    69.6    4313    70.7  4445.8    70.8
  4463.2    70.1    4560    68.9    4660    69.2  4718.6    68.1  4937.1   67.11
  4945.4   65.45  4960.2    59.6  4999.7   53.19    5008   53.72  5011.9   54.87
  5014.3   54.68  5056.1   68.42    5124      68  5293.3      70  5334.2    69.8
  5435.8    70.6  5544.4    70.8  5574.5    71.5  6280.3      71  6520.6    71.6
  6553.5    72.1  6768.2    71.3  6790.9    71.9  6862.9    71.8  7016.1    72.8
#Mann= 3 , 1 , 0
  4160.2      .1       0  4937.1    .035       0  5056.1      .1       0
Bank Sta=4937.1,5056.1
XS Rating Curve= 0 ,0
Exp/Cntr=0.5,0.3

Type RM Length L Ch R = 1 ,27170.1 ,54,54,54
BEGIN DESCRIPTION:
Upstream Section of Bridge/Culvert/Weir
END DESCRIPTION:
XS GIS Cut Line= 6
       3149680.6     13917340.31      3148869.44     13917297.38
      3148676.32     13917283.91      3147993.92     13917253.53
      3147277.25     13917212.64      3146479.06     13917138.01
#Sta/Elev= 30
  4141.4   71.31  4146.4   71.24  4286.4   71.01  4301.4   69.51  4331.4   70.61
  4346.4   69.11  4416.4   70.11  4456.4   68.91  4681.4   67.51  4937.1   67.01
  4945.2   65.35  4960.2    59.5  4999.7   53.09  5014.3   54.58  5056.1   68.32
  5280.3   69.39  5285.8   68.01  5455.8   70.61  5595.8   69.91  5640.8   71.11
  5846.2   71.61  6011.2   69.91  6196.2   71.31  6266.2   70.51  6361.2   71.51
  6796.2   70.91  7186.2   72.11  7231.2   74.21  7283.7   74.31  7349.9   74.81
#Mann= 6 , 1 , 0
  4141.4      .2       0  4146.4      .1       0  4937.1    .035       0
  5056.1      .1       0  7283.7     .14       0  7349.9      .2       0
#XS Ineff= 2 , 0
       0    4934    68.8    5058       0    68.8
Permanent Ineff=
       F       F
Bank Sta=4937.1,5056.1
XS Rating Curve= 0 ,0
Exp/Cntr=0.5,0.3

Type RM Length L Ch R = 3 ,27143.1 ,,,
BEGIN DESCRIPTION:
RANKIN ROAD W/ 10" PIPE
Structure ID: P30-13
END DESCRIPTION:
Bridge Culvert--1,0,-1,-1, 0
Deck Dist Width WeirC Skew NumUp NumDn MinLoCord MaxHiCord MaxSubmerge Is_Ogee
10,34,2.6,0, 60, 60, , , 0.95, 0, 1,1,,
  4141.4  4166.4  4181.4  4191.4  4286.4  4301.4  4316.4  4331.4  4346.4  4356.4
  4416.4  4456.4  4486.4  4681.4  4697.8  4884.1  4937.1    4945  4945.2  4945.3
 5047.19  5047.3  5056.1  5115.7  5280.3  5285.8  5355.8  5385.8  5400.8  5475.8
  5505.8  5535.8  5595.8  5610.8  5625.8  5640.8  5846.2  5866.2  5911.2  6011.2
  6031.2  6181.2  6196.2  6226.2  6241.2  6266.2  6361.2  6391.2  6421.2  6466.2
  6571.2  6596.2  6706.2  6796.2  6901.2  7051.2  7186.2  7201.2  7231.2  7349.9
    71.3   70.81   71.01   71.81      71   70.92   70.84   70.76   70.68   70.63
    70.3   69.78   69.59   69.41   69.39   68.97   68.96   68.95   68.95   68.95
   68.98   68.98      69   69.16   70.09   70.06   70.17   70.47   70.41   70.71
   70.26   70.81   70.94   71.05   71.16    71.2   71.61   71.32   71.34   71.39
    71.4   71.35   71.34   71.33   71.32   71.32   71.51   71.15   71.51   71.32
    71.5    71.5    71.5    71.5   71.91   72.48   74.07   74.25    74.6    74.8
    71.3    70.8      71    71.8      71    69.5    70.7    70.6    69.1    69.7
    70.1    68.9    69.2    67.5    67.9    67.4      67   65.38   65.34   67.25
   67.28   65.46   68.31   68.11   69.38      68    68.4      70    69.1    70.7
    69.7    70.8    69.9    70.6    70.3    71.1    71.6    70.7    71.1    69.9
    70.6    70.5    71.3    70.7    71.2    70.5    71.5      71    71.5    70.7
    71.5    71.1    71.4    70.9    71.9      72    72.1    72.4    74.2    74.8
  4141.4  4166.4  4181.4  4191.4  4286.4  4301.4  4316.4  4331.4  4346.4  4356.4
  4416.4  4456.4  4486.4  4681.4  4697.8  4884.1  4937.1    4945  4945.2  4945.3
 5047.19  5047.3  5056.1  5115.7  5280.3  5285.8  5355.8  5385.8  5400.8  5475.8
  5505.8  5535.8  5595.8  5610.8  5625.8  5640.8  5846.2  5866.2  5911.2  6011.2
  6031.2  6181.2  6196.2  6226.2  6241.2  6266.2  6361.2  6391.2  6421.2  6466.2
  6571.2  6596.2  6706.2  6796.2  6901.2  7051.2  7186.2  7201.2  7231.2  7349.9
    71.3   70.81   71.01   71.81      71   70.92   70.84   70.76   70.68   70.63
    70.3   69.78   69.59   69.41   69.39   68.97   68.96   68.95   68.95   68.95
   68.98   68.98      69   69.16   70.09   70.06   70.17   70.47   70.41   70.71
   70.26   70.81   70.94   71.05   71.16    71.2   71.61   71.32   71.34   71.39
    71.4   71.35   71.34   71.33   71.32   71.32   71.51   71.15   71.51   71.32
    71.5    71.5    71.5    71.5   71.91   72.48   74.07   74.25    74.6    74.8
   71.22   70.72   70.92   71.72   70.92   69.42   70.62   70.52   69.02   69.62
   70.02   68.82   69.12   67.42   67.82   67.32   66.92    65.3   65.26   67.17
    67.2   65.38   68.23   68.03    69.3   67.92   68.32   69.92   69.02   70.62
   69.62   70.72   69.82   70.52   70.22   71.02   71.52   70.62   71.02   69.82
   70.52   70.42   71.22   70.62   71.12   70.42   71.42   70.92   71.42   70.62
   71.42   71.02   71.32   70.82   71.82   71.92   72.02   72.32   74.12   74.72
Pier Skew, UpSta & Num, DnSta & Num=  ,4979.1, 2 ,4979.1, 2 , 0 , 0 , 0 ,,
     1.2     1.2
   55.98   68.26
     1.2     1.2
    55.9   68.18
Pier Skew, UpSta & Num, DnSta & Num=  ,5014.3, 2 ,5014.3, 2 , 0 , 0 , 0 ,,
     1.2     1.2
   53.62   68.27
     1.2     1.2
   53.54   68.19
BR Coef= 1 , 1 , 0 ,1.25, 0 ,,,0.8,0,2,0,
WSPro=,,,, 1 ,,,, 0 ,,,, 0 ,,,,-1 ,-1 ,-1 , 0 , 0 , 0 , 0 , 0
BR U #Sta/Elev= 160
  4141.4    71.3  4146.4   71.23  4161.4      71  4166.4    70.8  4171.4   70.87
  4176.4   70.93  4181.4      71  4191.3    71.8  4191.4    71.8  4286.4      71
  4301.4    69.5  4306.4    69.8  4316.4    70.7  4331.4    70.6  4346.4    69.1
  4351.4    69.3  4356.4    69.7  4361.4   69.74  4371.4   69.82  4381.4    69.9
  4386.4    69.8  4391.3    70.1  4391.4    70.1  4401.4    70.1  4416.4    70.1
  4421.4    69.7  4431.3    69.4  4431.4    69.4  4441.4    69.4  4456.4    68.9
  4476.3      69  4476.4      69  4486.4    69.2  4656.4    67.7  4671.4    67.7
  4681.4    67.5  4697.8    67.9  4699.1   67.89  4757.2   67.67  4758.5   67.67
  4816.1   67.48  4819.1   67.47  4875.7   67.41  4884.1    67.4  4937.1      67
 4937.99   66.82  4938.1    66.8 4938.21   66.77    4945   65.38 4945.11   65.36
  4945.2   65.34  4945.3    65.3  4945.4   65.26  4960.2   59.49  4979.1   57.15
    4988   54.67  4993.9   53.82  4999.7   53.08    5008   53.61  5011.9   54.76
  5014.3   54.57  5031.1   60.04    5047   65.37  5047.1    65.4 5047.19   65.43
  5047.3   65.46  5047.4    65.5 5054.19   67.69  5054.3   67.73 5054.41   67.76
  5056.1   68.31  5104.6   68.15  5115.7   68.11  5159.4   68.66  5170.7    68.8
  5211.9   68.88  5224.4    68.9  5268.6   69.28  5280.2   69.38  5280.3   69.38
  5285.8      68  5332.3   68.27  5355.8    68.4  5370.8      69  5377.3   69.59
  5380.8    69.9  5385.8      70  5395.8    69.2  5400.8    69.1  5452.3    70.5
  5455.8    70.6  5467.3   70.66  5475.8    70.7  5482.3   70.44  5497.3   69.84
  5500.8    69.7  5505.8    69.7  5510.8    70.1  5535.8    70.8  5580.8      70
  5585.8    70.2  5595.8    69.9  5600.8      70  5610.8    70.6  5617.3   70.47
  5625.8    70.3  5632.3   70.65  5640.8    71.1  5846.2    71.6  5866.2    70.7
  5911.2    71.1  5956.2    70.6  5961.2    70.6  5971.2    70.3  6001.2    70.2
  6011.2    69.9  6016.2    69.9  6025.4   70.33  6031.2    70.6  6076.2    70.3
  6091.2    70.8  6136.2    70.2  6151.2    70.8  6181.2    70.5  6196.2    71.3
  6226.2    70.7  6236.2    71.2  6241.2    71.2  6266.2    70.5  6310.4   70.97
  6325.4   71.12  6361.2    71.5  6391.2      71  6411.2    71.1  6421.2    71.5
  6436.2    71.3  6451.2    70.8  6466.2    70.7  6548.2   71.16  6556.2    71.2
  6571.2    71.5  6596.2    71.1  6706.2    71.4  6721.2    71.1  6796.2    70.9
  6856.2    71.2  6901.2    71.9  6961.2    72.1  6968.2   72.09  7051.2      72
  7186.2    72.1  7196.2    72.4  7201.2    72.4  7231.2    74.2  7244.2      74
  7248.2   74.03  7263.2   74.14  7283.7    74.3  7348.2   74.79  7349.9    74.8
BR U #Mann= 6
  4141.4      .2  4146.4      .1  4937.1    .035  5056.1      .1  7283.7     .14
  7349.9      .2
BR U Banks=4937.1,5056.1
BR D #Sta/Elev= 160
  4141.4   71.22  4146.4   71.15  4161.4   70.92  4166.4   70.72  4171.4   70.79
  4176.4   70.85  4181.4   70.92  4191.3   71.72  4191.4   71.72  4286.4   70.92
  4301.4   69.42  4306.4   69.72  4316.4   70.62  4331.4   70.52  4346.4   69.02
  4351.4   69.22  4356.4   69.62  4361.4   69.66  4371.4   69.74  4381.4   69.82
  4386.4   69.72  4391.3   70.02  4391.4   70.02  4401.4   70.02  4416.4   70.02
  4421.4   69.62  4431.3   69.32  4431.4   69.32  4441.4   69.32  4456.4   68.82
  4476.3   68.92  4476.4   68.92  4486.4   69.12  4656.4   67.62  4671.4   67.62
  4681.4   67.42  4697.8   67.82  4699.1   67.81  4757.2   67.59  4758.5   67.59
  4816.1    67.4  4819.1   67.39  4875.7   67.33  4884.1   67.32  4937.1   66.92
 4937.99   66.74  4938.1   66.72 4938.21   66.69    4945    65.3 4945.11   65.28
  4945.2   65.26  4945.3   65.22  4945.4   65.18  4960.2   59.41  4979.1   57.07
    4988   54.59  4993.9   53.74  4999.7      53    5008   53.53  5011.9   54.68
  5014.3   54.49  5031.1   59.96    5047   65.29  5047.1   65.32 5047.19   65.35
  5047.3   65.38  5047.4   65.42 5054.19   67.61  5054.3   67.65 5054.41   67.68
  5056.1   68.23  5104.6   68.07  5115.7   68.03  5159.4   68.58  5170.7   68.72
  5211.9    68.8  5224.4   68.82  5268.6    69.2  5280.2    69.3  5280.3    69.3
  5285.8   67.92  5332.3   68.19  5355.8   68.32  5370.8   68.92  5377.3   69.51
  5380.8   69.82  5385.8   69.92  5395.8   69.12  5400.8   69.02  5452.3   70.42
  5455.8   70.52  5467.3   70.58  5475.8   70.62  5482.3   70.36  5497.3   69.76
  5500.8   69.62  5505.8   69.62  5510.8   70.02  5535.8   70.72  5580.8   69.92
  5585.8   70.12  5595.8   69.82  5600.8   69.92  5610.8   70.52  5617.3   70.39
  5625.8   70.22  5632.3   70.57  5640.8   71.02  5846.2   71.52  5866.2   70.62
  5911.2   71.02  5956.2   70.52  5961.2   70.52  5971.2   70.22  6001.2   70.12
  6011.2   69.82  6016.2   69.82  6025.4   70.25  6031.2   70.52  6076.2   70.22
  6091.2   70.72  6136.2   70.12  6151.2   70.72  6181.2   70.42  6196.2   71.22
  6226.2   70.62  6236.2   71.12  6241.2   71.12  6266.2   70.42  6310.4   70.89
  6325.4   71.04  6361.2   71.42  6391.2   70.92  6411.2   71.02  6421.2   71.42
  6436.2   71.22  6451.2   70.72  6466.2   70.62  6548.2   71.08  6556.2   71.12
  6571.2   71.42  6596.2   71.02  6706.2   71.32  6721.2   71.02  6796.2   70.82
  6856.2   71.12  6901.2   71.82  6961.2   72.02  6968.2   72.01  7051.2   71.92
  7186.2   72.02  7196.2   72.32  7201.2   72.32  7231.2   74.12  7244.2   73.92
  7248.2   73.95  7263.2   74.06  7283.7   74.22  7348.2   74.71  7349.9   74.72
BR D #Mann= 6
  4141.4      .2  4146.4      .1  4937.1    .035  5056.1      .1  7283.7     .14
  7349.9      .2
BR D Banks=4937.1,5056.1
BC Design=,, 0 ,, 0 ,,,,,,
BC HTab HWMax=74.81
BC Use User HTab Curves=0
BC User HTab FreeFlow(D)= 0

Type RM Length L Ch R = 1 ,27116.1 ,404.3,404.3,404.3
BEGIN DESCRIPTION:
Downstream Section of Bridge/Culvert/Weir
END DESCRIPTION:
XS GIS Cut Line= 6
       3149680.6     13917286.31      3148869.44     13917243.38
      3148676.32     13917229.91      3147993.92     13917199.53
      3147277.25     13917158.64      3146479.06     13917084.01
#Sta/Elev= 30
  4141.4   71.23  4146.4   71.16  4286.4   70.93  4301.4   69.43  4331.4   70.53
  4346.4   69.03  4416.4   70.03  4456.4   68.83  4681.4   67.43  4937.1   66.93
  4945.2   65.27  4960.2   59.42  4999.7   53.01  5014.3    54.5  5056.1   68.24
  5280.3   69.31  5285.8   67.93  5455.8   70.53  5595.8   69.83  5640.8   71.03
  5846.2   71.53  6011.2   69.83  6196.2   71.23  6266.2   70.43  6361.2   71.43
  6796.2   70.83  7186.2   72.03  7231.2   74.13  7283.7   74.23  7349.9   74.73
#Mann= 6 , 1 , 0
  4141.4      .2       0  4146.4      .1       0  4937.1    .035       0
  5056.1      .1       0  7283.7     .14       0  7349.9      .2       0
#XS Ineff= 2 , 0
       0    4934    68.4    5058       0    68.4
Permanent Ineff=
       F       F
Bank Sta=4937.1,5056.1
XS Rating Curve= 0 ,0
Exp/Cntr=0.5,0.3

Type RM Length L Ch R = 1 ,26711.8 ,165.8,192.5,219.3
BEGIN DESCRIPTION:
Cross Section 26711.8 - Interpolated
END DESCRIPTION:
XS GIS Cut Line= 6
      3150896.49     13917432.54      3150054.49     13917141.89
      3149224.29     13916874.55      3148883.16     13916849.59
      3148333.08     13916840.75      3146368.72     13916749.54
#Sta/Elev= 30
  2766.3    72.4  4212.1   70.44    4767    67.8  4822.5    69.8  4924.4   66.31
  4938.9   61.37  4982.6   58.14  4987.3   57.37  4991.1   53.48  5006.8   53.33
  5018.1   58.27  5038.5   59.01    5064   66.75  5141.9    69.8  5487.1    69.9
  5517.2      68  5712.1    70.5  5817.5    68.4  5922.6    70.9  6057.7    70.9
  6132.8    68.8    6253    71.4  6418.1      69  6478.2    71.4  6628.4    71.9
  6733.5    69.7  6988.8    72.5  7093.9    70.4  7138.9    72.3    7388    71.6
#Mann= 4 , 1 , 0
  2766.3      .1       0  4212.1     .14       0  4924.4    .035       0
    5064      .1       0
#XS Ineff= 2 , 0
       0                    5145       0    70.2
Permanent Ineff=
       F       F
Bank Sta=4924.4,5064
XS Rating Curve= 0 ,0
Exp/Cntr=0.3,0.1