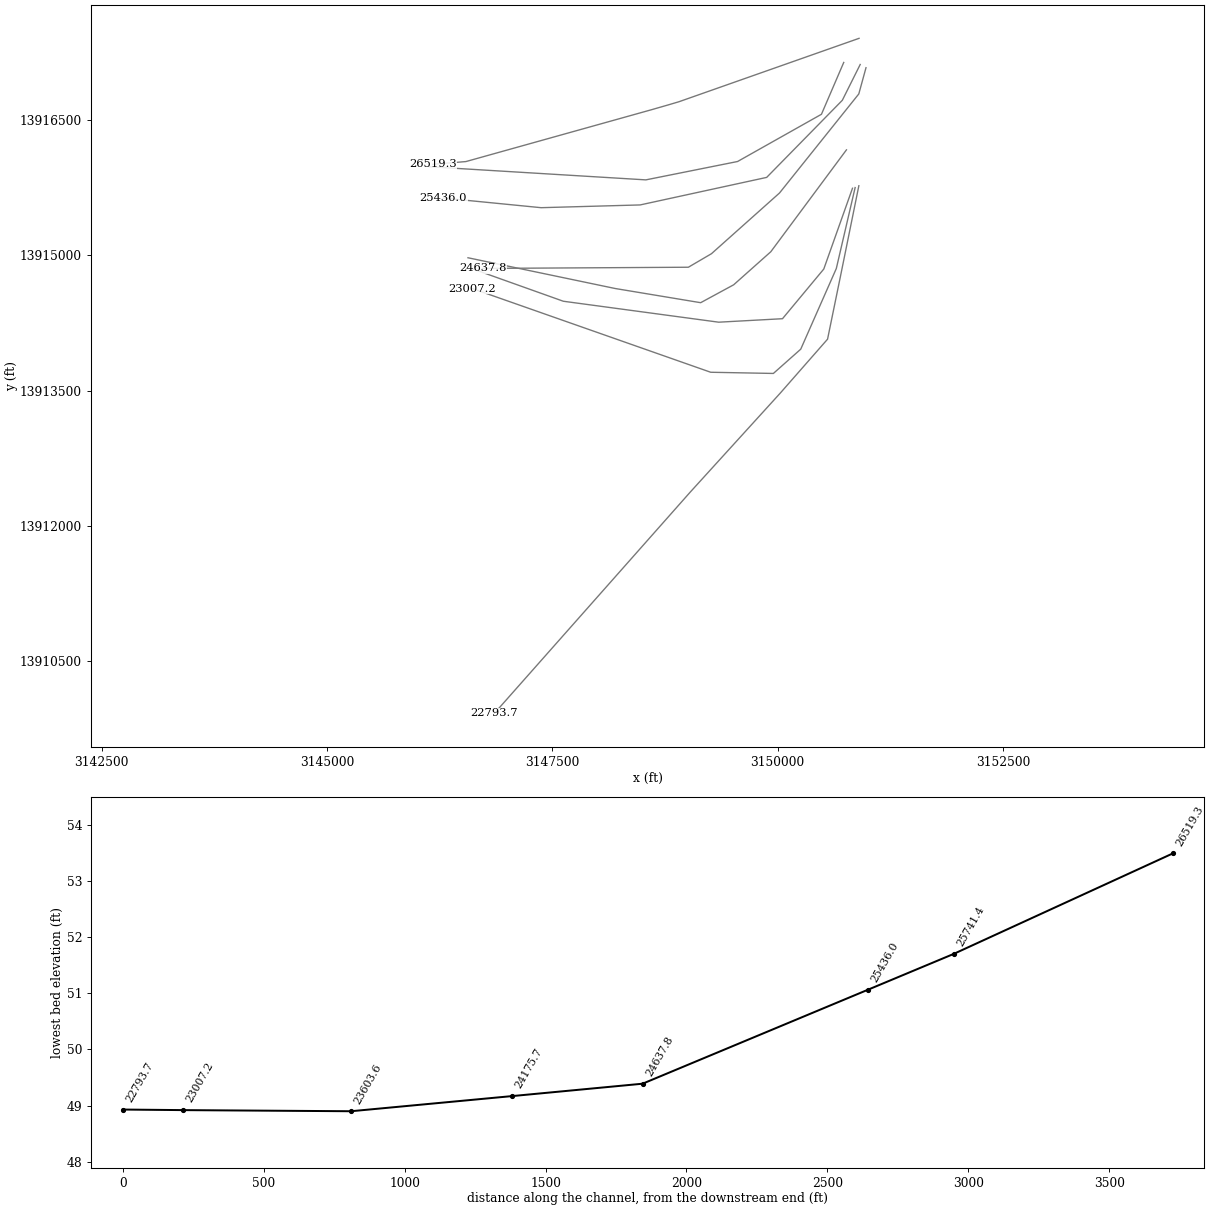
HEC-RAS study P130-00-00.prj: P130-00-00

--- P130-00-00.g01 (geometry) --- (continued)

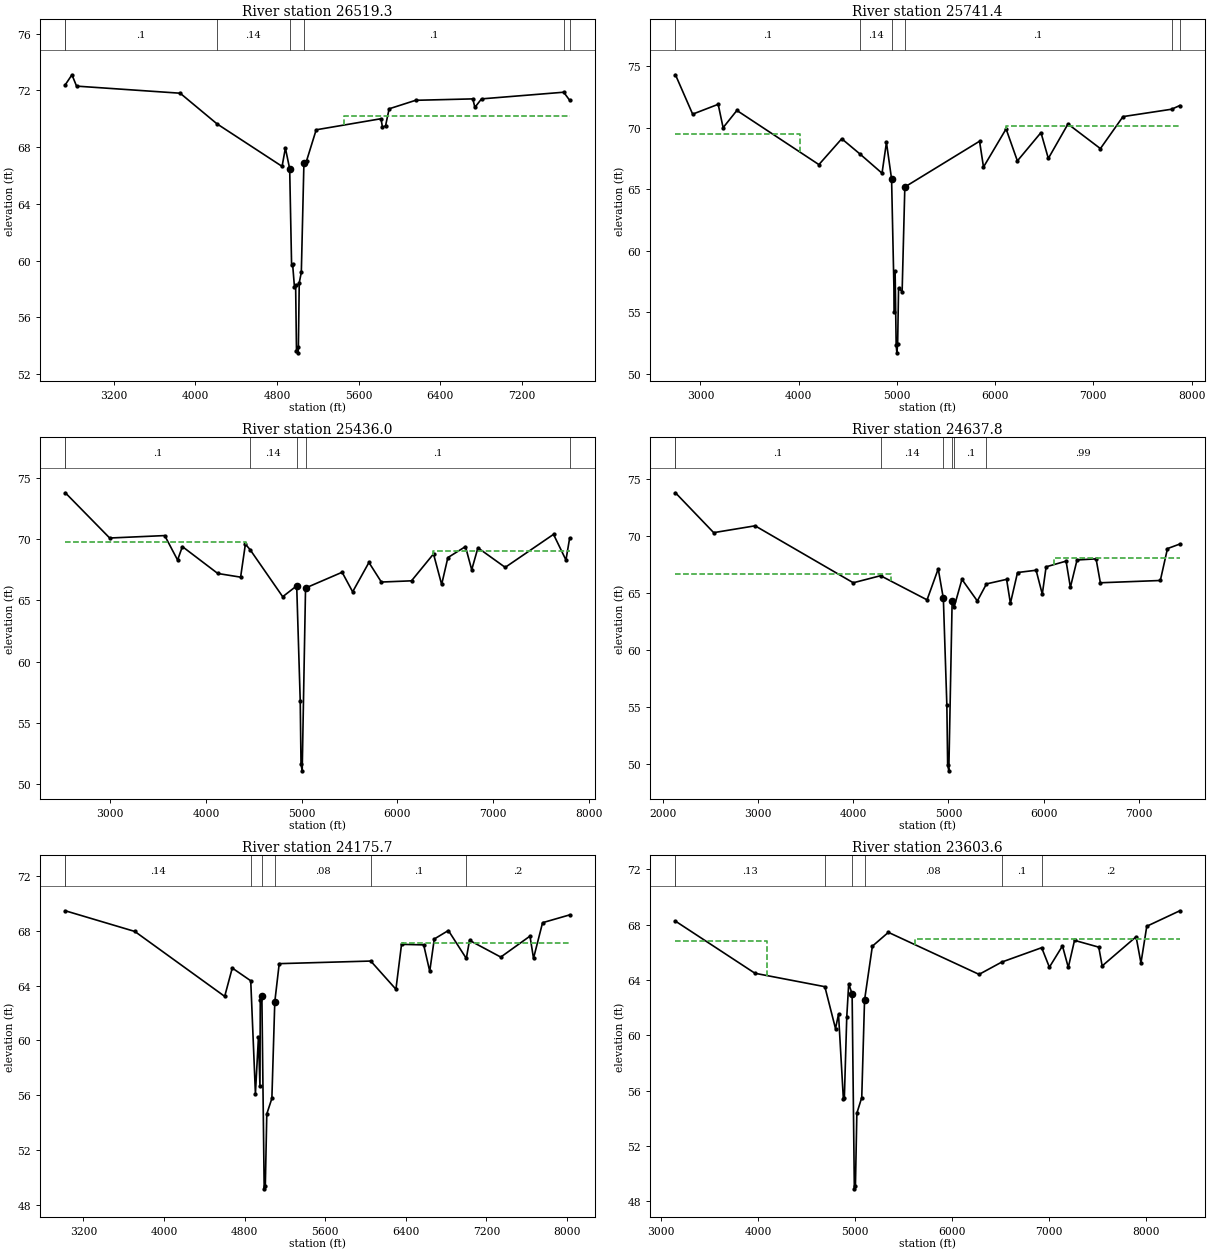
Type RM Length L Ch R = 1 ,26519.3 ,799.3,777.9,770.2
BEGIN DESCRIPTION:
Cross Section 26519.3
END DESCRIPTION:
XS GIS Cut Line= 6
      3150902.68     13917403.69      3148904.23     13916701.03
      3148782.57     13916665.04      3148597.86     13916611.99
      3146540.97     13916038.05      3146174.01     13916007.36
#Sta/Elev= 30
  2726.3    72.4  2791.3    73.1  2836.3    72.3  3851.3    71.8  4212.1   69.64
    4850   66.64  4882.3   67.93  4924.4   66.47  4943.1   59.68  4953.3   59.73
  4971.2   58.12  4982.6    58.3  4991.1   53.64  5006.8   53.49  5009.6   53.88
  5018.1   58.43  5038.5   59.17    5064   66.91  5089.8   67.03  5184.1   69.22
  5818.7      70  5833.7    69.4  5863.7    69.5  5898.7    70.7  6158.7    71.3
  6718.7    71.4  6738.7    70.8  6803.7    71.4  7609.1   71.87  7667.4    71.3
#Mann= 7 , 1 , 0
  2726.3      .2       0  2726.3      .1       0  4212.1     .14       0
  4924.4    .035       0    5064      .1       0  7609.1     .14       0
  7667.4      .2       0
#XS Ineff= 2 , 0
       0                    5452       0    70.2
Permanent Ineff=
       F       F
Bank Sta=4924.4,5064
XS Rating Curve= 0 ,0
Exp/Cntr=0.3,0.1

Type RM Length L Ch R = 1 ,25741.4 ,279.8,305.4,304.5
BEGIN DESCRIPTION:
Cross Section 25741.4
END DESCRIPTION:
XS GIS Cut Line= 5
      3150732.56     13917136.33      3150485.41     13916562.07
      3149554.96     13916038.69      3148537.28     13915835.16
      3146138.47     13915980.54
#Sta/Elev= 30
  2745.9    74.3  2920.9    71.1  3180.9    71.9  3230.9      70  3371.1    71.4
  4206.1      67  4438.6    69.1  4625.7   67.85  4848.6    66.3  4893.6    68.8
  4945.9   65.83  4975.1   55.02  4981.8   58.36  4992.5   52.35  4999.6    51.7
  5007.5    52.4  5017.1   56.98  5053.2   56.66  5080.8   65.18  5841.5    68.9
  5881.5    66.8  6111.5    69.9  6226.5    67.3  6466.5    69.6  6541.5    67.5
  6741.5    70.3  7071.5    68.3  7301.5    70.9  7796.3    71.5  7879.7    71.8
#Mann= 7 , 1 , 0
  2745.9      .2       0  2745.9      .1       0  4625.7     .14       0
  4945.9    .035       0  5080.8      .1       0  7796.3     .14       0
  7879.7      .2       0
#XS Ineff= 2 , 0
       0    4012    69.5    6113       0    70.1
Permanent Ineff=
       F       F
Bank Sta=4945.9,5080.8
XS Rating Curve= 0 ,0
Exp/Cntr=0.3,0.1

Type RM Length L Ch R = 1 ,25436.0 ,560,798.2,727.4
BEGIN DESCRIPTION:
Cross Section 25436.0 - Interpolated
END DESCRIPTION:
XS GIS Cut Line= 6
      3150915.33     13917113.82      3150716.97     13916717.09
      3149877.73      13915862.6      3148473.92     13915557.42
      3147375.29      13915526.9      3146291.92     13915633.72
#Sta/Elev= 30
  2529.2    73.8  2992.8    70.1  3567.8    70.3  3702.4    68.3  3752.4    69.4
  4122.4    67.2  4360.9    66.9  4410.9    69.6    4460   69.15  4800.9    65.3
  4947.1   66.19  4983.9   56.81  4992.2   51.59  5004.5   51.06  5039.5   66.01
  5421.7    67.3  5531.7    65.7  5701.8    68.1  5831.8    66.5  6146.8    66.6
  6376.8    68.8  6461.8    66.3  6526.8    68.5  6710.9    69.4  6775.9    67.5
  6840.9    69.3  7125.9    67.7  7630.9    70.4  7760.9    68.3  7799.5    70.1
#Mann= 6 , 1 , 0
  2529.2      .2       0  2529.2      .1       0    4460     .14       0
  4947.1     .04       0  5039.5      .1       0  7799.5      .2       0
#XS Ineff= 2 , 0
       0    4415    69.8    6371       0      69
Permanent Ineff=
       F       F
Bank Sta=4947.1,5039.5
XS Rating Curve= 0 ,0
Exp/Cntr=0.3,0.1

Type RM Length L Ch R = 1 ,24637.8 ,457.2,462.1,628
BEGIN DESCRIPTION:
Cross Section 24637.8
END DESCRIPTION:
XS GIS Cut Line= 6
      3150979.71     13917078.18      3150899.75     13916787.41
      3150020.19     13915689.77      3149265.18      13915016.9
      3149008.96     13914867.03      3146727.27     13914853.82
#Sta/Elev= 30
  2132.7    73.8  2534.3    70.3  2969.3    70.9  4000.8    65.9  4287.5   66.52
  4775.8    64.4  4893.2   67.12  4947.1   64.52  4983.9   55.14  4992.2   49.92
  5004.5   49.39  5039.5   64.34  5061.1   63.79  5142.2    66.2    5304    64.3
    5400    65.8  5611.5    66.2  5651.5    64.1  5726.5    66.8  5921.5      67
  5986.5    64.9  6026.5    67.3  6236.5    67.8  6281.5    65.5  6351.5    67.9
  6551.5      68  6596.5    65.9  7226.5    66.1  7301.5    68.9    7431    69.3
#Mann= 7 , 1 , 0
  2132.7      .2       0  2132.7      .1       0  4287.5     .14       0
  4947.1     .04       0  5039.5     .08       0  5061.1      .1       0
    5400     .99       0
#XS Ineff= 2 , 0
       0    4393    66.7    6110       0    68.1
Permanent Ineff=
       F       F
Bank Sta=4947.1,5039.5
XS Rating Curve= 0 ,0
Exp/Cntr=0.3,0.1

Type RM Length L Ch R = 1 ,24175.7 ,602.9,572.1,376.3
BEGIN DESCRIPTION:
Cross Section 24175.7 - Interpolated
END DESCRIPTION:
XS GIS Cut Line= 6
      3150762.74     13916167.77      3149923.51     13915038.62
      3149511.52     13914672.41      3149145.31     13914474.05
       3148197.7     13914631.13      3146564.05     13914971.96
#Sta/Elev= 30
  3020.1   69.47  3710.1   67.96    4602   63.22    4677   65.29  4860.5   64.36
    4907   56.12    4937   60.24    4952   56.68  4955.2   62.96    4971   63.27
    4994   49.17  5005.2   49.41  5019.9   54.64  5070.3   55.77  5099.2   62.82
  5143.2   65.61  6051.6    65.8  6301.6   63.74  6357.2   67.02  6577.2   66.98
  6637.2   65.05  6682.2   67.41  6822.2   68.03  7000.2   65.99  7032.2   67.31
  7342.2   66.09  7632.2   67.62  7667.2      66  7757.2    68.6    8026   69.17
#Mann= 7 , 1 , 0
  3020.1      .2       0  3020.1     .14       0  4860.5     .06       0
    4971     .04       0  5099.2     .08       0  6051.6      .1       0
  7000.2      .2       0
#XS Ineff= 2 , 0
       0                    6360       0    67.1
Permanent Ineff=
       F       F
Bank Sta=4971,5099.2
XS Rating Curve= 0 ,0
Exp/Cntr=0.3,0.1

Type RM Length L Ch R = 1 ,23603.6 ,596.4,596.4,596.4
BEGIN DESCRIPTION:
Cross Section 23603.6
END DESCRIPTION:
XS GIS Cut Line= 6
      3150829.78     13915742.26      3150511.29     13914846.88
      3150053.19     13914296.57       3149345.5     13914257.98
      3147621.81     13914490.09       3146599.3     13914854.43
#Sta/Elev= 30
  3149.4   68.26  3969.4   64.49  4689.9   63.52  4799.7   60.49  4830.8   61.53
  4880.8    55.4  4890.8   55.44  4915.8   61.33  4935.8   63.73    4971      63
    4994    48.9  5005.2   49.14  5019.9   54.37  5070.3    55.5  5099.2   62.55
  5179.9   66.45  5344.9   67.45  6280.1   64.41  6513.8    65.3  6925.6   66.34
  7005.1   64.93  7140.1   66.47  7200.1   64.91  7264.3   66.87  7514.3   66.38
  7549.3   65.02  7899.3   67.13  7949.3   65.23  8009.3   67.89  8349.8   69.01
#Mann= 7 , 1 , 0
  3149.4      .2       0  3149.4     .13       0  4689.9     .06       0
    4971     .04       0  5099.2     .08       0  6513.8      .1       0
  6925.6      .2       0
#XS Ineff= 2 , 0
       0    4092    66.8    5623       0   66.95
Permanent Ineff=
       F       F
Bank Sta=4971,5099.2
XS Rating Curve= 0 ,0
Exp/Cntr=0.3,0.1

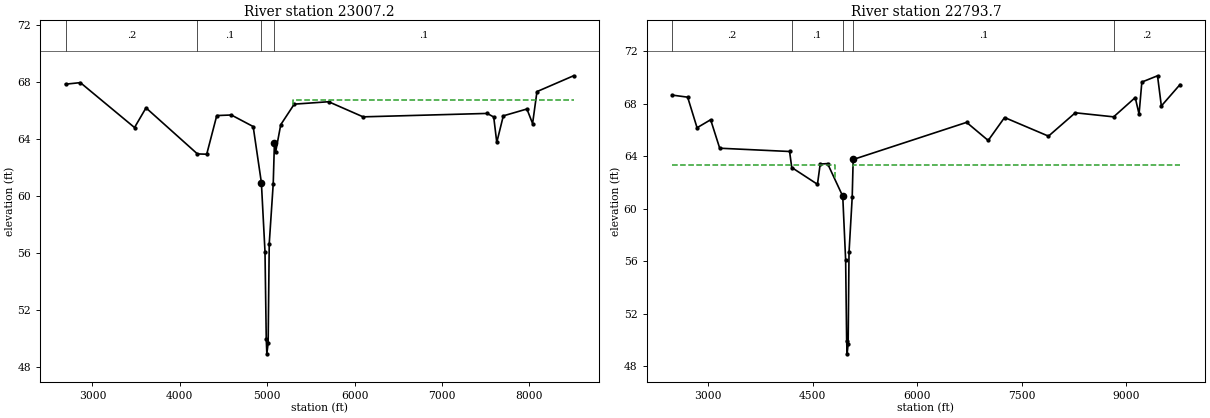
Type RM Length L Ch R = 1 ,23007.2 ,213.5,213.5,213.5
BEGIN DESCRIPTION:
Cross Section 23007.2 - Interpolated
END DESCRIPTION:
XS GIS Cut Line= 6
      3150859.14     13915749.89      3150650.27      13914852.5
      3150255.73     13913958.98      3149952.09     13913689.93
      3149256.74      13913703.1      3146611.06     13914631.13
#Sta/Elev= 30
  2691.3   67.83  2861.3   67.94  3481.3   64.79  3612.7   66.17  4201.3   62.94
  4307.7   62.92  4422.7   65.63  4589.4   65.67  4839.4   64.86  4933.3   60.93
  4974.7   56.08  4989.2   49.93  4995.9   48.92  5010.7   49.67  5023.3   56.65
    5069   60.86  5082.7   63.73  5096.4   63.07  5155.1   64.99  5309.4   66.43
  5702.7    66.6  6097.7   65.54  7517.7   65.78  7592.7   65.53  7627.7   63.75
  7702.7   65.61  7972.7   66.09  8037.7   65.07  8087.7   67.31  8506.5   68.42
#Mann= 4 , 1 , 0
  2691.3      .2       0  4201.3      .1       0  4933.3    .035       0
  5082.7      .1       0
#XS Ineff= 2 , 0
       0                    5300       0    66.7
Permanent Ineff=
       F       F
Bank Sta=4933.3,5082.7
XS Rating Curve= 0 ,0
Exp/Cntr=0.5,0.3

Type RM Length L Ch R = 1 ,22793.7 ,112.4,112.4,112.4
BEGIN DESCRIPTION:
Upstream Section of Bridge/Culvert/Weir
END DESCRIPTION:
XS GIS Cut Line= 6
      3150900.43     13915770.06      3150695.47      13914762.3
      3150553.18     13914069.74       3150029.1     13913472.75
      3149030.04     13912375.36      3146856.41      13909922.8
#Sta/Elev= 30
  2482.4   68.65  2707.4   68.49  2842.4   66.16  3037.4   66.77  3167.4    64.6
  4170.4   64.35  4201.3   63.13  4570.4   61.85  4609.4   63.39  4715.2   63.43
  4933.3   60.94  4974.7   56.09  4989.2   49.94  4995.9   48.93  5010.7   49.68
  5023.3   56.66    5069   60.87  5082.7   63.74  6710.6   66.57  7020.6   65.19
  7255.6   66.94  7885.6   65.52  8270.6    67.3    8821   66.99  9130.6   68.46
  9185.6    67.2  9225.6   69.64  9450.6   70.12  9505.6   67.82  9773.4   69.45
#Mann= 5 , 1 , 0
  2482.4      .2       0  4201.3      .1       0  4933.3    .035       0
  5082.7      .1       0    8821      .2       0
#XS Ineff= 2 , 0
       0    4820   63.32    5080       0   63.34
Permanent Ineff=
       F       F
Bank Sta=4933.3,5082.7
XS Rating Curve= 0 ,0
Exp/Cntr=0.5,0.3