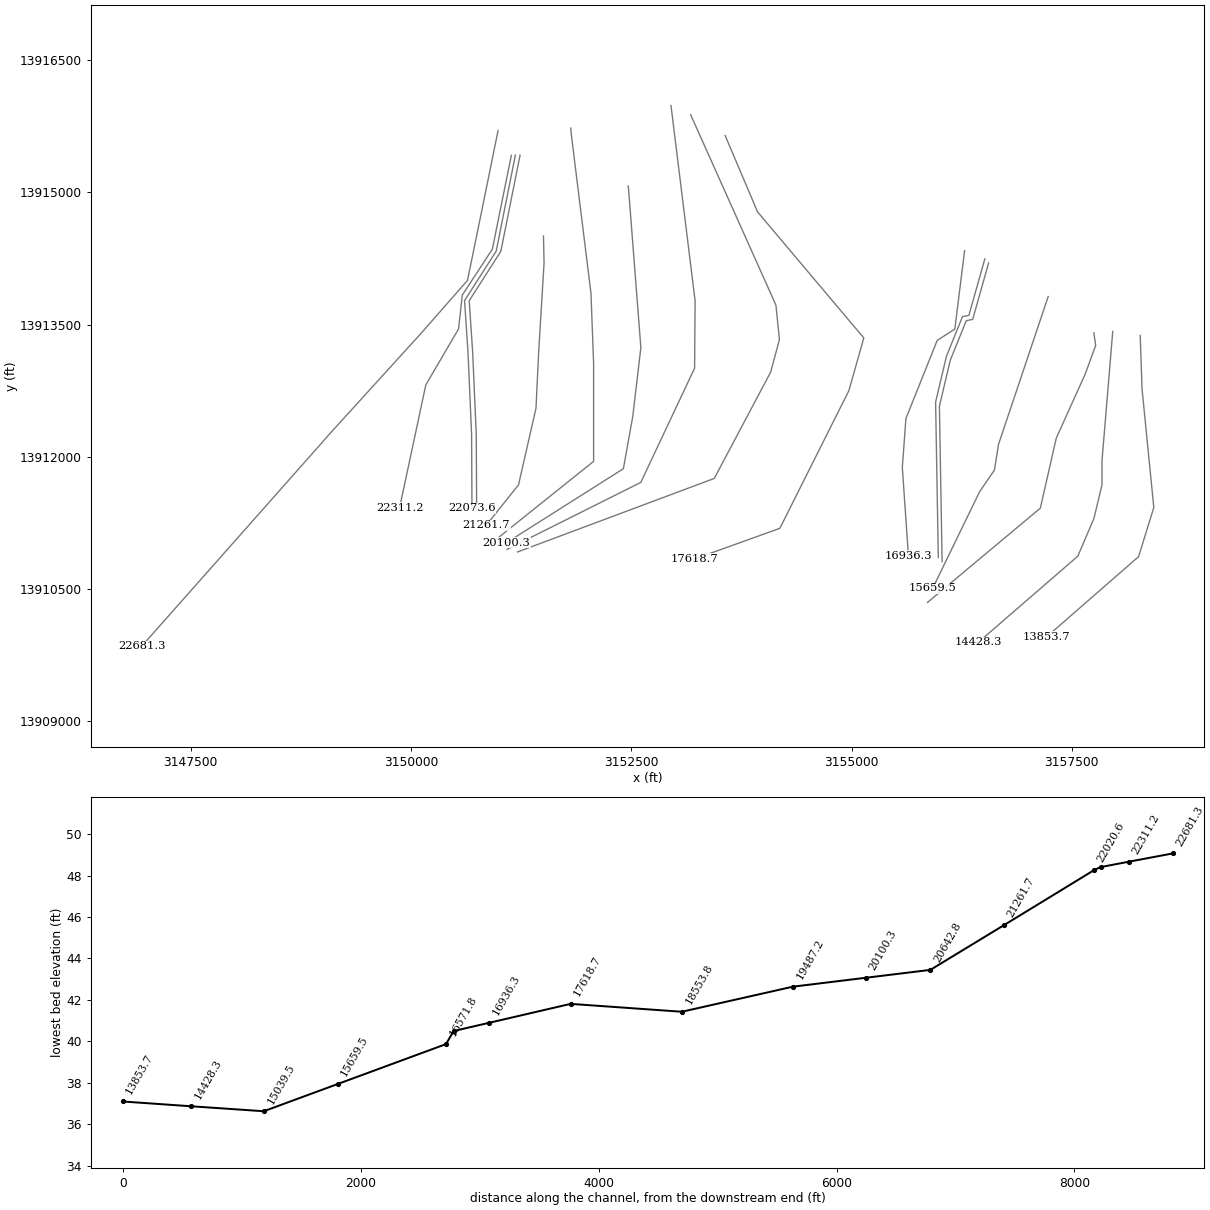
HEC-RAS study P130-00-00.prj: P130-00-00

--- P130-00-00.g01 (geometry) --- (continued)

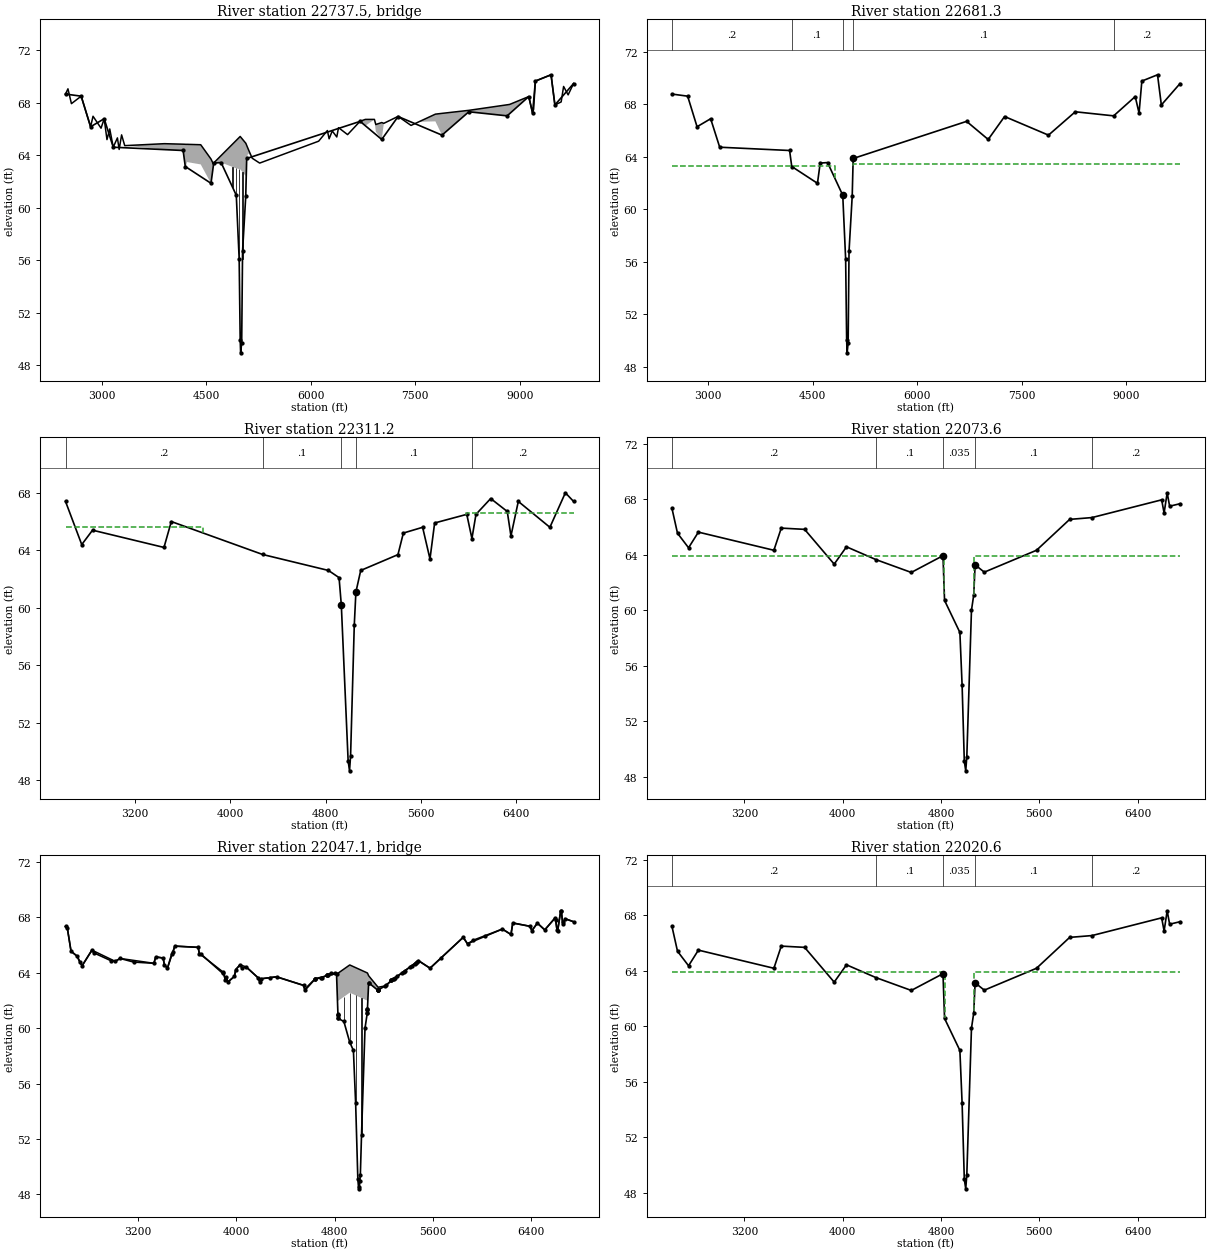
Type RM Length L Ch R = 3 ,22737.5 ,,,
BEGIN DESCRIPTION:
OLD HUMBLE ROAD
Structure ID: P30-10
END DESCRIPTION:
Bridge Culvert--1,0,-1,-1, 0
Deck Dist Width WeirC Skew NumUp NumDn MinLoCord MaxHiCord MaxSubmerge Is_Ogee
10,92.4,2.6,0, 60, 60, , , 0.95, 0, 1,1,,
  2482.4  2517.4  2567.4  2707.4  2842.4  2877.4  2992.4  3037.4  3077.4  3117.4
  3167.4  3227.4  3252.4  3287.4  3332.4  3902.4  3967.4  4170.4  4210.4  4225.4
  4422.9  4570.4  4604.6  4609.4  4989.2 5070.19  5070.3  5082.7  5102.9  5161.8
  5268.8  6115.5  6240.5  6265.5  6310.5  6375.5  6400.5  6530.5  6710.6  6785.6
  6915.6  6935.6  7020.6  7050.6  7255.6  7441.3  7790.6  7885.6  8270.6  8855.6
  9130.6  9185.6  9200.6  9225.6  9450.6  9505.6  9595.6  9630.6  9695.6  9773.4
   68.65   69.05   67.92   68.49   66.16   66.96   66.05   66.77   65.18   65.99
    64.6   65.31   64.43   65.54   64.72   64.87   64.86   64.83   64.82   64.82
   64.79    63.7   63.32    63.4   65.42    64.9    64.9   64.74   64.48   63.76
   63.39   65.06   65.87   65.24   65.84   65.38   66.09   65.56   66.58   66.72
   66.72   66.33   66.48   66.42   66.95   66.26   67.12   67.18   67.41   67.86
   68.46    67.2    67.5   69.64   70.12   67.82   68.05   69.23   68.59   69.45
   68.65   69.05   67.92   68.49   66.16   66.96   66.05   66.77   65.18   65.99
    64.6   65.31   64.43   65.54   64.72   64.41   63.66   64.35   62.84   63.47
   63.29   61.85   62.45   63.39   62.92    62.4   61.14   63.74   64.13   63.08
   63.38   65.02   65.86    65.1   65.83   64.99   66.08   65.55   66.57   66.09
   66.71   65.79   65.19   66.39   66.94   66.25   66.57   65.52    67.3   66.82
   68.46    67.2    67.5   69.64   70.12   67.82   68.05   69.23   68.59   69.45
  2482.4  2517.4  2567.4  2707.4  2842.4  2877.4  2992.4  3037.4  3077.4  3117.4
  3167.4  3227.4  3252.4  3287.4  3332.4  3902.4  3967.4  4170.4  4210.4  4225.4
  4422.9  4570.4  4604.6  4609.4  4989.2 5070.19  5070.3  5082.7  5102.9  5161.8
  5268.8  6115.5  6240.5  6265.5  6310.5  6375.5  6400.5  6530.5  6710.6  6785.6
  6915.6  6935.6  7020.6  7050.6  7255.6  7441.3  7790.6  7885.6  8270.6  8855.6
  9130.6  9185.6  9200.6  9225.6  9450.6  9505.6  9595.6  9630.6  9695.6  9773.4
    68.8    69.2   68.07   68.64   66.31   67.11    66.2   66.92   65.33   66.14
   64.75   65.46   64.58   65.69   64.87   64.87   64.86   64.83   64.82   64.82
   64.79    63.7   63.32   63.54   65.42    64.9    64.9   64.74   64.48   63.76
   63.53   65.17   66.01   65.25   65.98   65.38   66.23    65.7   66.72   66.72
   66.86   66.33   66.48   66.54   67.09    66.4   67.12   67.18   67.45   67.86
   68.61   67.35   67.65   69.79   70.27   67.97    68.2   69.38   68.74    69.6
    68.8    69.2   68.07   68.64   66.31   67.11    66.2   66.92   65.33   66.14
   64.75   65.46   64.58   65.69   64.87   64.56   63.81    64.5   62.99   63.62
   63.44      62    62.6   63.54   63.07   62.55   61.29   63.89   64.28   63.23
   63.53   65.17   66.01   65.25   65.98   65.14   66.23    65.7   66.72   66.24
   66.86   65.94   65.34   66.54   67.09    66.4   66.72   65.67   67.45   66.97
   68.61   67.35   67.65   69.79   70.27   67.97    68.2   69.38   68.74    69.6
Pier Skew, UpSta & Num, DnSta & Num=  ,4878.8, 2 ,4878.8, 2 , 0 , 0 , 0 ,,
     2.7     2.7
   60.54   63.69
     2.7     2.7
   60.69   63.84
Pier Skew, UpSta & Num, DnSta & Num=  ,4926.4, 2 ,4926.4, 2 , 0 , 0 , 0 ,,
     2.7     2.7
   60.13   63.98
     2.7     2.7
   60.27   64.13
Pier Skew, UpSta & Num, DnSta & Num=  ,4974.7, 2 ,4974.7, 2 , 0 , 0 , 0 ,,
     1.7     1.7
   54.71   63.95
     1.7     1.7
   54.86    64.1
Pier Skew, UpSta & Num, DnSta & Num=  ,5022.2, 2 ,5022.2, 2 , 0 , 0 , 0 ,,
     1.7     1.7
   54.51   63.72
     1.7     1.7
   54.66   63.87
Abutment Skew #Up #Dn= , 2 , 2
  4829.8  4830.9
   62.73   62.73
  4829.8  4830.9
   62.88   62.88
Abutment Skew #Up #Dn= , 2 , 2
  5069.1 5070.39
   60.89    62.4
  5069.1 5070.39
   61.04   62.55
BR Coef= 1 , 1 , 0 ,1.25, 0 ,,,0.8,0,2,0,
WSPro=,,,, 1 ,,,, 0 ,,,, 0 ,,,,-1 ,-1 ,-1 , 0 , 0 , 0 , 0 , 0
BR U #Sta/Elev= 30
  2482.4   68.65  2707.4   68.49  2842.4   66.16  3037.4   66.77  3167.4    64.6
  4170.4   64.35  4201.3   63.13  4570.4   61.85  4609.4   63.39  4715.2   63.43
  4933.3   60.94  4974.7   56.09  4989.2   49.94  4995.9   48.93  5010.7   49.68
  5023.3   56.66    5069   60.87  5082.7   63.74  6710.6   66.57  7020.6   65.19
  7255.6   66.94  7885.6   65.52  8270.6    67.3    8821   66.99  9130.6   68.46
  9185.6    67.2  9225.6   69.64  9450.6   70.12  9505.6   67.82  9773.4   69.45
BR U #Mann= 5
  2482.4      .2  4201.3      .1  4933.3    .035  5082.7      .1    8821      .2
BR U Banks=4933.3,5082.7
BR D #Sta/Elev= 30
  2482.4    68.8  2707.4   68.64  2842.4   66.31  3037.4   66.92  3167.4   64.75
  4170.4    64.5  4201.3   63.28  4570.4      62  4609.4   63.54  4715.2   63.58
  4933.3   61.09  4974.7   56.24  4989.2   50.09  4995.9   49.08  5010.7   49.83
  5023.3   56.81    5069   61.02  5082.7   63.89  6710.6   66.72  7020.6   65.34
  7255.6   67.09  7885.6   65.67  8270.6   67.45    8821   67.14  9130.6   68.61
  9185.6   67.35  9225.6   69.79  9450.6   70.27  9505.6   67.97  9773.4    69.6
BR D #Mann= 5
  2482.4      .2  4201.3      .1  4933.3    .035  5082.7      .1    8821      .2
BR D Banks=4933.3,5082.7
BC Design=,, 0 ,, 0 ,,,,,,
BC HTab HWMax=70.12
BC Use User HTab Curves=0
BC User HTab FreeFlow(D)= 0

Type RM Length L Ch R = 1 ,22681.3 ,370.1,370.1,370.1
BEGIN DESCRIPTION:
Downstream Section of Bridge/Culvert/Weir
END DESCRIPTION:
XS GIS Cut Line= 6
      3150988.45     13915700.17      3150783.49      13914692.4
       3150641.2     13913999.84      3150117.12     13913402.85
      3149118.06     13912305.46      3146944.44     13909852.91
#Sta/Elev= 30
  2482.4   68.79  2707.4   68.63  2842.4    66.3  3037.4   66.91  3167.4   64.74
  4170.4   64.49  4201.3   63.27  4570.4   61.99  4609.4   63.53  4715.2   63.57
  4933.3   61.08  4974.7   56.23  4989.2   50.08  4995.9   49.07  5010.7   49.82
  5023.3    56.8    5069   61.01  5082.7   63.88  6710.6   66.71  7020.6   65.33
  7255.6   67.08  7885.6   65.66  8270.6   67.44    8821   67.13  9130.6    68.6
  9185.6   67.34  9225.6   69.78  9450.6   70.26  9505.6   67.96  9773.4   69.59
#Mann= 5 , 1 , 0
  2482.4      .2       0  4201.3      .1       0  4933.3    .035       0
  5082.7      .1       0    8821      .2       0
#XS Ineff= 2 , 0
       0    4820   63.29    5080       0   63.48
Permanent Ineff=
       F       F
Bank Sta=4933.3,5082.7
XS Rating Curve= 0 ,0
Exp/Cntr=0.5,0.3

Type RM Length L Ch R = 1 ,22311.2 ,11.5,237.6,485.8
BEGIN DESCRIPTION:
Cross Section 22311.2 - Interpolated
END DESCRIPTION:
XS GIS Cut Line= 6
      3151139.04     13915417.87      3150923.55      13914354.4
      3150582.37     13913833.64       3150539.9     13913449.91
      3150168.15     13912814.51      3149870.06     13911419.39
#Sta/Elev= 30
  2617.4    67.4  2753.7    64.4  2844.4    65.4    3444    64.2  3505.5      66
  4272.3   63.71  4824.7    62.6  4913.6    62.1  4932.5    60.2  4989.7   49.37
  5001.4   48.67  5010.2    49.7  5041.3    58.8  5054.9    61.1  5095.4    62.6
  5407.9    63.7  5453.2    65.2  5614.9    65.6  5676.7    63.4  5715.8    65.9
  5985.6    66.5  6028.8   64.82  6062.8    66.5  6186.4    67.6  6325.4    66.7
  6356.3      65  6418.1    67.4  6683.2    65.6  6813.2      68  6881.8    67.4
#Mann= 5 , 1 , 0
  2617.4      .2       0  4272.3      .1       0  4932.5    .035       0
  5054.9      .1       0  6028.8      .2       0
#XS Ineff= 2 , 0
       0    3770    65.6    5979       0    66.6
Permanent Ineff=
       F       F
Bank Sta=4932.5,5054.9
XS Rating Curve= 0 ,0
Exp/Cntr=0.5,0.3

Type RM Length L Ch R = 1 ,22073.6 ,53,53,53
BEGIN DESCRIPTION:
Upstream Section of Bridge/Culvert/Weir
END DESCRIPTION:
XS GIS Cut Line= 6
      3151184.83      13915420.8      3150966.87     13914331.05
       3150607.9     13913770.86      3150646.75     13913191.89
       3150687.9     13912253.73      3150692.19     13911414.24
#Sta/Elev= 30
  2610.1   67.35  2655.1   65.56  2745.1   64.51  2825.1   65.64  3439.7   64.33
  3499.7   65.93  3689.7   65.84  3930.6   63.33  4030.6   64.58  4272.3   63.65
  4558.1   62.73  4816.2   63.94  4828.9   60.71  4953.7    58.4  4971.9   54.57
  4989.7   49.11  5001.4   48.41  5010.2   49.44    5048      60  5066.4    61.1
  5077.7   63.28 5152.41   62.75  5577.4   64.33  5847.4   66.56  6028.8   66.69
  6596.1   67.97  6616.1   67.02  6641.1   68.48  6661.1   67.51  6745.6   67.69
#Mann= 5 ,-1 , 0
  2610.1      .2       0  4272.3      .1       0  4816.2    .035       0
  5077.7      .1       0  6028.8      .2       0
#XS Ineff= 2 , 0
       0    4827    63.9    5066       0    63.9
Permanent Ineff=
       F       F
Bank Sta=4816.2,5077.7
XS Rating Curve= 0 ,0
Exp/Cntr=0.5,0.3

Type RM Length L Ch R = 3 ,22047.1 ,,,
BEGIN DESCRIPTION:
MESA ROAD
Structure ID: P30-8
END DESCRIPTION:
Bridge Culvert--1,0,-1,-1, 0
Deck Dist Width WeirC Skew NumUp NumDn MinLoCord MaxHiCord MaxSubmerge Is_Ogee
10,33,2.6,0, 60, 60, , , 0.95, 0, 1,1,,
  2610.1  2625.1  2655.1  2705.1  2745.1  2825.1  3014.7  3054.7  3329.7  3344.7
  3404.7  3414.7  3439.7  3499.7  3689.7  3699.7  3895.6  3910.6  3920.6  3930.6
  3985.6  3995.6  4030.6  4080.6  4180.6  4190.6  4200.6  4328.1  4548.1  4558.1
  4644.4  4816.2 4827.81  4827.9  4923.7 5067.79  5067.9  5077.7  5154.5  5209.2
  5482.4  5577.4  5847.4  5882.4  6166.1  6236.1  6251.1  6391.1  6406.1  6451.1
  6511.1  6596.1  6611.1  6616.1  6641.1  6646.1  6656.1  6661.1  6676.1  6745.6
   67.34   67.21   65.55   65.19    64.5   65.63   64.82   65.03   64.68   65.14
   65.06   64.59   64.32   65.92   65.83   65.38   64.03   63.49   63.66   63.32
   63.74   64.22   64.57   64.42   63.61   63.34   63.56   63.71   63.09   62.82
   63.58   63.94   63.96   63.96   64.56   63.98   63.98   63.78   62.95   63.04
   64.88   64.33   66.56   66.09   67.15   66.76   67.59   67.35   67.03   67.58
   67.09   67.96   67.07   67.01   68.47   68.45   67.64    67.5    67.9   67.68
   67.34   67.21   65.55   65.19    64.5   65.63   64.82   65.03   64.68   65.14
   65.06   64.59   64.32   65.92   65.83   65.38   64.03   63.49   63.66   63.32
   63.74   64.22   64.57   64.42   63.61   63.34   63.56    63.7   63.08   62.72
   63.57   63.93   60.98   61.96   62.56   61.98   61.38   63.27   62.75   63.03
   64.87   64.32   66.55   66.08   67.15   66.76   67.59   67.35   67.03   67.58
   67.09   67.96   67.07   67.01   68.47   68.45   67.64    67.5    67.9   67.68
  2610.1  2625.1  2655.1  2705.1  2745.1  2825.1  3014.7  3054.7  3329.7  3344.7
  3404.7  3414.7  3439.7  3499.7  3689.7  3699.7  3895.6  3910.6  3920.6  3930.6
  3985.6  3995.6  4030.6  4080.6  4180.6  4190.6  4200.6  4328.1  4548.1  4558.1
  4644.4  4816.2 4827.81  4827.9  4923.7 5067.79  5067.9  5077.7  5154.5  5209.2
  5482.4  5577.4  5847.4  5882.4  6166.1  6236.1  6251.1  6391.1  6406.1  6451.1
  6511.1  6596.1  6611.1  6616.1  6641.1  6646.1  6656.1  6661.1  6676.1  6745.6
   67.34   67.21   65.55   65.19    64.5   65.63   64.82   65.03   64.68   65.14
   65.06   64.59   64.32   65.92   65.83   65.38   64.03   63.49   63.66   63.32
   63.74   64.22   64.57   64.42   63.61   63.34   63.56   63.71   63.09   62.82
   63.58   63.94   63.96   63.96   64.56   63.98   63.98   63.78   62.95   63.04
   64.88   64.33   66.56   66.09   67.15   66.76   67.59   67.35   67.03   67.58
   67.09   67.96   67.07   67.01   68.47   68.45   67.64    67.5    67.9   67.68
   67.24   67.11   65.45   65.09    64.4   65.53   64.72   64.93   64.58   65.04
   64.96   64.49   64.22   65.82   65.73   65.28   63.93   63.39   63.56   63.22
   63.64   64.12   64.47   64.32   63.51   63.24   63.46    63.6   62.98   62.62
   63.47   63.83   60.88   61.86   62.46   61.88   61.28   63.17   62.65   62.93
   64.77   64.22   66.45   65.98   67.05   66.66   67.49   67.25   66.93   67.48
   66.99   67.86   66.97   66.91   68.37   68.35   67.54    67.4    67.8   67.58
Pier Skew, UpSta & Num, DnSta & Num=  ,4876, 2 ,4876, 2 , 0 , 0 , 0 ,,
     2.7     2.7
   59.44   63.27
     2.7     2.7
   59.34   63.17
Pier Skew, UpSta & Num, DnSta & Num=  ,4923.7, 2 ,4923.7, 2 , 0 , 0 , 0 ,,
     1.7     1.7
   57.97   63.56
     1.7     1.7
   57.87   63.46
Pier Skew, UpSta & Num, DnSta & Num=  ,4971.9, 2 ,4971.9, 2 , 0 , 0 , 0 ,,
     1.7     1.7
    53.3   63.37
     1.7     1.7
    53.2   63.27
Pier Skew, UpSta & Num, DnSta & Num=  ,5019.7, 2 ,5019.7, 2 , 0 , 0 , 0 ,,
     1.7     1.7
   51.03   63.17
     1.7     1.7
   50.93   63.07
Abutment Skew #Up #Dn= , 2 , 2
  4827.7    4829
   61.96    60.7
  4827.7    4829
   61.86    60.6
Abutment Skew #Up #Dn= , 2 , 2
  5066.4 5067.99
   61.09   61.98
  5066.4 5067.99
   60.99   61.88
BR Coef= 1 , 1 , 0 ,1.25, 0 ,,,0.8,0,2,0,
WSPro=,,,, 1 ,,,, 0 ,,,, 0 ,,,,-1 ,-1 ,-1 , 0 , 0 , 0 , 0 , 0
BR U #Sta/Elev= 122
  2610.1   67.34  2625.1   67.21  2655.1   65.55  2705.1   65.19  2725.1   64.78
  2745.1    64.5  2825.1   65.63  2844.7   65.42  2979.7   64.87  3014.7   64.82
  3054.7   65.03  3164.7   64.77  3329.7   64.68  3344.7   65.14  3404.7   65.06
  3414.7   64.59  3439.7   64.32  3474.7   65.35  3484.7   65.49  3499.7   65.92
  3689.7   65.83  3699.7   65.38  3710.6   65.36  3890.6   63.95  3895.6   64.03
  3910.6   63.49  3920.6   63.66  3930.6   63.32  3985.6   63.74  3995.6   64.22
  4030.6   64.57  4050.6   64.34  4080.6   64.42  4180.6   63.61  4190.6   63.34
  4200.6   63.56  4272.3   63.64  4328.1    63.7  4548.1   63.08  4558.1   62.72
  4641.2   63.54  4644.4   63.57  4644.6   63.57  4693.8   63.62  4696.6   63.63
 4741.79   63.84  4741.9   63.84 4742.01   63.84  4744.1   63.85  4769.5   63.96
  4804.8   63.95  4816.2   63.93  4827.7   61.01 4827.81   60.98  4827.9   60.95
  4828.9    60.7    4829    60.7    4876   60.48  4923.7   58.98  4923.9   58.98
  4953.7   58.39  4971.9   54.56  4989.7    49.1  4995.3   48.51  5001.4    48.4
  5005.7   48.96  5010.2   49.43  5019.7   52.29    5048   59.99  5066.3   61.08
  5066.4   61.09  5067.7   61.34 5067.79   61.36  5067.9   61.38  5077.7   63.27
  5083.5   63.23  5151.7   62.74 5152.19   62.74  5152.3   62.74 5152.41   62.74
  5154.5   62.75  5209.2   63.03    5221   63.09  5262.2   63.45  5262.3   63.45
  5263.1   63.46    5272   63.51    5282   63.57    5292   63.64    5312   63.76
    5352   64.01    5362   64.07    5372   64.14    5417   64.42    5427   64.48
  5452.4   64.64    5462   64.71    5472   64.79  5482.4   64.87  5577.4   64.32
    5667   65.06  5847.4   66.55  5882.4   66.08  5931.1   66.35  6028.8   66.68
  6166.1   67.15  6236.1   66.76  6251.1   67.59  6391.1   67.35  6406.1   67.03
  6451.1   67.58  6511.1   67.09  6596.1   67.96  6601.1   67.81  6611.1   67.07
  6616.1   67.01  6641.1   68.47  6646.1   68.45  6656.1   67.64  6661.1    67.5
  6676.1    67.9  6745.6   67.68
BR U #Mann= 5
  2610.1      .2  4272.3      .1  4816.2    .035  5077.7      .1  6028.8      .2
BR U Banks=4816.2,5077.7
BR D #Sta/Elev= 122
  2610.1   67.24  2625.1   67.11  2655.1   65.45  2705.1   65.09  2725.1   64.68
  2745.1    64.4  2825.1   65.53  2844.7   65.32  2979.7   64.77  3014.7   64.72
  3054.7   64.93  3164.7   64.67  3329.7   64.58  3344.7   65.04  3404.7   64.96
  3414.7   64.49  3439.7   64.22  3474.7   65.25  3484.7   65.39  3499.7   65.82
  3689.7   65.73  3699.7   65.28  3710.6   65.26  3890.6   63.85  3895.6   63.93
  3910.6   63.39  3920.6   63.56  3930.6   63.22  3985.6   63.64  3995.6   64.12
  4030.6   64.47  4050.6   64.24  4080.6   64.32  4180.6   63.51  4190.6   63.24
  4200.6   63.46  4272.3   63.54  4328.1    63.6  4548.1   62.98  4558.1   62.62
  4641.2   63.44  4644.4   63.47  4644.6   63.47  4693.8   63.52  4696.6   63.53
 4741.79   63.74  4741.9   63.74 4742.01   63.74  4744.1   63.75  4769.5   63.86
  4804.8   63.85  4816.2   63.83  4827.7   60.91 4827.81   60.88  4827.9   60.85
  4828.9    60.6    4829    60.6    4876   60.38  4923.7   58.88  4923.9   58.88
  4953.7   58.29  4971.9   54.46  4989.7      49  4995.3   48.41  5001.4    48.3
  5005.7   48.86  5010.2   49.33  5019.7   52.19    5048   59.89  5066.3   60.98
  5066.4   60.99  5067.7   61.24 5067.79   61.26  5067.9   61.28  5077.7   63.17
  5083.5   63.13  5151.7   62.64 5152.19   62.64  5152.3   62.64 5152.41   62.64
  5154.5   62.65  5209.2   62.93    5221   62.99  5262.2   63.35  5262.3   63.35
  5263.1   63.36    5272   63.41    5282   63.47    5292   63.54    5312   63.66
    5352   63.91    5362   63.97    5372   64.04    5417   64.32    5427   64.38
  5452.4   64.54    5462   64.61    5472   64.69  5482.4   64.77  5577.4   64.22
    5667   64.96  5847.4   66.45  5882.4   65.98  5931.1   66.25  6028.8   66.58
  6166.1   67.05  6236.1   66.66  6251.1   67.49  6391.1   67.25  6406.1   66.93
  6451.1   67.48  6511.1   66.99  6596.1   67.86  6601.1   67.71  6611.1   66.97
  6616.1   66.91  6641.1   68.37  6646.1   68.35  6656.1   67.54  6661.1    67.4
  6676.1    67.8  6745.6   67.58
BR D #Mann= 5
  2610.1      .2  4272.3      .1  4816.2    .035  5077.7      .1  6028.8      .2
BR D Banks=4816.2,5077.7
BC Design=,, 0 ,, 0 ,,,,,,
BC HTab HWMax=68.48
BC Use User HTab Curves=0
BC User HTab FreeFlow(D)= 0

Type RM Length L Ch R = 1 ,22020.6 ,758.9,758.9,758.9
BEGIN DESCRIPTION:
Downstream Section of Bridge/Culvert/Weir
END DESCRIPTION:
XS GIS Cut Line= 6
      3151237.81     13915419.47      3151019.85     13914329.73
      3150660.88     13913769.54      3150699.73     13913190.57
      3150740.88     13912252.41      3150745.17     13911412.91
#Sta/Elev= 30
  2610.1   67.21  2655.1   65.42  2745.1   64.37  2825.1    65.5  3439.7   64.19
  3499.7   65.79  3689.7    65.7  3930.6   63.19  4030.6   64.44  4272.3   63.51
  4558.1   62.59  4816.2    63.8  4828.9   60.57  4953.7   58.26  4971.9   54.43
  4989.7   48.97  5001.4   48.27  5010.2    49.3    5048   59.86  5066.4   60.96
  5077.7   63.14 5152.41   62.61  5577.4   64.19  5847.4   66.42  6028.8   66.55
  6596.1   67.83  6616.1   66.88  6641.1   68.34  6661.1   67.37  6745.6   67.55
#Mann= 5 ,-1 , 0
  2610.1      .2       0  4272.3      .1       0  4816.2    .035       0
  5077.7      .1       0  6028.8      .2       0
#XS Ineff= 2 , 0
       0    4829    63.9    5067       0    63.9
Permanent Ineff=
       F       F
Bank Sta=4816.2,5077.7
XS Rating Curve= 0 ,0
Exp/Cntr=0.5,0.3

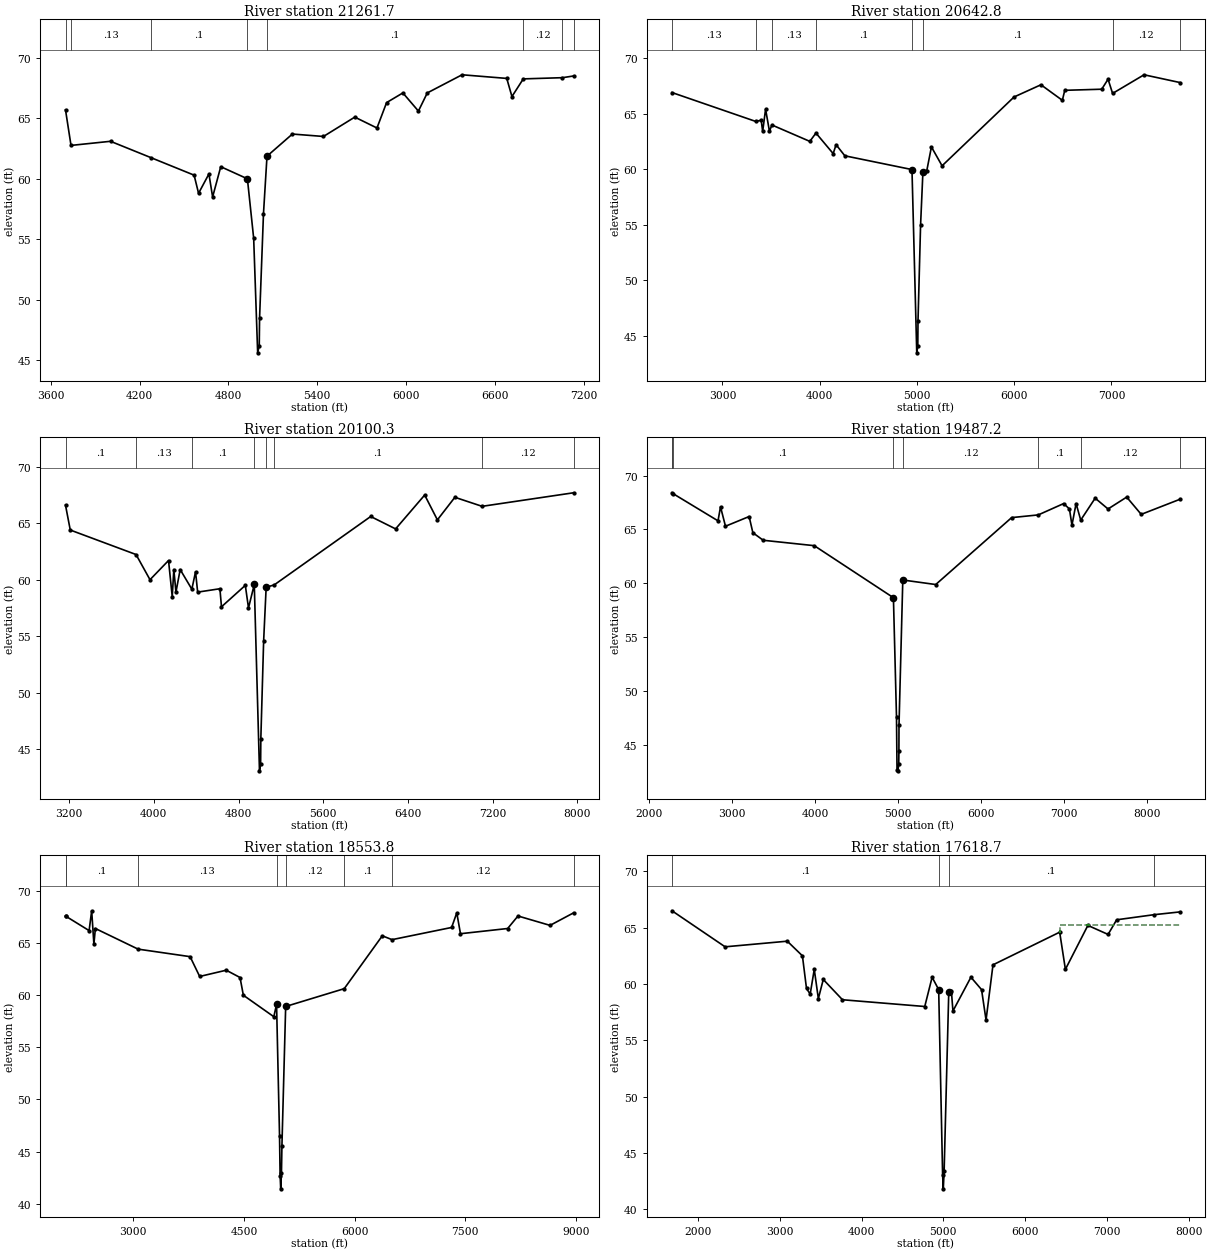
Type RM Length L Ch R = 1 ,21261.7 ,570.6,618.9,634.1
BEGIN DESCRIPTION:
Cross Section 21261.7 - Interpolated
END DESCRIPTION:
XS GIS Cut Line= 6
      3151503.81     13914503.44      3151510.42     13914199.39
      3151449.39     13913192.31      3151418.87     13912551.44
      3151220.51     13911681.69      3150854.29     13911223.93
#Sta/Elev= 30
  3699.2    65.7  3736.4   62.76  4003.3    63.1  4278.3   61.74  4568.3    60.3
  4598.3    58.8  4668.3    60.4  4693.3    58.5  4748.3      61  4928.3      60
  4970.7   55.08  4997.7   45.61  5008.4   46.21  5010.5   48.46    5037   57.12
  5060.8   61.87  5232.3    63.7  5442.3    63.5  5653.9    65.1  5803.9    64.2
  5868.9    66.3  5978.9    67.1  6083.9    65.6  6143.9    67.1  6378.9    68.6
  6680.9    68.3  6715.9    66.8  6792.5   68.26  7057.2   68.36  7132.2    68.5
#Mann= 8 , 1 , 0
  3699.2      .1       0  3736.4     .13       0  4278.3      .1       0
  4928.3    .035       0  5060.8      .1       0  6792.5     .12       0
  7057.2      .1       0  7132.2      .2       0
Bank Sta=4928.3,5060.8
XS Rating Curve= 0 ,0
Exp/Cntr=0.3,0.1

Type RM Length L Ch R = 1 ,20642.8 ,524.6,542.5,505
BEGIN DESCRIPTION:
Cross Section 20642.8
END DESCRIPTION:
XS GIS Cut Line= 6
      3151813.04     13915727.26      3151819.56     13915655.06
      3152042.86     13913853.71      3152072.64     13913064.69
      3152072.64     13911948.15       3150956.1     13911054.92
#Sta/Elev= 30
  2480.9    66.9  3341.2    64.3  3398.4    64.4  3413.4    63.4  3443.4    65.4
  3483.4    63.4  3507.7   63.98  3898.4    62.5  3961.1   63.25  4138.4    61.4
  4168.4    62.2  4258.4    61.2  4948.6   59.96  4997.7   43.45  5008.4   44.05
  5010.5    46.3    5037   54.96  5060.8   59.71  5100.3   59.84  5148.5      62
  5258.1    60.3  5998.1    66.5  6274.6    67.6  6494.6    66.2  6519.6    67.1
  6899.6    67.2  6964.6    68.1  7011.4   66.82  7334.6    68.5  7704.5    67.8
#Mann= 8 , 1 , 0
  2480.9     .13       0  3341.2      .1       0  3507.7     .13       0
  3961.1      .1       0  4948.6    .035       0  5060.8      .1       0
  7011.4     .12       0  7704.5      .2       0
Bank Sta=4948.6,5060.8
XS Rating Curve= 0 ,0
Exp/Cntr=0.3,0.1

Type RM Length L Ch R = 1 ,20100.3 ,681.1,613.1,611.1
BEGIN DESCRIPTION:
Cross Section 20100.3 - Interpolated
END DESCRIPTION:
XS GIS Cut Line= 6
      3152465.29     13915070.48      3152471.73     13915008.11
      3152609.06     13913238.09       3152517.5     13912459.89
      3152410.69      13911864.8      3151083.18     13911025.56
#Sta/Elev= 30
  3166.3    66.6  3211.3    64.4  3832.3   62.23    3964      60    4139    61.7
    4174    58.5    4189    60.9    4209    58.9    4249    60.9  4359.1   59.16
    4394    60.7    4414    58.9    4624    59.2    4639    57.6    4864    59.5
    4894    57.5  4948.6   59.58  4997.7   43.07  5008.4   43.67  5010.5   45.92
    5037   54.58  5060.8   59.33  5136.8   59.54  6047.9    65.6  6282.9    64.5
  6557.5    67.5  6677.5    65.3  6842.5    67.3  7099.6    66.5    7963    67.7
#Mann= 8 , 1 , 0
  3166.3      .1       0  3832.3     .13       0  4359.1      .1       0
  4948.6    .035       0  5060.8     .12       0  5136.8      .1       0
  7099.6     .12       0    7963      .2       0
Bank Sta=4948.6,5060.8
XS Rating Curve= 0 ,0
Exp/Cntr=0.3,0.1

Type RM Length L Ch R = 1 ,19487.2 ,964.2,933.4,828.6
BEGIN DESCRIPTION:
Cross Section 19487.2
END DESCRIPTION:
XS GIS Cut Line= 5
      3152950.98     13915982.57      3153224.59     13913769.61
      3153218.95     13913005.14      3152608.58     13911709.96
      3151090.09     13910950.71
#Sta/Elev= 30
  2276.4    68.4  2287.5   68.33  2831.4    65.8  2861.4    67.1  2921.4    65.3
  3206.4    66.2  3251.4    64.7  3376.4      64  3991.4    63.5  4945.7   58.68
  4982.8   47.62  4989.1    42.7  4999.6   42.64  5009.8   43.23  5011.9   44.52
  5012.9   46.85  5058.7   60.32  5455.7    59.9  6370.7    66.1  6691.7   66.35
  6997.5    67.4  7067.5    66.9  7097.5    65.4  7147.5    67.4  7203.4   65.87
  7377.5    67.9  7532.5    66.9  7757.5      68  7932.5    66.4  8400.2    67.8
#Mann= 8 , 1 , 0
  2276.4      .2       0  2276.4     .13       0  2287.5      .1       0
  4945.7    .035       0  5058.7     .12       0  6691.7      .1       0
  7203.4     .12       0  8400.2      .2       0
Bank Sta=4945.7,5058.7
XS Rating Curve= 0 ,0
Exp/Cntr=0.3,0.1

Type RM Length L Ch R = 1 ,18553.8 ,903.7,935.1,917.9
BEGIN DESCRIPTION:
Cross Section 18553.8
END DESCRIPTION:
XS GIS Cut Line= 6
      3153174.29     13915878.36      3154141.96     13913719.72
      3154181.81     13913329.68      3154082.41     13912960.48
      3153442.26     13911754.62      3151209.18     13910920.94
#Sta/Elev= 30
  2080.3    67.6  2088.6   67.56  2400.3    66.2  2435.3    68.1  2465.3    64.9
  2485.3    66.4  3065.2   64.42    3770    63.7    3900    61.8    4260    62.4
  4447.3    61.7  4492.3      60  4905.4   57.94  4942.8   59.12  4983.2   46.48
  4990.8   42.69  4999.1   41.43  5009.3   42.97  5015.6   45.57  5066.3   58.92
  5860.6   60.63  6376.8    65.7  6508.8   65.33    7317    66.5    7387    67.9
    7437    65.9    8077    66.4    8217    67.6    8652    66.7  8970.6    67.9
#Mann= 9 , 1 , 0
  2080.3      .2       0  2080.3     .13       0  2088.6      .1       0
  3065.2     .13       0  4942.8    .035       0  5066.3     .12       0
  5860.6      .1       0  6508.8     .12       0  8970.6      .2       0
Bank Sta=4942.8,5066.3
XS Rating Curve= 0 ,0
Exp/Cntr=0.3,0.1

Type RM Length L Ch R = 1 ,17618.7 ,886,682.4,680.4
BEGIN DESCRIPTION:
Cross Section 17618.7
END DESCRIPTION:
XS GIS Cut Line= 6
      3153565.84     13915642.58      3153933.54     13914776.71
       3155139.4     13913347.54      3154969.82     13912749.55
      3154186.62      13911188.9      3153217.21     13910841.03
#Sta/Elev= 30
  1680.2    66.5  2330.2    63.3  3090.9    63.8  3275.9    62.5  3325.9    59.6
  3370.9    59.1  3420.9    61.3  3470.9    58.7  3530.9    60.4  3765.9    58.6
  4772.5      58  4862.5    60.6  4942.8    59.5  4990.8   43.07  4999.2   41.81
  5009.3   43.35  5066.2    59.3  5098.5   59.35  5117.2    57.6  5337.2    60.6
  5467.2    59.5  5522.2    56.8  5607.2    61.7  6422.9    64.6  6492.9    61.3
  6767.9    65.2    7015    64.4    7120    65.7  7574.9   66.15    7895    66.4
#Mann= 4 , 1 , 0
  1680.2      .1       0  4942.8    .035       0  5066.2      .1       0
  7574.9     .12       0
#XS Ineff= 2 , 0
       0                    6424       0   65.25
Permanent Ineff=
       F       F
Bank Sta=4942.8,5066.2
XS Rating Curve= 0 ,0
Exp/Cntr=0.3,0.1

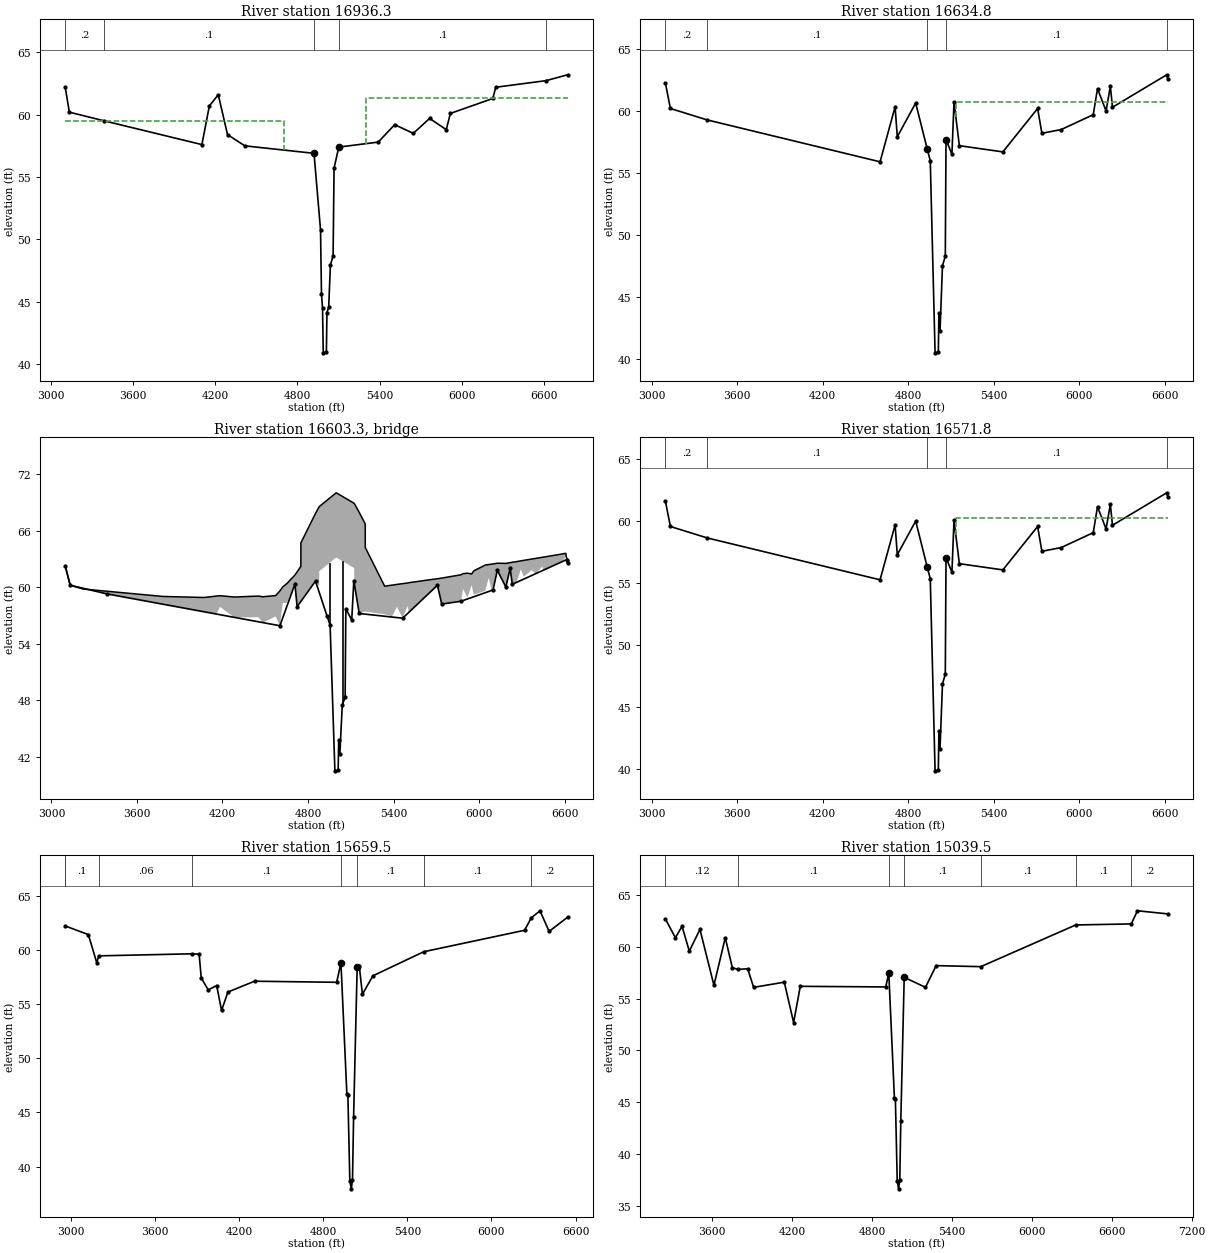
Type RM Length L Ch R = 1 ,16936.3 ,150.9,301.5,397.8
BEGIN DESCRIPTION:
Cross Section 16936.3 - Interpolated
END DESCRIPTION:
XS GIS Cut Line= 6
      3156283.36     13914337.53      3156172.54     13913448.25
      3155972.24     13913319.43      3155617.29     13912433.64
      3155576.58     13911878.56      3155646.15     13910875.18
#Sta/Elev= 30
    3107    62.2  3137.1    60.2  3389.5   59.51  4103.6    57.6  4157.8    60.7
  4222.9    61.6  4290.4    58.4  4416.6    57.5    4921    56.9  4968.4   50.77
  4975.4   45.64    4983   44.49  4988.4    40.9  5011.2   40.95  5015.2   44.13
  5028.1   44.56  5040.3   47.92  5060.1   48.69  5067.1    55.7  5101.3    57.4
  5388.9    57.8  5509.3    59.2  5644.7    58.5  5763.8    59.7  5885.1    58.8
  5915.2    60.1  6224.9    61.3    6246    62.2  6613.4   62.73  6769.5    63.2
#Mann= 5 , 1 , 0
    3107      .2       0  3389.5      .1       0    4921    .035       0
  5101.3      .1       0  6613.4      .2       0
#XS Ineff= 2 , 0
       0    4700    59.5    5300       0    61.3
Permanent Ineff=
       F       F
Bank Sta=4921,5101.3
XS Rating Curve= 0 ,0
Exp/Cntr=0.5,0.3

Type RM Length L Ch R = 1 ,16634.8 ,63,63,63
BEGIN DESCRIPTION:
Upstream Section of Bridge/Culvert/Weir
END DESCRIPTION:
XS GIS Cut Line= 6
      3156512.85     13914243.45      3156331.96     13913603.84
       3156259.6     13913589.37       3156078.4     13913143.23
      3155954.29     13912620.52      3155984.94      13910858.2
#Sta/Elev= 30
    3097   62.26    3132   60.21  3389.5   59.29  4602.6   55.91    4708   60.34
  4723.4   57.93  4852.4   60.65  4933.3   56.94  4954.7   55.99  4988.4    40.5
  5011.2   40.55  5015.2   43.73  5022.9   42.25  5040.3   47.52  5060.1   48.29
  5065.2    57.7  5106.6   56.52  5121.1   60.71  5158.8   57.21  5463.7   56.71
  5707.6   60.21  5737.6   58.21  5872.6   58.51  6097.6   59.71  6127.6   61.81
  6187.6   60.01  6217.6   62.01  6232.6   60.31  6613.4   62.93  6620.1   62.61
#Mann= 5 , 1 , 0
    3097      .2       0  3389.5      .1       0  4933.3    .035       0
  5065.2      .1       0  6613.4      .2       0
#XS Ineff= 2 , 0
       0    4868   59.08    5134       0    60.7
Permanent Ineff=
       F       F
Bank Sta=4933.3,5065.2
XS Rating Curve= 0 ,0
Exp/Cntr=0.5,0.3

Type RM Length L Ch R = 3 ,16603.3 ,,,
BEGIN DESCRIPTION:
WILSON ROAD
Structure ID: P30-7
END DESCRIPTION:
Bridge Culvert--1,0,-1,-1, 0
Deck Dist Width WeirC Skew NumUp NumDn MinLoCord MaxHiCord MaxSubmerge Is_Ogee
10,43,2.6,0, 60, 60, , , 0.95, 0, 1,1,,
    3097    3132    3222  3782.6  4070.8  4157.6  4182.6  4282.6  4452.2  4482.6
  4572.9  4602.6  4622.6  4652.2    4708  4723.4 4749.69  4749.8  4852.4  4878.3
 4878.41  4878.5  4997.7 5123.79  5123.9  5158.8  5201.4 5201.51  5337.4  5388.7
  5423.7  5463.7  5497.6  5507.6  5647.6  5707.6  5737.6  5872.6  5887.6  5917.6
  5947.6  5962.6  6042.6  6067.6  6087.6  6127.6  6187.6  6217.6  6232.6  6262.6
  6292.6  6312.6  6367.6  6397.6  6442.6  6452.6  6547.6  6577.6  6607.6  6620.1
   62.25    60.2    59.8   59.01    58.9   59.05   59.09   58.95   59.05   58.98
    59.1    59.6   60.02   60.39   61.28   61.62    62.2    64.7   67.83   68.55
   68.55   68.55   70.02    68.9    68.9   67.94   66.71   64.21    60.1   60.21
   60.29   60.37   60.44   60.47   60.77   60.89   60.96   61.31   61.43   61.48
    61.4   61.73   62.34    62.4   62.44   62.54   62.52    62.6   62.64   62.71
   62.79   62.84   62.98   63.05   63.17   63.19   63.43   63.51   63.59    62.6
   62.25    60.2    59.8    57.5   57.31    56.8    57.9    56.5    56.8      56
   56.89    55.9   58.32   58.34   60.33   57.92   58.54   58.54   60.64   60.08
   60.07   61.68   63.15   62.03   60.44    57.2    57.4    57.4   57.11    56.9
    57.9    56.7      58      57    57.7    60.2    58.2    58.5    59.8    58.9
    60.2    59.2    59.6      61    59.6    61.8      60      62    60.3    60.4
    61.9    61.1    61.8    61.2    62.2    61.2    61.1    61.5    63.2    62.6
    3097    3132    3222  3782.6  4070.8  4157.6  4182.6  4282.6  4452.2  4482.6
  4572.9  4602.6  4622.6  4652.2    4708  4723.4 4749.69  4749.8  4852.4  4878.3
 4878.41  4878.5  4997.7 5123.79  5123.9  5158.8  5201.4 5201.51  5337.4  5388.7
  5423.7  5463.7  5497.6  5507.6  5647.6  5707.6  5737.6  5872.6  5887.6  5917.6
  5947.6  5962.6  6042.6  6067.6  6087.6  6127.6  6187.6  6217.6  6232.6  6262.6
  6292.6  6312.6  6367.6  6397.6  6442.6  6452.6  6547.6  6577.6  6607.6  6620.1
   62.25    60.2    59.8   59.01    58.9   59.05   59.09   58.95   59.05   58.98
    59.1    59.6   60.02   60.39   61.28   61.62    62.2    64.7   67.83   68.55
   68.55   68.55   70.02    68.9    68.9   67.94   66.71   64.21    60.1   60.21
   60.29   60.37   60.44   60.47   60.77   60.89   60.96   61.31   61.43   61.48
    61.4   61.73   62.34    62.4   62.44   62.54   62.52    62.6   62.64   62.71
   62.79   62.84   62.98   63.05   63.17   63.19   63.43   63.51   63.59    62.6
   61.65    59.6    59.2    56.9   56.71    56.2    57.3    55.9    56.2    55.4
   56.29    55.3   57.72   57.74   59.73   57.32   57.94   57.94   60.04   59.48
   59.47   61.08   62.55   61.43   59.84    56.6    56.8    56.8   56.51    56.3
    57.3    56.1    57.4    56.4    57.1    59.6    57.6    57.9    59.2    58.3
    59.6    58.6      59    60.4      59    61.2    59.4    61.4    59.7    59.8
    61.3    60.5    61.2    60.6    61.6    60.6    60.5    60.9    62.6      62
Pier Skew, UpSta & Num, DnSta & Num=  ,4951.8, 2 ,4951.8, 2 , 0 , 0 , 0 ,,
       3       3
   55.11   63.79
       3       3
   54.51   63.19
Pier Skew, UpSta & Num, DnSta & Num=  ,5040.3, 2 ,5040.3, 2 , 0 , 0 , 0 ,,
       3       3
    46.1   64.03
       3       3
    45.5   63.43
Abutment Skew #Up #Dn= , 2 , 2
  4878.3  4880.5
   61.68      60
  4878.3  4880.5
   61.08    59.4
Abutment Skew #Up #Dn= , 2 , 2
  5121.1 5123.99
    60.7   62.03
  5121.1 5123.99
    60.1   61.43
BR Coef= 1 , 1 , 0 ,1.25, 0 ,,,0.8,0,2,0,
WSPro=,,,, 1 ,,,, 0 ,,,, 0 ,,,,-1 ,-1 ,-1 , 0 , 0 , 0 , 0 , 0
BR U #Sta/Elev= 30
    3097   62.25    3132    60.2  3389.5   59.28  4602.6    55.9    4708   60.33
  4723.4   57.92  4852.4   60.64  4933.3   56.93  4954.7   55.98  4988.4   40.49
  5011.2   40.54  5015.2   43.72  5022.9   42.24  5040.3   47.51  5060.1   48.28
  5065.2   57.69  5106.6   56.51  5121.1    60.7  5158.8    57.2  5463.7    56.7
  5707.6    60.2  5737.6    58.2  5872.6    58.5  6097.6    59.7  6127.6    61.8
  6187.6      60  6217.6      62  6232.6    60.3  6613.4   62.92  6620.1    62.6
BR U #Mann= 5
    3097      .2  3389.5      .1  4933.3    .035  5065.2      .1  6613.4      .2
BR U Banks=4933.3,5065.2
BR D #Sta/Elev= 30
    3097   61.65    3132    59.6  3389.5   58.68  4602.6    55.3    4708   59.73
  4723.4   57.32  4852.4   60.04  4933.3   56.33  4954.7   55.38  4988.4   39.89
  5011.2   39.94  5015.2   43.12  5022.9   41.64  5040.3   46.91  5060.1   47.68
  5065.2   57.09  5106.6   55.91  5121.1    60.1  5158.8    56.6  5463.7    56.1
  5707.6    59.6  5737.6    57.6  5872.6    57.9  6097.6    59.1  6127.6    61.2
  6187.6    59.4  6217.6    61.4  6232.6    59.7  6613.4   62.32  6620.1      62
BR D #Mann= 5
    3097      .2  3389.5      .1  4933.3    .035  5065.2      .1  6613.4      .2
BR D Banks=4933.3,5065.2
BC Design=,, 0 ,, 0 ,,,,,,
BC HTab HWMax=63.21
BC Use User HTab Curves=0
BC User HTab FreeFlow(D)= 0

Type RM Length L Ch R = 1 ,16571.8 ,912.3,912.3,912.3
BEGIN DESCRIPTION:
Downstream Section of Bridge/Culvert/Weir
END DESCRIPTION:
XS GIS Cut Line= 6
      3156556.01     13914197.55      3156375.12     13913557.94
      3156302.76     13913543.47      3156121.56     13913097.33
      3155997.45     13912574.62       3156028.1      13910812.3
#Sta/Elev= 30
    3097   61.63    3132   59.58  3389.5   58.66  4602.6   55.28    4708   59.71
  4723.4    57.3  4852.4   60.02  4933.3   56.31  4954.7   55.36  4988.4   39.87
  5011.2   39.92  5015.2    43.1  5022.9   41.62  5040.3   46.89  5060.1   47.66
  5065.2   57.07  5106.6   55.89  5121.1   60.08  5158.8   56.58  5463.7   56.08
  5707.6   59.58  5737.6   57.58  5872.6   57.88  6097.6   59.08  6127.6   61.18
  6187.6   59.38  6217.6   61.38  6232.6   59.68  6613.4    62.3  6620.1   61.98
#Mann= 5 , 1 , 0
    3097      .2       0  3389.5      .1       0  4933.3    .035       0
  5065.2      .1       0  6613.4      .2       0
#XS Ineff= 2 , 0
       0    4868   58.95    5134       0    60.3
Permanent Ineff=
       F       F
Bank Sta=4933.3,5065.2
XS Rating Curve= 0 ,0
Exp/Cntr=0.5,0.3

Type RM Length L Ch R = 1 ,15659.5 ,615.5,620,680.5
BEGIN DESCRIPTION:
Cross Section 15659.5 - Interpolated
END DESCRIPTION:
XS GIS Cut Line= 5
      3157232.47     13913817.92      3156667.89     13912139.45
      3156622.12     13911849.54      3156454.27      13911605.4
      3155920.21     13910506.76
#Sta/Elev= 30
  2960.4    62.2  3125.4    61.4  3185.4    58.8  3199.4   59.44  3866.1   59.63
  3915.4    59.6  3930.4    57.4  3980.4    56.3  4040.4    56.7  4075.4    54.4
  4120.4    56.1  4310.4    57.1  4896.3      57  4926.6    58.8  4968.9   46.69
  4976.1    46.6    4990   38.68  5000.5   37.94    5009   38.76  5016.8   44.54
  5042.3   58.38    5057   58.53  5079.8    55.9  5154.8    57.6    5517   59.82
  6236.1    61.8  6283.5   62.94  6346.1    63.6  6411.1    61.7  6542.6      63
#Mann= 8 , 1 , 0
  2960.4      .2       0  2960.4      .1       0  3199.4     .06       0
  3866.1      .1       0  4926.6    .035       0  5042.3      .1       0
    5517      .1       0  6283.5      .2       0
Bank Sta=4926.6,5042.3
XS Rating Curve= 0 ,0
Exp/Cntr=0.3,0.1

Type RM Length L Ch R = 1 ,15039.5 ,513.8,611.2,625.9
BEGIN DESCRIPTION:
Cross Section 15039.5
END DESCRIPTION:
XS GIS Cut Line= 6
      3157750.07      13913405.8      3157771.23     13913262.98
      3157653.43       13912941.       3157323.6     13912210.66
      3157142.98     13911417.49      3155862.91     13910349.46
#Sta/Elev= 30
  3250.2    62.7  3325.2    60.9  3375.2      62  3429.5    59.6  3509.5    61.7
  3614.5    56.3  3699.5    60.9  3752.4      58  3795.3   57.83  3867.4    57.9
  3912.4    56.1  4142.4    56.6  4212.4    52.7  4262.4    56.2  4903.9   56.14
  4926.6   57.49  4968.9   45.38  4976.1   45.29    4990   37.37  5000.5   36.63
    5009   37.45  5016.8   43.23  5042.3   57.07    5202    56.1    5282    58.2
    5617    58.1  6329.5   62.13  6746.2   62.23  6792.8    63.5  7019.9    63.2
#Mann= 7 , 1 , 0
  3250.2     .12       0  3795.3      .1       0  4926.6    .035       0
  5042.3      .1       0    5617      .1       0  6329.5      .1       0
  6746.2      .2       0
Bank Sta=4926.6,5042.3
XS Rating Curve= 0 ,0
Exp/Cntr=0.3,0.1

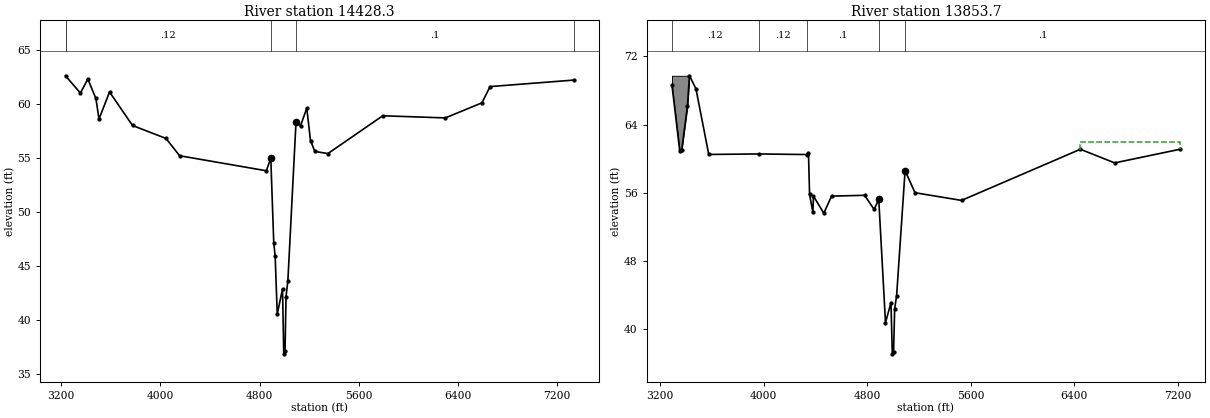
Type RM Length L Ch R = 1 ,14428.3 ,491.4,574.6,662.4
BEGIN DESCRIPTION:
Cross Section 14428.3 - Interpolated
END DESCRIPTION:
XS GIS Cut Line= 6
      3157964.89     13913421.19      3157842.82     13911956.35
      3157842.82     13911681.69      3157751.27     13911300.22
      3157568.16     13910872.97      3156439.01     13909896.41
#Sta/Elev= 30
  3236.4    62.6  3356.4      61  3416.4    62.3  3481.4    60.5  3506.4    58.6
  3591.4    61.1  3776.4      58  4046.4    56.8  4156.4    55.2  4855.2   53.81
  4890.8   54.99  4914.8   47.15  4926.3   45.89  4942.9   40.54  4985.4   42.88
  4995.4   36.87  5005.6   37.14  5013.7   42.16  5028.7   43.65  5094.3   58.36
  5130.8   57.98    5181    59.6    5211    56.6    5246    55.6    5351    55.4
  5793.3    58.9  6298.1    58.7  6593.1    60.1  6658.1    61.6    7331    62.2
#Mann= 5 , 1 , 0
  3236.4      .2       0  3236.4     .12       0  4890.8    .035       0
  5094.3      .1       0    7331      .2       0
Bank Sta=4890.8,5094.3
XS Rating Curve= 0 ,0
Exp/Cntr=0.3,0.1

Type RM Length L Ch R = 1 ,13853.7 ,851.7,551.2,271.1
BEGIN DESCRIPTION:
Cross Section 13853.7
END DESCRIPTION:
XS GIS Cut Line= 5
      3158276.42     13913376.45      3158297.39     13912768.23
      3158430.89     13911425.34      3158258.12     13910867.77
      3157213.85     13909957.85
#Sta/Elev= 30
  3292.5    68.6  3352.5    60.9  3367.5      61  3412.5    66.2 3427.29   69.72
 3477.67   68.21 3576.77   60.49  3962.1   60.55    4333   60.48 4347.63   60.64
  4356.1    55.8 4381.55   53.69  4386.1    55.6  4466.1    53.6  4526.1    55.6
  4781.1    55.7  4855.2   54.04  4890.8   55.22  4942.9   40.77  4985.4   43.11
  4995.4    37.1  5005.6   37.37  5013.7   42.39  5028.7   43.88  5094.3   58.59
  5171.1      56  5530.6    55.1  6449.4    61.1  6714.4    59.5  7219.4    61.1
#Mann= 5 ,-1 , 0
  3292.5     .12       0  3962.1     .12       0    4333      .1       0
  4890.8    .035       0  5094.3      .1       0
#XS Ineff= 2 , 0
       0                    6445       0      62
Permanent Ineff=
       F       F
#Block Obstruct= 1 ,-1
  3292.5 3427.29   69.72
Bank Sta=4890.8,5094.3
XS Rating Curve= 0 ,0
Exp/Cntr=0.3,0.1