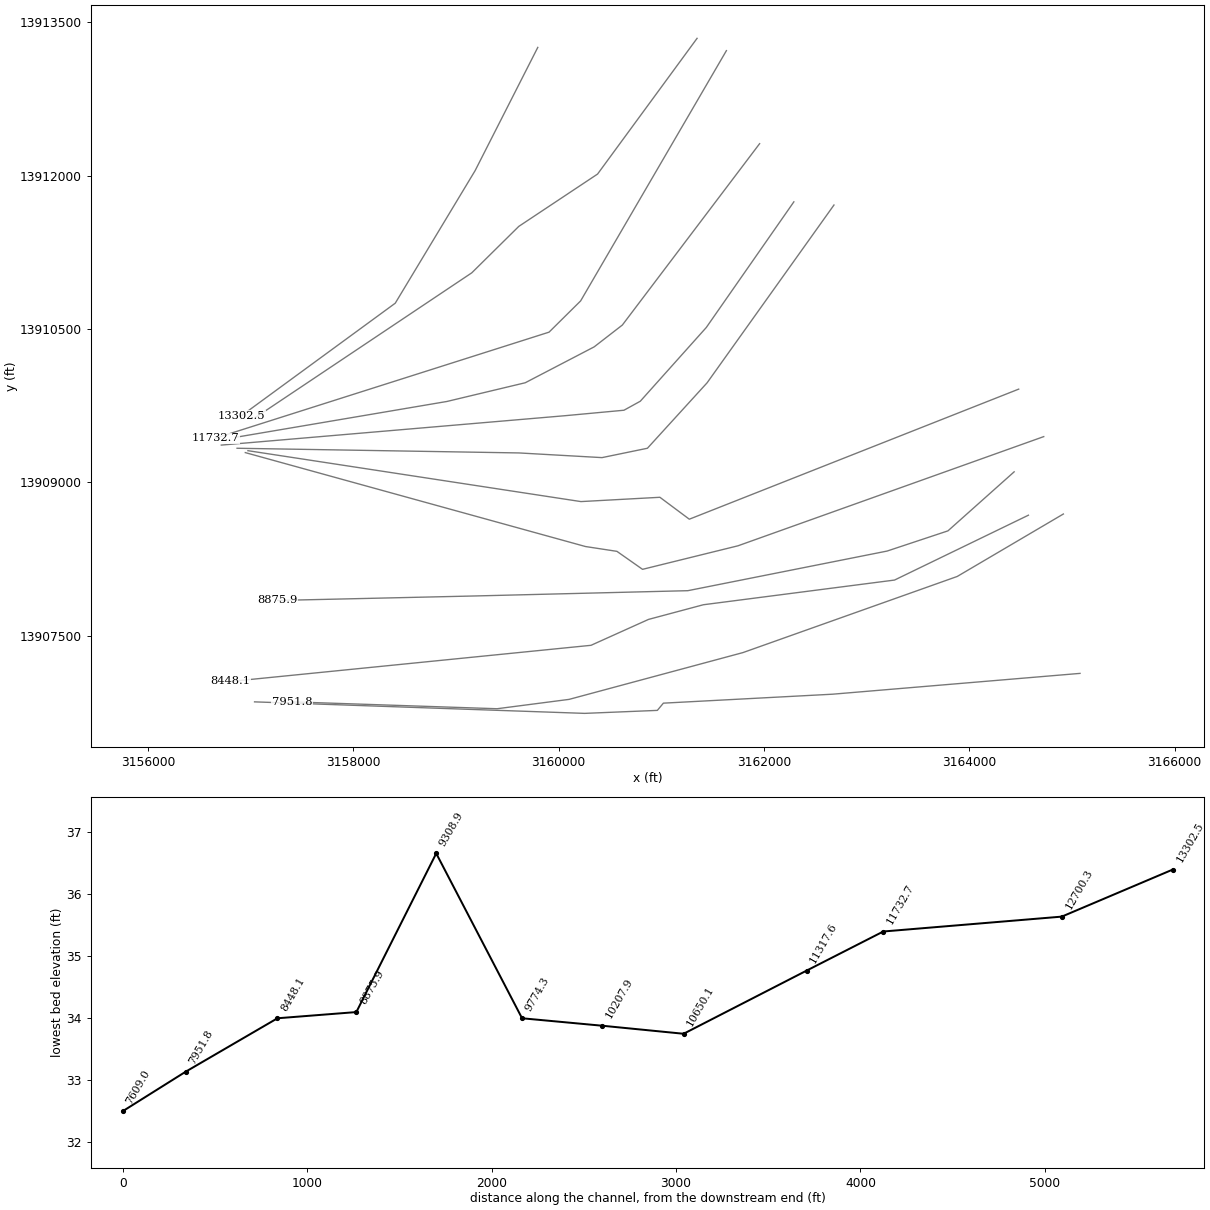
HEC-RAS study P130-00-00.prj: P130-00-00

--- P130-00-00.g01 (geometry) --- (continued)

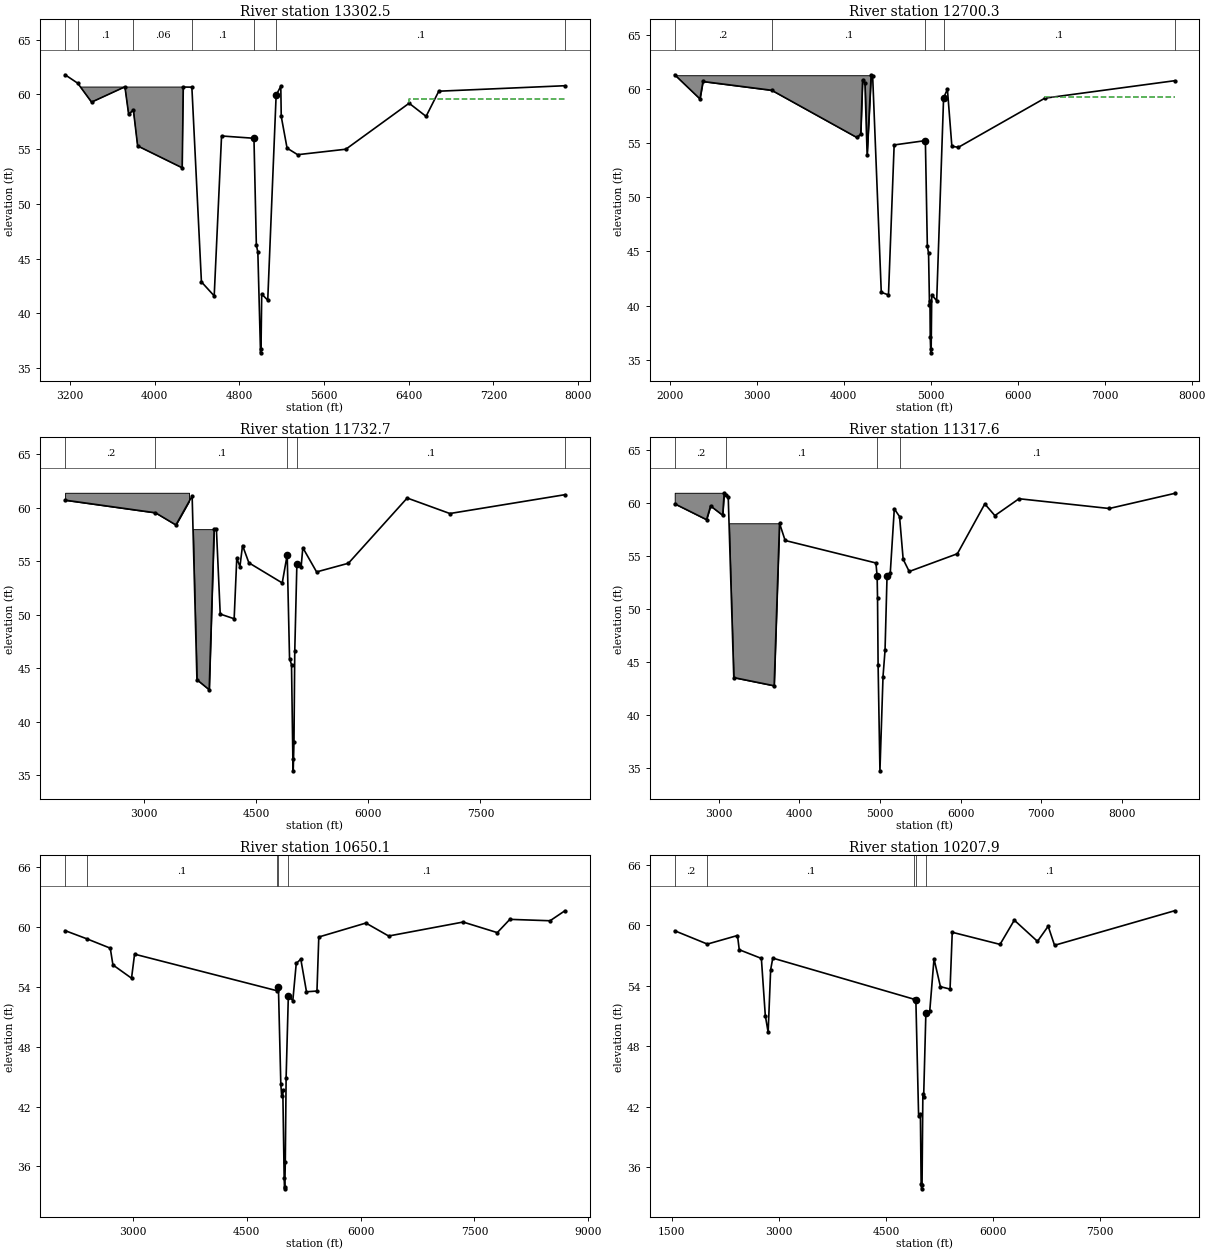
Type RM Length L Ch R = 1 ,13302.5 ,763.2,602.2,332.6
BEGIN DESCRIPTION:
Cross Section 13302.5 - Interpolated
END DESCRIPTION:
XS GIS Cut Line= 5
      3159795.95     13913253.35      3159185.59      13912047.9
      3158956.71     13911666.43       3158407.4      13910750.9
      3156912.03     13909652.27
#Sta/Elev= 30
    3155    61.8  3274.2   61.03    3405    59.3    3720    60.7    3755    58.2
    3800   58.57    3840    55.3    4261    53.3 4271.06   60.68 4352.17   60.67
 4442.39   42.88    4563    41.6 4632.39   56.21  4938.4      56    4961   46.25
  4975.1    45.6  5000.4    36.4    5005   36.73  5011.7   41.77  5068.5   41.21
  5147.8   59.94  5191.8   60.75    5196      58    5251    55.1    5351    54.5
    5806      55  6403.7    59.2  6563.7      58  6683.7    60.3  7874.3    60.8
#Mann= 7 ,-1 , 0
    3155      .2       0  3274.2      .1       0    3800     .06       0
 4352.17      .1       0  4938.4    .035       0  5147.8      .1       0
  7874.3      .2       0
#XS Ineff= 2 , 0
       0                    6405       0    59.6
Permanent Ineff=
       F       F
#Block Obstruct= 1 ,-1
    3155 4271.06   60.68
Bank Sta=4938.4,5147.8
XS Rating Curve= 0 ,0
Exp/Cntr=0.3,0.1

Type RM Length L Ch R = 1 ,12700.3 ,854.5,967.6,956.7
BEGIN DESCRIPTION:
Cross Section 12700.3
END DESCRIPTION:
XS GIS Cut Line= 5
      3161347.81     13913342.07      3160378.47     13912014.33
      3159610.88     13911502.26      3159153.38     13911048.39
      3157048.74     13909634.83
#Sta/Elev= 30
  2056.4   61.32  2346.4   59.09  2381.4    60.7  3171.2   59.89  4150.3   55.53
  4195.3   55.85 4216.51   60.83 4243.35   60.56 4268.72   53.93 4314.78   61.28
 4332.21    61.2  4431.4   41.23 4514.16   40.99  4579.4   54.84  4938.4   55.24
    4961   45.49  4975.1   44.84  4985.8   40.04  4991.2   40.46  4994.3   37.12
  5000.4   35.64    5005   35.97  5011.7   41.01  5068.5   40.45  5147.8   59.18
  5191.8   59.99    5243   54.72  5317.5   54.62  6312.5   59.16  7802.8   60.77
#Mann= 5 ,-1 , 0
  2056.4      .2       0  3171.2      .1       0  4938.4    .035       0
  5147.8      .1       0  7802.8      .2       0
#XS Ineff= 2 , 0
       0                    6315       0    59.3
Permanent Ineff=
       F       F
#Block Obstruct= 1 ,-1
  2056.4 4314.78   61.28
Bank Sta=4938.4,5147.8
XS Rating Curve= 0 ,0
Exp/Cntr=0.3,0.1

Type RM Length L Ch R = 1 ,11732.7 ,415.2,415.1,378.2
BEGIN DESCRIPTION:
Cross Section 11732.7
END DESCRIPTION:
XS GIS Cut Line= 4
      3161633.64     13913221.72      3160213.56     13910773.53
      3159905.78     13910467.69      3156656.08     13909430.64
#Sta/Elev= 30
  1951.7   60.71  3158.4   59.53  3431.7   58.39  3648.7    61.1  3712.7   43.92
  3876.7   42.98  3942.2   57.98  3972.7      58  4023.7   50.06  4209.7   49.62
  4244.7   55.29  4286.7   54.49  4321.7   56.47  4406.7   54.85  4851.9   52.97
  4918.2    55.6  4949.7   45.88  4975.9   45.33  4993.9   36.47  4998.7    35.4
  5008.7   38.08  5019.2   46.56  5047.5   54.73  5103.5   54.42  5126.9   56.26
  5310.8      54  5735.8   54.81  6520.8   60.91  7090.8   59.46    8627   61.22
#Mann= 5 ,-1 , 0
  1951.7      .2       0  3158.4      .1       0  4918.2    .035       0
  5047.5      .1       0    8627      .2       0
#Block Obstruct= 2 ,-1
  1951.7  3606.7    61.4  3606.7  3972.7      58
Bank Sta=4918.2,5047.5
XS Rating Curve= 0 ,0
Exp/Cntr=0.3,0.1

Type RM Length L Ch R = 1 ,11317.6 ,677.2,667.5,461.2
BEGIN DESCRIPTION:
Cross Section 11317.6 - Interpolated
END DESCRIPTION:
XS GIS Cut Line= 6
      3161957.08     13912311.57      3160619.92     13910537.28
      3160345.26     13910323.66      3159673.88     13909972.71
      3158910.94      13909789.6        3156851.     13909438.65
#Sta/Elev= 30
  2452.3   59.91  2847.3   58.42  2897.3   59.71  3047.3   58.83  3066.3   60.95
  3091.8   60.75  3116.3   60.56  3185.3   43.55  3686.3   42.78  3752.8   58.08
  3822.3   56.46    4949   54.34    4964   53.09    4969      51    4976    44.7
  4998.7   34.77    5037   43.65    5062   46.11    5087   53.13    5127    53.4
    5177   59.44    5242   58.71    5287   54.69    5362   53.54  5959.6   55.21
    6300    59.9    6425    58.8  6724.2   60.39  7844.2   59.47  8653.8   60.89
#Mann= 4 ,-1 , 0
  2452.3      .2       0  3091.8      .1       0    4964    .035       0
    5242      .1       0
#Block Obstruct= 2 ,-1
  2452.3    3066   60.95    3066    3752   58.08
Bank Sta=4964,5087
XS Rating Curve= 0 ,0
Exp/Cntr=0.3,0.1

Type RM Length L Ch R = 1 ,10650.1 ,365.4,442.2,357
BEGIN DESCRIPTION:
Cross Section 10650.1
END DESCRIPTION:
XS GIS Cut Line= 6
      3162290.74      13911742.5      3161438.07     13910513.84
      3160794.69     13909791.89      3160635.78     13909703.85
      3160065.32     13909650.67      3156712.73     13909362.81
#Sta/Elev= 30
  2108.7   59.64  2398.3   58.81  2703.7   57.88  2738.7    56.2  2983.7   54.87
  3023.7   57.28  4901.3   53.61  4918.3   53.96  4949.8   44.23  4961.2   43.05
    4976   43.68  4993.9   34.82  4998.7   33.75  5002.4   33.98  5008.7   36.44
  5019.6   44.91  5048.9   53.09  5107.9   52.63  5152.9   56.35  5212.9   56.78
  5287.9   53.51  5425.8   53.58    5450      59    6070    60.4    6370    59.1
  7350.8    60.5  7800.8   59.44  7965.8   60.77  8495.8   60.63  8690.8   61.63
#Mann= 5 ,-1 , 0
  2108.7      .2       0  2398.3      .1       0  4901.3      .1       0
  4918.3    .035       0  5048.9      .1       0
Bank Sta=4918.3,5048.9
XS Rating Curve= 0 ,0
Exp/Cntr=0.3,0.1

Type RM Length L Ch R = 1 ,10207.9 ,433.6,433.6,433.6
BEGIN DESCRIPTION:
Cross Section 10207.9 - Interpolated
END DESCRIPTION:
XS GIS Cut Line= 6
      3162681.49     13911711.42      3161445.59     13909972.27
      3160864.06     13909331.84      3160421.56     13909240.28
      3159612.84     13909286.06      3156866.26     13909331.84
#Sta/Elev= 30
  1538.8   59.45  1996.7   58.13  2418.8   58.98  2443.8   57.57  2753.8   56.71
  2808.8   51.05  2848.8   49.39  2883.8   55.59  2913.8   56.74    4898   52.66
    4920   52.56  4958.3   41.13  4983.5   41.28  4993.9   34.34  5000.9   33.88
  5006.6    34.3  5018.1   43.29  5029.1      43  5060.2   51.28  5114.3   51.47
  5174.3   56.67  5264.3   53.91  5399.3   53.67    5430    59.3    6100    58.1
    6300    60.5    6625    58.4    6775    59.9  6864.3   58.01  8546.2   61.43
#Mann= 5 ,-1 , 0
  1538.8      .2       0  1996.7      .1       0    4898      .1       0
    4920    .035       0  5060.2      .1       0
Bank Sta=4920,5060.2
XS Rating Curve= 0 ,0
Exp/Cntr=0.3,0.1

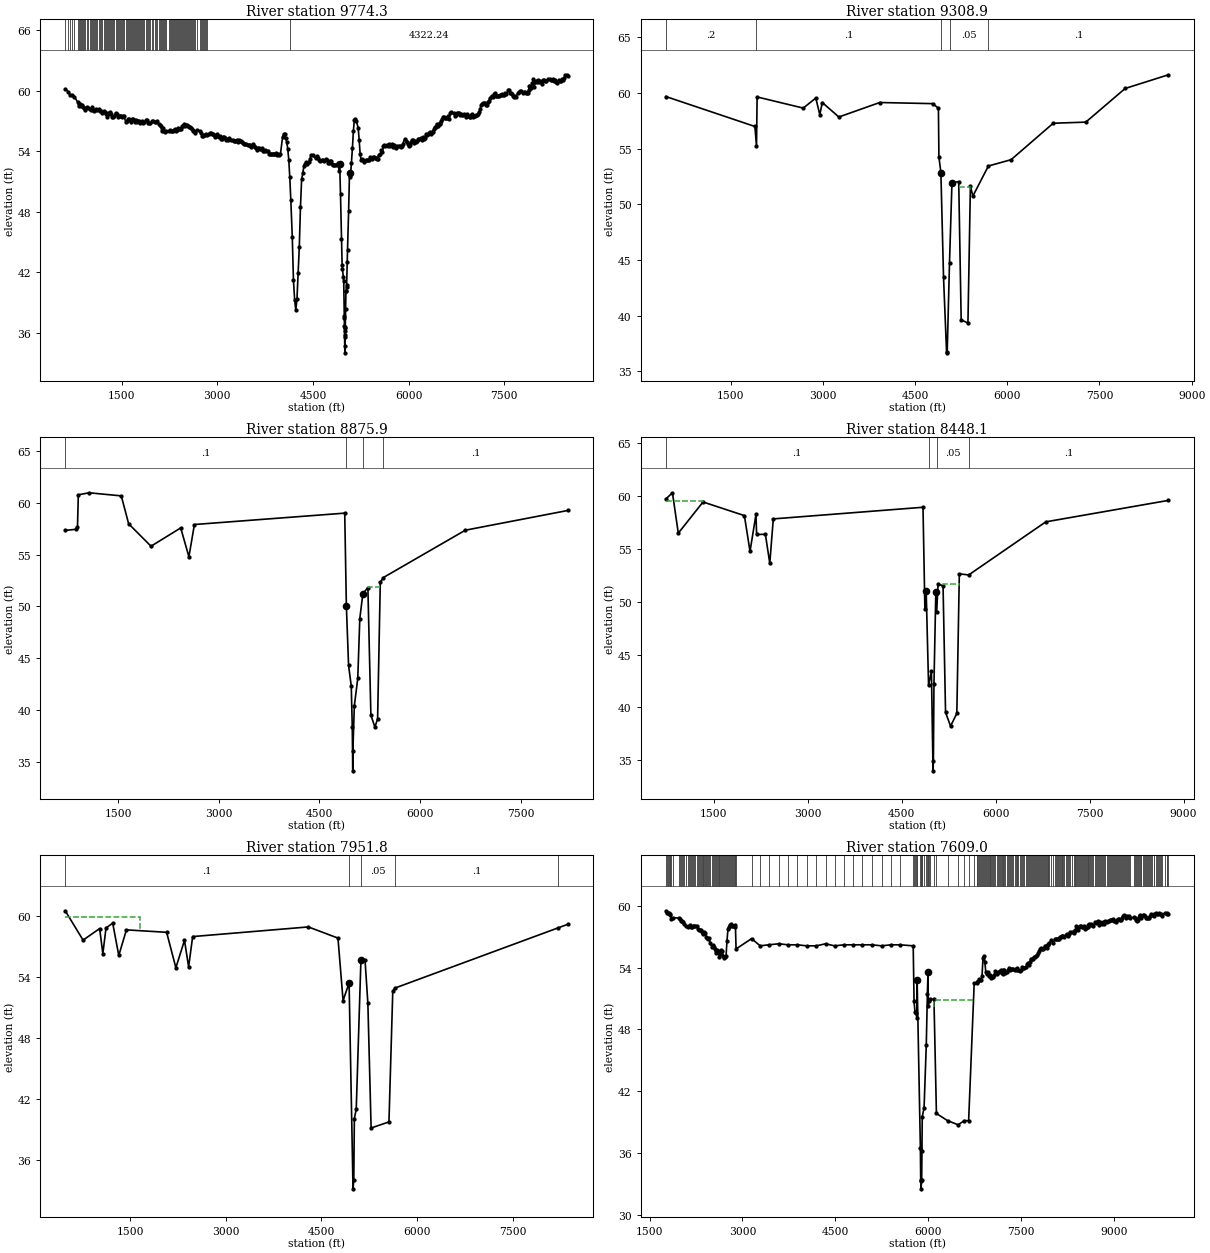
Type RM Length L Ch R = 1 ,9774.3  ,1020.4,465.4,367.9
BEGIN DESCRIPTION:
NEW XS BM LOMR
END DESCRIPTION:
XS GIS Cut Line= 6
 3164481.110831813909910.2784304 3163650.957890413909581.0875962
     3161272.212    13908637.814     3160985.756    13908852.178
     3160216.375    13908810.122 3156972.084733113909308.1613949
#Sta/Elev= 467
  615.76   60.16  664.04   59.89  696.22   59.55  728.41   59.57  760.59   59.38
  808.87   58.88  824.96    58.5  841.05   58.63  857.14   58.52  873.23   58.56
  889.33   58.42  905.42   58.32  921.51   58.07   953.7   58.39  969.79   58.24
 1001.97   58.18 1018.06   58.05 1034.16   58.33 1050.25    58.1 1066.34   57.94
 1082.43   58.09 1098.52   58.19 1114.62   58.07  1146.8    58.2 1162.89   58.02
 1178.99   57.96 1195.08   57.75 1227.26   57.94 1243.35   57.87 1259.45   57.72
 1275.54   57.38 1291.63   57.76 1307.72   57.72 1323.82   57.84 1339.91   57.67
    1356   57.41 1372.09   57.35 1388.18   57.53 1404.28   57.79 1420.37    57.7
 1436.46   57.43 1452.55    57.5 1468.64   57.47 1484.74   57.53 1500.83   57.43
 1516.92   57.45 1533.01   57.51  1565.2    56.9 1581.29      57 1597.38   57.14
 1613.47   57.16 1629.57   57.11 1645.66   56.84 1661.75   57.15 1677.84   57.21
 1693.93   57.13 1710.03   56.93 1726.12   57.05 1742.21   56.86  1758.3   56.98
  1774.4   56.97 1790.49   56.81 1806.58   56.93 1822.67   56.97 1838.76   56.82
 1854.86   56.93 1887.04   57.05 1903.13   57.05 1919.23    56.8 1935.32   56.76
 1951.41   56.78 1983.59   56.96 1999.69   56.99 2015.78   56.88 2031.87   56.84
 2047.96   57.02 2080.15   56.65 2096.24    56.6 2112.33   56.48 2128.42      56
 2144.52   56.25 2160.61   55.97  2176.7   55.94 2192.79   56.02 2241.07   55.96
 2257.16   56.09 2273.25   55.97 2283.14   55.98 2299.07   56.04    2315   56.05
 2330.93   56.18 2346.86   56.04 2362.79   56.12 2378.72    56.3 2394.65    56.2
 2410.58   56.18 2426.51   56.24 2442.44   56.45 2458.37   56.52  2474.3   56.67
 2490.24   56.54 2506.17   56.62  2522.1   56.61 2538.03   56.45 2553.96   56.39
 2569.89   56.38 2585.82   56.31 2601.75   56.17 2617.68   55.96 2633.61   55.97
 2649.54   55.79  2681.4   56.05 2729.19   55.96 2745.12    55.8 2761.06   55.53
 2776.99   55.48 2792.92    55.6 2808.85   55.59 2824.78   55.73 2840.71   55.62
 2872.57   55.72  2888.5    55.8 2904.43    55.8 2920.36   55.69 2936.29   55.74
 2952.22   55.63 2968.15   55.42 2984.08   55.49 3000.02   55.66 3015.95   55.47
 3031.88   55.37 3047.81   55.52 3063.74    55.2 3079.67   55.17  3095.6   55.44
 3111.53   55.38 3127.46   55.26 3143.39    55.1 3159.32   55.19 3175.25   55.13
 3191.18   55.27 3207.11   55.15 3238.98   55.06 3254.91   54.96 3270.84   55.04
 3286.77   54.98  3302.7   55.07 3318.63   54.93 3334.56   55.07 3350.49      55
 3366.42   55.03 3382.35   54.95 3398.28   54.79 3414.21   54.75 3430.14   54.75
 3446.07   54.74 3477.94   54.57 3493.87   54.64  3509.8   54.61 3525.73   54.42
 3557.59   54.67 3573.52   54.49 3589.45   54.36 3605.38   54.29 3621.31   54.14
 3637.24   54.33 3653.17   54.35  3669.1   54.23 3685.03   54.19 3700.96   54.29
  3716.9   54.04 3732.83   54.01 3748.76   54.09 3764.69   54.04 3796.55   54.03
 3812.48   53.71 3828.41   53.71 3844.34   53.75 3860.27   53.74  3876.2   53.67
 3892.13   53.73 3910.03   53.71 3926.24   53.81 3942.44   53.66 3958.65   53.69
 3974.86   53.64 3991.06   53.74 4023.48    55.4 4039.68   55.66 4055.89   55.66
 4072.09   55.27  4088.3   54.92 4104.51   54.24 4120.71   53.15 4136.92   51.39
 4153.13   49.11 4175.81   45.48 4194.13   41.23 4212.46   39.27 4230.79   38.24
 4249.12   39.31 4267.45   41.96 4285.78   44.48  4304.1   48.45 4322.43   51.22
 4340.76   51.82 4359.09   52.55 4377.42   52.68 4395.74   52.94 4414.07   52.77
  4432.4   52.92 4450.73   53.19 4469.06   53.61 4496.87   53.57 4542.11   53.27
 4557.19   53.52 4572.27   53.29 4602.43   53.16  4617.5   53.02 4647.66   53.12
 4662.74   53.11 4677.82   52.99 4707.98    53.2 4723.06   53.11 4738.14   52.78
 4753.22   52.83  4768.3   53.02 4783.38   52.98 4798.46   52.76 4813.53   52.61
 4828.61   52.59 4843.69   52.67 4879.05   52.63 4894.05   52.85 4909.06   52.05
  4919.1    52.7    4932    49.7    4947    45.3  4957.4    42.7    4962    42.3
    4977    41.5  4982.6    41.1  4991.7    37.7    4992    37.5    4993    36.7
    4997    36.2  4999.1    34.7    5000      34    5002    35.8  5005.7    35.6
  5006.4    36.5    5007    36.6    5012    38.3  5017.2    40.1    5022    40.1
    5027    40.5  5028.2    40.7    5037      43    5042    44.2  5059.3    48.1
 5073.21   51.85 5088.39   51.46 5103.57   52.86 5118.74    54.3 5133.92   55.97
  5149.1   57.13 5164.27   57.15 5179.45      57  5209.8   56.29 5224.98   55.07
 5240.16   53.68 5255.33   53.11 5270.51    53.2 5285.69    53.1 5300.86   52.95
 5331.22   53.13 5346.39    53.1 5361.57   53.12 5376.75    53.1 5391.92   53.38
  5407.1   53.33 5422.28   53.19 5437.45   53.39 5452.63   53.44 5467.81   53.27
 5482.99   53.32 5498.16   53.23 5513.34   53.25 5528.52   53.62 5558.87   53.67
 5574.05   54.12 5589.22   53.92  5604.4   54.46 5619.58   54.65 5634.75   54.52
 5665.11   54.59 5680.28   54.53 5695.46   54.67 5710.64    54.5 5725.81   54.62
 5740.99    54.7 5756.17   54.42 5771.34   54.65 5786.52   54.43  5801.7   54.28
 5816.87   54.54 5847.23    54.5  5862.4   54.51 5877.58   54.43 5892.76   54.55
 5907.93   54.73 5938.29   55.19 5953.46   55.05 5968.64   54.86 5983.82   54.74
 5998.99   54.49 6029.35   54.65 6044.53   54.91  6059.7   55.06 6074.88   55.07
 6090.06   54.76 6105.23   54.96 6120.41   54.92 6135.59   54.99 6150.76   55.24
 6165.94   55.21 6196.29   55.26 6211.47   55.12 6226.65   55.38 6241.82   55.16
    6257   55.33 6272.18   55.73 6287.35   55.59 6302.53   55.68 6317.71   55.82
 6332.88   55.86 6348.06   55.71 6363.24   55.86 6378.41   55.92 6393.59    56.2
 6408.77   56.37 6423.94   56.35 6439.12   56.71  6454.3   56.45 6469.47    56.7
 6484.65   56.69 6499.83   56.78    6515   57.02 6530.18   57.14 6545.36   57.43
 6560.53   57.38 6575.71   57.25 6590.89   57.33 6606.07   57.28 6621.24   57.48
 6636.42    57.2  6651.6   57.74 6666.77   57.86  6712.3   57.75 6727.48   57.52
 6742.66   57.56 6757.83   57.74 6773.01   57.77 6788.19   57.74 6803.36   57.61
 6818.54   57.65 6833.72   57.61 6848.89   57.62 6864.07   57.67 6894.42   57.36
  6909.6   57.65 6924.78   57.51 6939.95   57.53 6955.13   57.35 6970.31   57.39
 6985.48   57.57 7000.66   57.68 7015.84   57.43 7031.01   57.48 7046.19   57.48
 7061.37   57.55 7076.54   57.56 7091.72   57.67  7106.9   57.88 7122.07    58.2
 7137.25   58.58 7152.43   58.71 7167.61   58.77 7182.78   58.77 7197.96   58.73
 7213.14   58.53 7228.31   58.57 7243.49   58.86 7258.67   59.01 7273.84   59.27
  7304.2   59.51 7319.37   59.34 7334.55   59.62 7349.73   59.74  7364.9   59.43
 7380.08   59.42 7395.26   59.47 7410.43   59.44 7425.61   59.55 7455.96   59.59
 7471.14   59.65 7486.32   59.54 7501.49   59.59 7516.67   59.78 7531.85   59.62
  7562.2   60.05 7577.38   60.02 7592.18   59.73 7607.32   59.78 7622.46   59.67
 7637.61   59.48 7652.75   59.38 7667.89   59.42 7683.03   59.36 7713.31   59.77
 7728.45   59.82 7743.59   59.97 7758.73   59.99 7789.01   59.79 7804.15   59.87
 7819.29   59.89 7834.43   59.72 7849.57   59.77 7864.71   59.77 7879.86   60.06
    7895   60.42 7910.14   60.42 7925.28   60.27 7940.42   60.78 7955.56   61.11
  7970.7    60.4 7985.84    60.9 8000.98      61 8016.12   60.86 8031.26   61.02
  8046.4   60.84 8061.54   60.92 8076.68   60.85 8091.82   60.61 8106.96   61.05
 8122.11   61.07 8137.25   60.98 8152.39   60.95 8182.67   61.12 8212.95   61.15
 8228.09   61.05 8243.23   61.01 8258.37   61.14 8273.51   60.96 8288.65    61.1
 8303.79   60.88 8318.93   60.82 8334.07    60.8 8364.36   61.09  8379.5   60.99
 8394.64   60.98 8409.78   61.17 8424.92   61.05 8440.06   61.22  8455.2   61.54
 8485.48   61.57 8497.34   61.47
#Mann= 467 ,-1 , 0
  615.76      .2       0  664.04       0       0  696.22       0       0
  728.41       0       0  760.59       0       0  808.87       0       0
  824.96       0       0  841.05       0       0  857.14       0       0
  873.23       0       0  889.33       0       0  905.42       0       0
  921.51       0       0   953.7       0       0  969.79       0       0
 1001.97       0       0 1018.06       0       0 1034.16       0       0
 1050.25       0       0 1066.34       0       0 1082.43       0       0
 1098.52       0       0 1114.62       0       0  1146.8       0       0
 1162.89       0       0 1178.99       0       0 1195.08       0       0
 1227.26       0       0 1243.35       0       0 1259.45       0       0
 1275.54       0       0 1291.63       0       0 1307.72       0       0
 1323.82       0       0 1339.91       0       0    1356       0       0
 1372.09       0       0 1388.18       0       0 1404.28       0       0
 1420.37       0       0 1436.46       0       0 1452.55       0       0
 1468.64       0       0 1484.74       0       0 1500.83       0       0
 1516.92       0       0 1533.01       0       0  1565.2       0       0
 1581.29       0       0 1597.38       0       0 1613.47       0       0
 1629.57       0       0 1645.66       0       0 1661.75       0       0
 1677.84       0       0 1693.93       0       0 1710.03       0       0
 1726.12       0       0 1742.21       0       0  1758.3       0       0
  1774.4       0       0 1790.49       0       0 1806.58       0       0
 1822.67       0       0 1838.76       0       0 1854.86       0       0
 1887.04       0       0 1903.13       0       0 1919.23       0       0
 1935.32       0       0 1951.41       0       0 1983.59       0       0
 1999.69       0       0 2015.78       0       0 2031.87       0       0
 2047.96       0       0 2080.15       0       0 2096.24       0       0
 2112.33       0       0 2128.42       0       0 2144.52       0       0
 2160.61       0       0  2176.7       0       0 2192.79       0       0
 2241.07       0       0 2257.16       0       0 2273.25       0       0
 2283.14       0       0 2299.07       0       0    2315       0       0
 2330.93       0       0 2346.86       0       0 2362.79       0       0
 2378.72       0       0 2394.65       0       0 2410.58       0       0
 2426.51       0       0 2442.44       0       0 2458.37       0       0
  2474.3       0       0 2490.24       0       0 2506.17       0       0
  2522.1       0       0 2538.03       0       0 2553.96       0       0
 2569.89       0       0 2585.82       0       0 2601.75       0       0
 2617.68       0       0 2633.61       0       0 2649.54       0       0
  2681.4       0       0 2729.19       0       0 2745.12       0       0
 2761.06       0       0 2776.99       0       0 2792.92       0       0
 2808.85       0       0 2824.78       0       0 2840.71       0       0
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#XS Ineff= 1 ,-1
 4140.54 4322.24   51.14
Permanent Ineff=
       T
Bank Sta=4919.1,5073.21
XS Rating Curve= 0 ,0
Exp/Cntr=0.3,0.1

Type RM Length L Ch R = 1 ,9308.9  ,121.7,433,734
BEGIN DESCRIPTION:
Cross Section  9308.9
END DESCRIPTION:
XS GIS Cut Line= 6
      3164725.12     13909445.74      3161746.47     13908377.63
      3160816.55     13908147.35      3160566.95     13908323.35
      3160260.68     13908370.47      3156946.65     13909289.29
#Sta/Elev= 30
   443.9   59.67  1893.9   56.98    1920   55.23    1930   59.63    2680   58.63
    2885   59.53    2950   58.03    2990   59.13    3260   57.83    3925   59.13
    4785   59.03 4879.63   58.63  4887.9   54.25    4920   52.84  4962.9   43.44
  5012.9   36.66  5022.9   36.76  5060.2   44.76    5100   51.93    5210   52.03
    5250   39.63    5360   39.33    5400   51.63    5440   50.73  5692.7   53.43
  6062.7      54  6747.7   57.27  7277.7   57.37  7917.7   60.39  8621.8   61.62
#Mann= 5 ,-1 , 0
   443.9      .2       0    1920      .1       0    4920    .035       0
  5060.2     .05       0  5692.7      .1       0
#XS Ineff= 1 ,-1
 5211.48 5398.53   51.59
Permanent Ineff=
       T
Bank Sta=4920,5100
XS Rating Curve= 0 ,0
Exp/Cntr=0.3,0.1

Type RM Length L Ch R = 1 ,8875.9  ,143,427.8,477.7
BEGIN DESCRIPTION:
NEW XS BM LOMR
END DESCRIPTION:
XS GIS Cut Line= 6
     3164436.859    13909101.173     3163791.826    13908523.701
     3163199.163    13908326.147      3161257.71    13907938.462
     3159196.772    13907887.191     3157260.295    13907842.936
#Sta/Elev= 30
  714.15   57.36  880.15   57.47  896.75   57.68  909.15    60.8 1069.15      61
 1549.15    60.7 1659.15      58 1992.38   55.83 2435.02    57.6 2557.12   54.81
 2639.15   57.93 4879.15   59.03 4903.73   50.03 4936.53    44.3 4976.63    42.3
 4991.53    38.3 4998.93    34.1 5000.63      36 5022.53    40.4 5073.66   43.05
 5103.76   48.82 5149.15   51.23 5224.15   51.83 5269.15   39.48 5329.15   38.33
 5369.15   39.13 5409.15   52.33 5455.03    52.8 6676.82   57.38 8204.74   59.29
#Mann= 4 ,-1 , 0
  714.15      .1       0 4903.73    .035       0 5149.15     .05       0
 5455.03      .1       0
#XS Ineff= 1 ,-1
 5223.73  5407.8   51.84
Permanent Ineff=
       T
Bank Sta=4903.73,5149.15
XS Rating Curve= 0 ,0
Exp/Cntr=0.3,0.1

Type RM Length L Ch R = 1 ,8448.1  ,433.5,496.3,511.1
BEGIN DESCRIPTION:
Cross Section  8448.1
END DESCRIPTION:
XS GIS Cut Line= 6
      3164575.66     13908676.94       3163271.4     13908042.43
      3161409.08     13907800.89      3160874.95     13907657.53
      3160314.55     13907404.06      3156804.37     13907050.68
#Sta/Elev= 30
   733.6   59.71     840    60.3   933.6   56.48  1328.6   59.43  1988.6   58.14
  2078.6   54.76  2173.6   58.25    2184   56.36    2324   56.37    2394   53.63
    2450   57.83    4840   58.93    4870   49.33  4890.7   51.05  4928.9   42.11
  4974.5   43.41  5000.1      34  5005.8   34.91    5015   42.23  5044.7   50.93
  5058.4   49.03    5080   51.63    5160   51.53    5200   39.53    5280   38.23
    5380   39.43    5420   52.63    5570   52.53    6800   57.55  8757.9   59.58
#Mann= 4 ,-1 , 0
   733.6      .1       0  4928.9    .035       0  5058.4     .05       0
    5570      .1       0
#XS Ineff= 2 ,-1
   733.6    1327    59.5 5158.76 5416.66    51.7
Permanent Ineff=
       F       T
Bank Sta=4890.7,5044.7
XS Rating Curve= 0 ,0
Exp/Cntr=0.3,0.1

Type RM Length L Ch R = 1 ,7951.8  ,455.8,342.8,122.9
BEGIN DESCRIPTION:
Cross Section 7951.8 - Interpolated
END DESCRIPTION:
XS GIS Cut Line= 6
      3164916.41     13908688.69       3163882.4     13908077.68
      3161794.85     13907332.94      3160101.12     13906875.17
      3159399.22     13906783.62      3157400.44     13906851.03
#Sta/Elev= 30
   480.5   60.52   760.5   57.63  1020.5   58.77  1070.5   56.29  1120.5   58.83
  1225.5    59.3  1320.5   56.12  1440.5   58.64  2071.5    58.4  2216.5   54.91
  2351.5   57.61  2416.5      55    2480   57.98    4295   58.93    4760   57.83
    4840   51.68  4934.3   53.41  4996.3   33.14  5008.1   34.01  5017.2   40.05
  5046.7      41    5120   55.63    5185   55.63 5229.12   51.41    5280   39.13
    5560   39.73    5620   52.63  5658.6   52.92    8215   58.84  8367.6   59.19
#Mann= 5 ,-1 , 0
   480.5      .1       0  4934.3    .035       0    5120     .05       0
  5658.6      .1       0    8215      .2       0
#XS Ineff= 2 ,-1
   480.5    1650    59.9 5216.39 5621.26   52.59
Permanent Ineff=
       F       T
Bank Sta=4934.3,5120
XS Rating Curve= 0 ,0
Exp/Cntr=0.3,0.1

Type RM Length L Ch R = 1 ,7609.0  ,313,170.1,50.4
BEGIN DESCRIPTION:
NEW XS BM LOMR
END DESCRIPTION:
XS GIS Cut Line= 6
     3165078.693    13907129.434     3162668.622    13906925.824
     3161019.639    13906838.203     3160960.751    13906767.455
     3160252.771    13906738.216     3157036.723    13906850.829
#Sta/Elev= 290
 1762.38   59.54 1777.59   59.33 1792.79   59.28    1808   59.31  1823.2   59.25
 1838.41   59.11 1853.62    58.7 1884.03   58.87 1975.27   58.83 1990.47   58.74
 2005.68   58.55 2020.88   58.54 2036.09   58.48  2051.3   58.27 2081.71   58.08
 2127.33   57.99 2142.53   58.09 2157.74   58.14 2172.94   58.01 2188.15   57.98
 2203.36   58.05 2218.56   58.04 2233.77   58.07 2264.18   58.04 2279.39   57.78
 2294.59   57.63  2309.8   57.67    2325   57.66 2340.21   57.46 2355.42   57.35
 2370.62   57.29 2385.83   57.44 2401.03   57.37 2416.24   57.03 2431.45   56.86
 2446.65   56.84 2461.86   56.88 2477.07   56.44 2507.48   56.05 2522.68   56.17
 2537.89   56.04  2553.1   55.82  2568.3   55.41 2583.51   55.74 2598.71   55.64
 2613.92   55.46 2629.13   55.09 2644.33   55.31 2659.54   55.68 2674.74   55.62
 2689.95   55.17 2705.16   54.94 2720.36   55.06 2735.57   55.12 2750.77   56.63
 2765.98   57.73 2781.19      58 2796.39   58.19  2811.6   58.25  2826.8   58.06
 2842.01   58.02 2857.22   58.06 2872.42   58.18 2887.63   57.97 2897.38   55.83
 3147.38   56.83 3287.38   56.13 3422.38   56.23 3587.38   56.33 3737.38   56.23
 3888.38   56.23 4037.38   56.13 4192.38   56.13 4342.38   56.33 4487.38   56.13
 4642.38   56.23 4792.38   56.23 4937.38   56.23 5092.38   56.23 5247.38   56.13
 5397.38   56.23 5547.38   56.23 5757.38   56.13 5771.17   50.72 5786.58   49.69
 5801.99   49.59  5817.4   49.12  5820.6    52.8  5873.3    36.5  5878.3    33.3
  5878.6    33.4  5882.6    32.5  5894.4    33.4  5899.4    36.2  5903.5    39.5
    5933    40.4  5968.6    46.5    5986    51.4  5996.4    53.6 5999.99   50.27
 6015.04   50.78 6022.38   50.93 6092.38   50.93 6132.38   39.83 6312.38   39.13
 6482.38   38.73 6582.38   39.13 6652.38   39.13 6742.38   52.53 6782.38   52.53
 6794.15   52.62 6809.18   52.67 6824.21   52.92 6839.23   52.82 6854.26   52.76
 6869.29   53.23 6884.32   54.99 6899.35   55.18 6914.38   54.52 6929.41   53.59
 6944.44   53.37 6959.47   53.55 6974.49   53.19 6989.52   53.21 7004.55   53.34
 7019.58   52.99 7034.61   53.09 7049.64   53.06 7064.67   53.28  7079.7   53.67
 7109.75   53.41 7124.78   53.58 7139.81   53.55 7154.84   53.69 7169.87   53.74
  7184.9   53.51 7199.93    53.4 7214.96   53.75 7229.98   53.82 7245.01   53.49
 7275.07    53.6  7290.1   53.74 7305.13   53.96 7320.16   53.75 7335.19   53.92
 7350.21   53.92 7365.24   53.83  7395.3   53.78 7410.33   53.91 7425.36   53.93
 7440.39   53.82 7455.42   53.81  7476.4   53.68 7491.41   53.75 7521.43   54.04
 7536.44      54 7551.45   54.02 7581.48   54.12 7596.49   54.32  7611.5   54.46
 7626.51   54.28 7641.52   54.56 7656.53   54.89 7671.54   54.82 7686.55   54.81
 7701.56   55.02 7731.58   55.08 7746.59   55.19 7761.61   55.23 7776.62    55.4
 7791.63   55.67 7806.64   55.82 7821.65   55.89 7836.66    55.8 7851.67    55.8
 7866.68    55.9 7881.69   56.16  7896.7   56.11 7911.71   55.88 7926.72    56.2
 7941.73   56.32 7956.74    56.4 7986.77   56.72 8016.79   56.41 8046.81   56.79
 8061.82   56.76 8076.83    56.8 8091.84   56.79 8106.85   56.83 8121.86   57.03
 8136.87   57.03 8151.88   57.07  8166.9   57.04 8181.91   57.06 8196.92   56.95
 8226.94   57.21 8241.95    57.3 8256.96    57.1 8271.97   57.26 8286.98   57.48
    8317   57.48 8347.02   57.34 8362.03   57.65 8377.05   57.58 8392.06   58.06
 8407.07   58.01 8422.08   57.67 8437.09   57.97  8452.1   58.05 8467.11   58.03
 8482.12   57.95 8497.13   57.97 8512.14    58.1 8527.15   57.79 8542.16   57.82
 8557.17   57.99 8572.19   57.97  8587.2   58.14 8602.21   58.24 8617.22   58.19
 8632.23   58.27 8647.24   58.12 8662.25   58.03 8692.27   58.44 8707.28   58.33
 8722.29   58.49  8737.3   58.52 8752.31    58.2 8767.32   58.42 8782.34    58.4
 8812.36   58.25 8827.37   58.43 8842.38   58.29 8857.39   58.53 8887.41   58.49
 8902.42   58.51 8917.43   58.58 8932.44   58.69 8947.45    58.6 8962.46   58.62
 8977.48   58.72  9007.5   58.59 9022.51   58.56 9037.52   58.48 9052.53    58.6
 9067.54   58.76 9082.55    58.7 9097.56    58.6 9112.57   58.64 9127.58   58.87
 9142.59   59.03  9157.6    59.1 9172.61   59.03 9187.63   58.88 9202.64   58.99
 9232.66   58.95 9247.67   58.99 9262.68   58.88 9322.72   58.89 9337.73   58.81
 9352.74   58.66 9367.75   58.57 9382.77   58.61 9397.78   58.93 9412.79   59.16
  9427.8   59.04 9442.81   58.85 9472.83    59.1 9487.84   59.15 9502.85   59.06
 9517.86   58.79 9532.87   58.87 9547.88   58.81 9562.89   58.82  9577.9   59.02
 9592.92   59.18 9607.93    59.1 9637.95   59.08 9652.96   59.25 9682.98   59.36
 9697.99   59.27    9713   59.24 9728.01    59.3 9743.02   59.21 9758.03   59.22
 9773.04   59.08 9818.08   59.29  9848.1   59.24 9863.11   59.29 9878.12   59.19
#Mann= 290 ,-1 , 0
 1762.38      .1       0 1777.59       0       0 1792.79       0       0
    1808       0       0  1823.2       0       0 1838.41       0       0
 1853.62       0       0 1884.03       0       0 1975.27       0       0
 1990.47       0       0 2005.68       0       0 2020.88       0       0
 2036.09       0       0  2051.3       0       0 2081.71       0       0
 2127.33       0       0 2142.53       0       0 2157.74       0       0
 2172.94       0       0 2188.15       0       0 2203.36       0       0
 2218.56       0       0 2233.77       0       0 2264.18       0       0
 2279.39       0       0 2294.59       0       0  2309.8       0       0
    2325       0       0 2340.21       0       0 2355.42       0       0
 2370.62       0       0 2385.83       0       0 2401.03       0       0
 2416.24       0       0 2431.45       0       0 2446.65       0       0
 2461.86       0       0 2477.07       0       0 2507.48       0       0
 2522.68       0       0 2537.89       0       0  2553.1       0       0
  2568.3       0       0 2583.51       0       0 2598.71       0       0
 2613.92       0       0 2629.13       0       0 2644.33       0       0
 2659.54       0       0 2674.74       0       0 2689.95       0       0
 2705.16       0       0 2720.36       0       0 2735.57       0       0
 2750.77       0       0 2765.98       0       0 2781.19       0       0
 2796.39       0       0  2811.6       0       0  2826.8       0       0
 2842.01       0       0 2857.22       0       0 2872.42       0       0
 2887.63       0       0 2897.38       0       0 3147.38       0       0
 3287.38       0       0 3422.38       0       0 3587.38       0       0
 3737.38       0       0 3888.38       0       0 4037.38       0       0
 4192.38       0       0 4342.38       0       0 4487.38       0       0
 4642.38       0       0 4792.38       0       0 4937.38       0       0
 5092.38       0       0 5247.38       0       0 5397.38       0       0
 5547.38       0       0 5757.38       0       0 5771.17       0       0
 5786.58       0       0 5801.99       0       0  5817.4       0       0
  5820.6    .035       0  5873.3       0       0  5878.3       0       0
  5878.6       0       0  5882.6       0       0  5894.4       0       0
  5899.4       0       0  5903.5       0       0    5933       0       0
  5968.6       0       0    5986       0       0  5996.4     .05       0
 5999.99       0       0 6015.04       0       0 6022.38       0       0
 6092.38       0       0 6132.38       0       0 6312.38       0       0
 6482.38       0       0 6582.38       0       0 6652.38       0       0
 6742.38       0       0 6782.38      .1       0 6794.15       0       0
 6809.18       0       0 6824.21       0       0 6839.23       0       0
 6854.26       0       0 6869.29       0       0 6884.32       0       0
 6899.35       0       0 6914.38       0       0 6929.41       0       0
 6944.44       0       0 6959.47       0       0 6974.49       0       0
 6989.52       0       0 7004.55       0       0 7019.58       0       0
 7034.61       0       0 7049.64       0       0 7064.67       0       0
  7079.7       0       0 7109.75       0       0 7124.78       0       0
 7139.81       0       0 7154.84       0       0 7169.87       0       0
  7184.9       0       0 7199.93       0       0 7214.96       0       0
 7229.98       0       0 7245.01       0       0 7275.07       0       0
  7290.1       0       0 7305.13       0       0 7320.16       0       0
 7335.19       0       0 7350.21       0       0 7365.24       0       0
  7395.3       0       0 7410.33       0       0 7425.36       0       0
 7440.39       0       0 7455.42       0       0  7476.4       0       0
 7491.41       0       0 7521.43       0       0 7536.44       0       0
 7551.45       0       0 7581.48       0       0 7596.49       0       0
  7611.5       0       0 7626.51       0       0 7641.52       0       0
 7656.53       0       0 7671.54       0       0 7686.55       0       0
 7701.56       0       0 7731.58       0       0 7746.59       0       0
 7761.61       0       0 7776.62       0       0 7791.63       0       0
 7806.64       0       0 7821.65       0       0 7836.66       0       0
 7851.67       0       0 7866.68       0       0 7881.69       0       0
  7896.7       0       0 7911.71       0       0 7926.72       0       0
 7941.73       0       0 7956.74       0       0 7986.77       0       0
 8016.79       0       0 8046.81       0       0 8061.82       0       0
 8076.83       0       0 8091.84       0       0 8106.85       0       0
 8121.86       0       0 8136.87       0       0 8151.88       0       0
  8166.9       0       0 8181.91       0       0 8196.92       0       0
 8226.94       0       0 8241.95       0       0 8256.96       0       0
 8271.97       0       0 8286.98       0       0    8317       0       0
 8347.02       0       0 8362.03       0       0 8377.05       0       0
 8392.06       0       0 8407.07       0       0 8422.08       0       0
 8437.09       0       0  8452.1       0       0 8467.11       0       0
 8482.12       0       0 8497.13       0       0 8512.14       0       0
 8527.15       0       0 8542.16       0       0 8557.17       0       0
 8572.19       0       0  8587.2       0       0 8602.21       0       0
 8617.22       0       0 8632.23       0       0 8647.24       0       0
 8662.25       0       0 8692.27       0       0 8707.28       0       0
 8722.29       0       0  8737.3       0       0 8752.31       0       0
 8767.32       0       0 8782.34       0       0 8812.36       0       0
 8827.37       0       0 8842.38       0       0 8857.39       0       0
 8887.41       0       0 8902.42       0       0 8917.43       0       0
 8932.44       0       0 8947.45       0       0 8962.46       0       0
 8977.48       0       0  9007.5       0       0 9022.51       0       0
 9037.52       0       0 9052.53       0       0 9067.54       0       0
 9082.55       0       0 9097.56       0       0 9112.57       0       0
 9127.58       0       0 9142.59       0       0  9157.6       0       0
 9172.61       0       0 9187.63       0       0 9202.64       0       0
 9232.66       0       0 9247.67       0       0 9262.68       0       0
 9322.72       0       0 9337.73       0       0 9352.74       0       0
 9367.75       0       0 9382.77       0       0 9397.78       0       0
 9412.79       0       0  9427.8       0       0 9442.81       0       0
 9472.83       0       0 9487.84       0       0 9502.85       0       0
 9517.86       0       0 9532.87       0       0 9547.88       0       0
 9562.89       0       0  9577.9       0       0 9592.92       0       0
 9607.93       0       0 9637.95       0       0 9652.96       0       0
 9682.98       0       0 9697.99       0       0    9713       0       0
 9728.01       0       0 9743.02       0       0 9758.03       0       0
 9773.04       0       0 9818.08       0       0  9848.1       0       0
 9863.11       0       0 9878.12       0       0
#XS Ineff= 1 ,-1
  6095.1 6733.81   50.89
Permanent Ineff=
       T
Bank Sta=5820.6,5996.4
XS Rating Curve= 0 ,0
Exp/Cntr=0.3,0.1