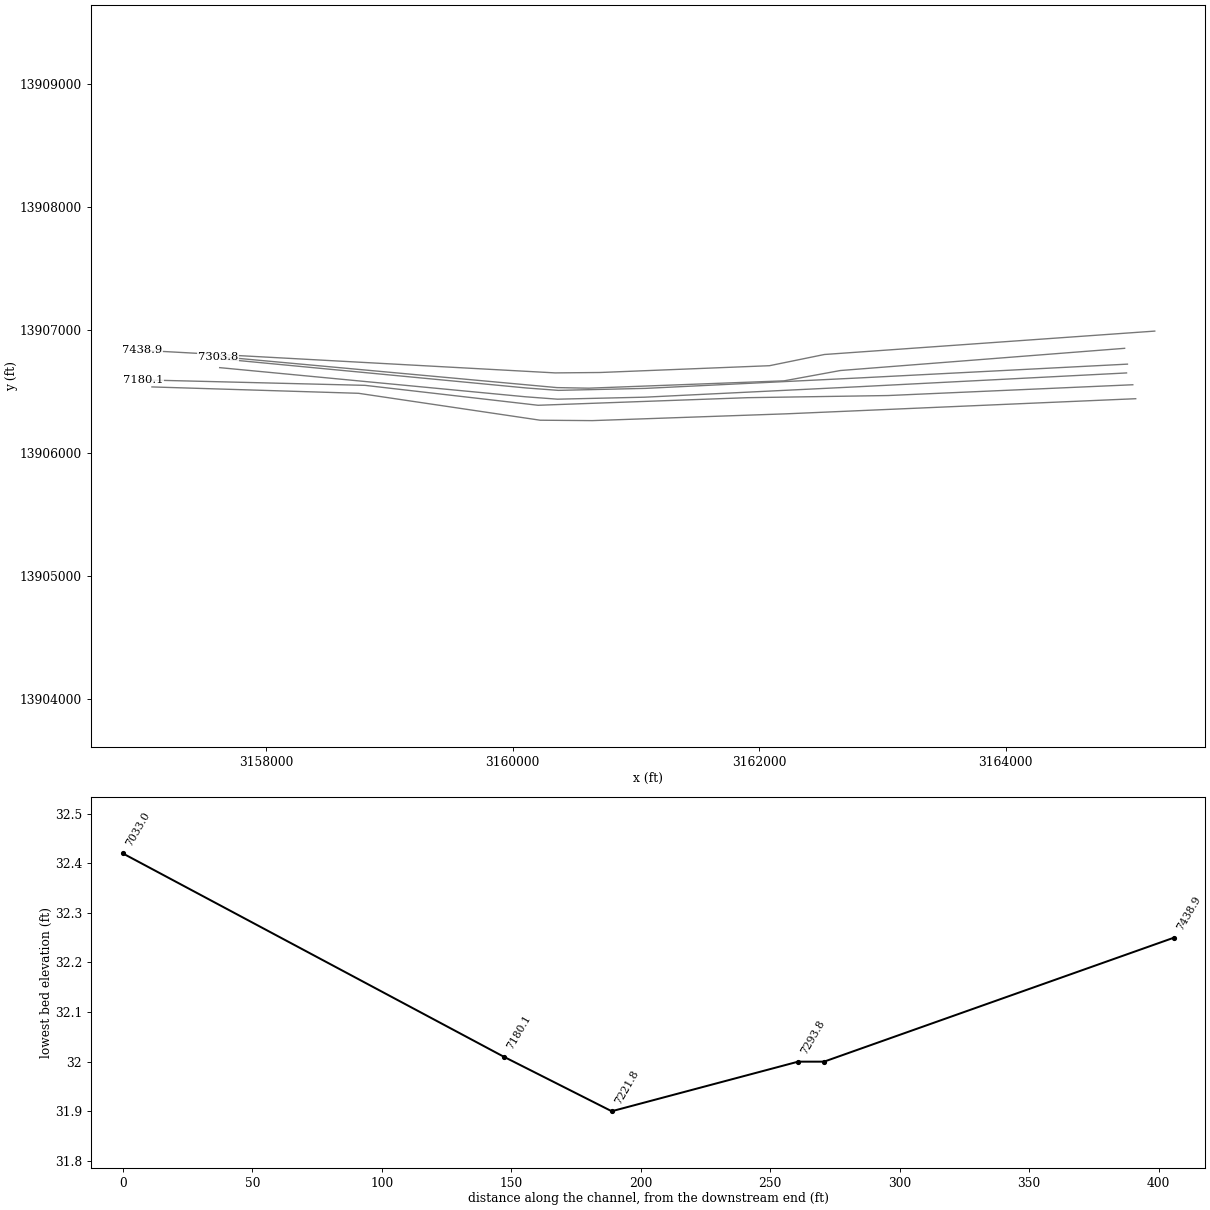
HEC-RAS study P130-00-00.prj: P130-00-00

--- P130-00-00.g01 (geometry) --- (continued)

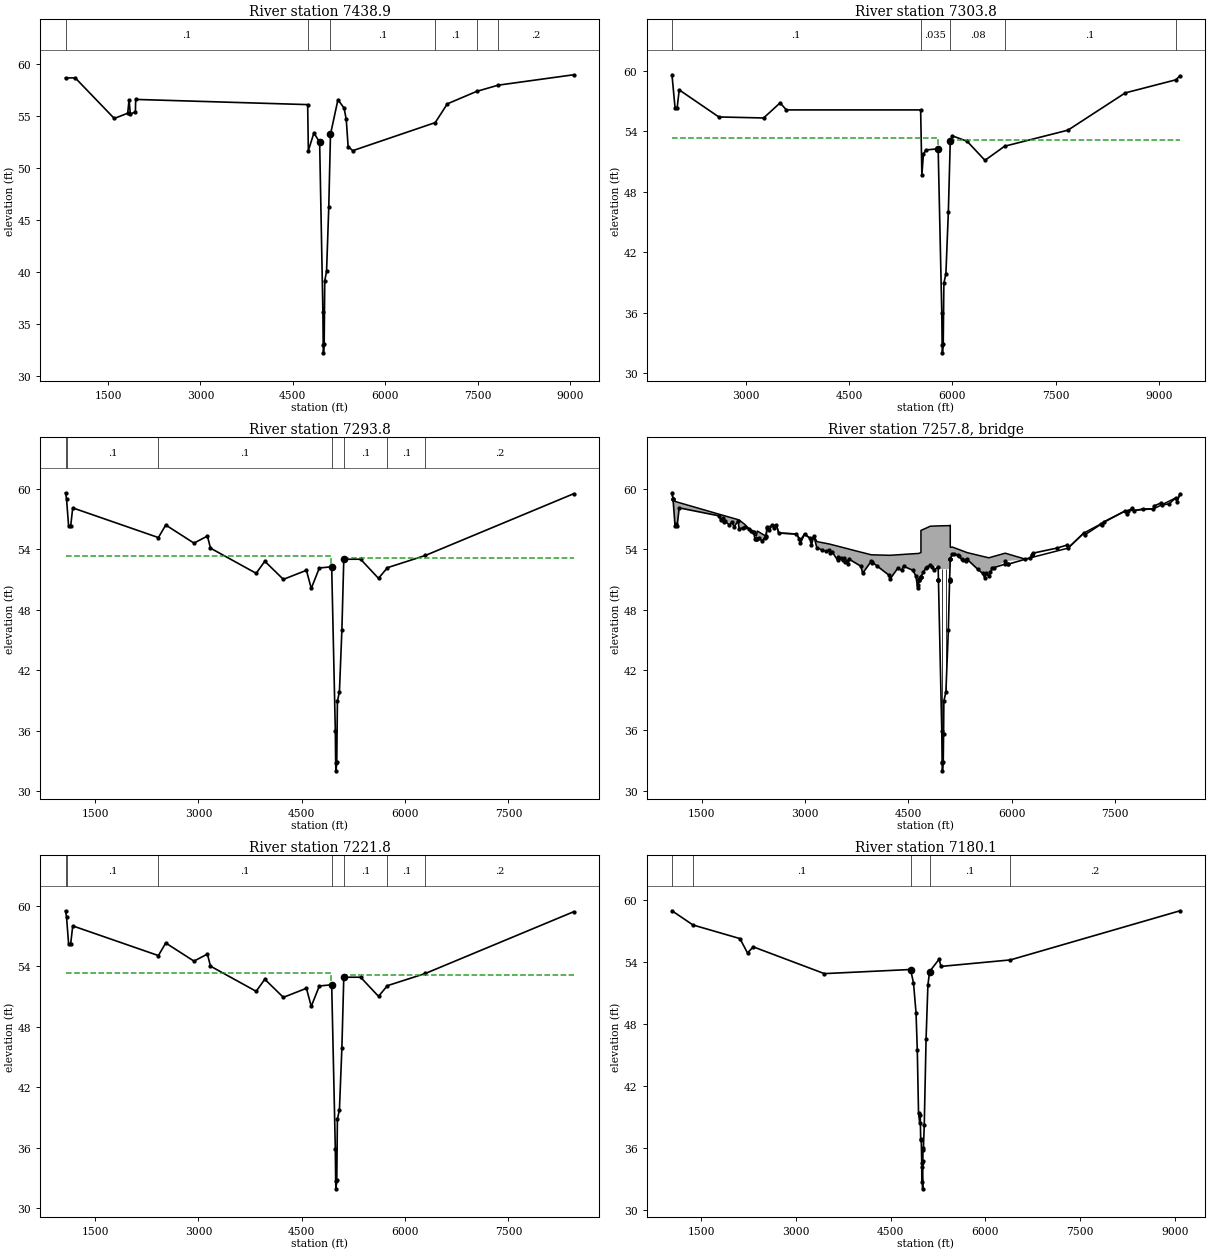
Type RM Length L Ch R = 1 ,7438.9  ,121.1,135.1,123.8
BEGIN DESCRIPTION:
Cross Section 7438.9 - Interpolated
END DESCRIPTION:
XS GIS Cut Line= 6
      3165210.16     13906988.05      3162528.83     13906797.72
      3162083.53      13906706.6      3160708.14     13906651.33
      3160343.97     13906648.08      3156990.99     13906831.81
#Sta/Elev= 30
   811.2    58.7     969    58.7    1602    54.8  1820.6    55.3  1842.5    56.6
    1863   55.23    1945   55.43    1950   56.63    4740   56.13  4751.2    51.7
  4840.9    53.4  4934.3   52.52    4987   36.21    4992   33.05  4996.3   32.25
  5008.1   33.12  5017.2   39.16  5046.7   40.11  5082.3   46.25  5110.1   53.27
  5231.2    56.6  5330.6    55.8  5366.2    54.7  5396.2    52.1  5471.2    51.7
  6810.1    54.4  7005.2    56.2  7480.7    57.4  7830.9      58  9053.7      59
#Mann= 6 ,-1 , 0
   811.2      .1       0    4740    .035       0  5110.1      .1       0
  6810.1      .1       0  7480.7      .1       0  7830.9      .2       0
Bank Sta=4934.3,5110.1
XS Rating Curve= 0 ,0
Exp/Cntr=0.5,0.3

Type RM Length L Ch R = 1 ,7303.8  ,10,10,10
BEGIN DESCRIPTION:
Cross Section 7438.9 - Interpolated
END DESCRIPTION:
XS GIS Cut Line= 6
     3164965.576    13906848.028     3162658.404    13906667.434
     3162201.976    13906583.472     3160616.101    13906523.828
     3160359.162    13906528.499     3157607.772    13906781.347
#Sta/Elev= 30
  1927.8   59.62  1972.8   56.32  2002.8   56.32  2032.8   58.12  2608.2   55.43
  3258.2   55.33  3498.2   56.83  3588.2   56.13  5538.2   56.13  5556.2   49.63
  5578.1   51.72  5613.2   52.15  5792.5   52.27  5845.2   35.96  5850.2    32.8
  5854.5      32  5866.3   32.87  5875.4   38.91  5904.9   39.86  5940.5      46
  5968.2   53.02 5968.29   53.02  5998.8   53.55  6212.2   53.02  6472.2   51.12
  6756.4   52.52  7677.3   54.12    8509   57.82    9244   59.12    9304   59.52
#Mann= 5 ,-1 , 0
  1927.8      .1       0  5538.2    .035       0 5968.29     .08       0
  6756.4      .1       0    9244      .2       0
#XS Ineff= 2 , 0
       0  5786.7    53.3  5968.5       0    53.1
Permanent Ineff=
       F       F
Bank Sta=5792.5,5968.2
XS Rating Curve= 0 ,0
Exp/Cntr=0.5,0.3

Type RM Length L Ch R = 1 ,7293.8  ,72,72,72
BEGIN DESCRIPTION:
Upstream Section of Bridge/Culvert/Weir
END DESCRIPTION:
XS GIS Cut Line= 6
      3164988.41     13906719.38      3162817.92     13906607.44
      3161079.26     13906522.25      3160370.43     13906505.99
      3160110.31      13906525.5      3157629.39     13906762.45
#Sta/Elev= 30
  1069.6   59.62  1084.1   59.04  1114.6   56.32  1144.6   56.32  1174.6   58.12
  2418.3   55.17  2524.6   56.42  2934.6   54.62  3129.6   55.32  3174.6   54.12
    3838   51.62    3963   52.82  4232.5   51.02  4567.5   51.92  4637.5   50.12
    4755   52.15  4934.3   52.27    4987   35.96    4992    32.8  4996.3      32
  5008.1   32.87  5017.2   38.91  5046.7   39.86  5082.3      46    5110   53.02
    5354   53.02    5614   51.12  5743.3   52.18  6293.2   53.39  8445.8   59.52
#Mann= 7 ,-1 , 0
  1069.6      .2       0  1084.1      .1       0  2418.3      .1       0
  4934.3    .035       0    5110      .1       0  5743.3      .1       0
  6293.2      .2       0
#XS Ineff= 2 , 0
       0  4928.5    53.3  5110.3       0    53.1
Permanent Ineff=
       F       F
Bank Sta=4934.3,5110
XS Rating Curve= 0 ,0
Exp/Cntr=0.5,0.3

Type RM Length L Ch R = 3 ,7257.8  ,,,
BEGIN DESCRIPTION:
WEST BELTWAY 8
Structure ID: P30-5
END DESCRIPTION:
Bridge Culvert--1,0,-1,-1, 0
Deck Dist Width WeirC Skew NumUp NumDn MinLoCord MaxHiCord MaxSubmerge Is_Ogee
10,52,2.6,0, 60, 60, , , 0.95, 0, 1,1,,
  1069.6  1084.6  1114.6  1144.6  1174.6  1759.6  1969.6  2029.6  2044.6  2129.6
  2294.1  2309.1  2379.6  2434.6  2454.6  2584.6  2619.6  2874.6  2934.6  2994.6
  3069.6  3094.6  3129.6  3174.6  3354.6    3628    3643    3813    3838    3963
  4232.5  4347.5  4567.5  4612.5  4637.5  4654.4 4684.29  4684.4  4820.5  4934.3
 4938.51  4938.6 5100.19  5100.3  5110.2 5110.31  5140.6    5354    5614    5629
    5669  5908.2  6199.1  6819.1  7049.1  7650.8  8060.8  8385.8  8400.8  8445.8
    59.6   59.01   58.74   58.68   58.62   57.46   57.05   56.93    56.9   56.44
    55.3    55.8   55.51    55.3   56.21   56.41   55.61   55.51   54.93   55.51
   55.11   54.81   55.31   54.75   54.51   54.03      54    53.7   53.66   53.44
   53.39   53.44   53.54   53.56   53.57   53.58   53.66   55.86   56.28   56.31
   56.31   56.31   56.34   56.34   56.38   54.18   54.21   53.66   53.23   53.21
   53.14    53.6   53.01    54.1    55.6    57.8      58    59.1    58.7    59.5
    59.6      59    56.3    56.3    58.1    57.3    56.2    56.8      56    56.2
   55.01   55.04    54.8    55.3    56.2    56.4    55.6    55.5    54.6    55.5
    55.1    54.4    55.3    54.1    53.9    52.5      53    52.3    51.6    52.8
      51    52.1    51.9    51.3    50.1      51   51.27   51.27   52.39   52.25
   50.95   52.01   52.04   50.97      53   53.01   53.53      53    51.1    51.6
    51.3    52.8      53    54.1    55.6    57.8      58    59.1    58.7    59.5
  1069.6  1084.6  1114.6  1144.6  1174.6  1759.6  1969.6  2029.6  2044.6  2129.6
  2294.1  2309.1  2379.6  2434.6  2454.6  2584.6  2619.6  2874.6  2934.6  2994.6
  3069.6  3094.6  3129.6  3174.6  3354.6    3628    3643    3813    3838    3963
  4232.5  4347.5  4567.5  4612.5  4637.5  4654.4 4684.29  4684.4  4820.5  4934.3
 4938.51  4938.6 5100.19  5100.3  5110.2 5110.31  5140.6    5354    5614    5629
    5669  5908.2  6199.1  6819.1  7049.1  7650.8  8060.8  8385.8  8400.8  8445.8
    59.6   59.01   58.74   58.68   58.62   57.46   57.05   56.93    56.9   56.44
    55.3    55.8   55.51    55.3   56.21   56.41   55.61   55.51   54.93   55.51
   55.11   54.81   55.31   54.75   54.51   54.03      54    53.7   53.66   53.44
   53.39   53.44   53.54   53.56   53.57   53.58   53.66   55.86   56.28   56.31
   56.31   56.31   56.34   56.34   56.38   54.18   54.21   53.66   53.23   53.21
   53.14    53.6   53.01    54.1    55.6    57.8      58    59.1    58.7    59.5
   59.49   58.89   56.19   56.19   57.99   57.19   56.09   56.69   55.89   56.09
    54.9   54.93   54.69   55.19   56.09   56.29   55.49   55.39   54.49   55.39
   54.99   54.29   55.19   53.99   53.79   52.39   52.89   52.19   51.49   52.69
   50.89   51.99   51.79   51.19   49.99   50.89   51.16   51.16   52.28   52.14
   50.84    51.9   51.93   50.86   52.89    52.9   53.42   52.89   50.99   51.49
   51.19   52.69   52.89   53.99   55.49   57.69   57.89   58.99   58.59   59.39
Pier Skew, UpSta & Num, DnSta & Num=  ,4992, 2 ,4992, 2 , 0 , 0 , 0 ,,
     1.7     1.7
   31.71   53.02
     1.7     1.7
    31.6   52.91
Pier Skew, UpSta & Num, DnSta & Num=  ,5046.7, 2 ,5046.7, 2 , 0 , 0 , 0 ,,
     1.7     1.7
   38.81   53.03
     1.7     1.7
    38.7   52.92
BR Coef= 1 , 1 , 0 ,1.25, 0 ,,,0.8,0,2,0,
WSPro=,,,, 1 ,,,, 0 ,,,, 0 ,,,,-1 ,-1 ,-1 , 0 , 0 , 0 , 0 , 0
BR U #Sta/Elev= 162
  1069.6    59.6    1084   59.02  1084.1   59.02  1084.6      59  1114.6    56.3
  1129.6    56.5  1144.6    56.3  1174.6    58.1  1759.6    57.3  1774.6    56.9
  1804.6    57.1  1819.6    56.7  1834.6    56.8  1904.6    56.4  1944.6    56.7
  1969.6    56.2  2029.6    56.8  2044.6      56  2094.1   56.12  2129.6    56.2
  2184.1   55.98  2219.1   55.84  2249.1   55.72  2254.6    55.7  2274.6      55
  2289.6      55  2294.1   55.01  2309.1   55.04  2334.6    55.1  2379.6    54.8
  2418.3   55.15  2429.1   55.25  2434.6    55.3  2449.6    56.1  2454.6    56.2
  2484.6    55.9  2524.6    56.4  2554.6    56.1  2584.6    56.4  2619.6    55.6
  2874.6    55.5  2919.6      55  2934.6    54.6  2994.6    55.5  3069.6    55.1
  3094.6    54.4  3129.6    55.3  3174.6    54.1  3246.6   53.94  3309.6    53.8
  3354.6    53.9  3369.6    53.6  3399.6    53.7  3474.6    52.9  3484.6    53.2
    3523    53.1    3553    52.9    3563    53.1    3588    52.7    3603    52.8
    3628    52.5    3643      53    3813    52.3    3838    51.6    3963    52.8
    3973    52.6  3977.5    52.7  4039.7   52.37  4222.5    51.4  4232.5      51
  4347.5    52.1  4402.5    51.9  4432.5    52.3  4567.5    51.9  4612.5    51.3
  4637.5    50.1  4647.5    50.4  4654.4      51  4657.5   50.95  4657.6   50.95
  4658.1   50.96 4684.29   51.27  4684.4   51.27 4684.51   51.28  4719.9    51.7
    4755   52.13  4777.6   52.22  4820.5   52.39  4845.3   52.19    4878   51.92
  4934.3   52.25  4938.4   50.98 4938.51   50.95  4938.6   50.92  4938.7   50.89
    4987   35.94    4992   32.78  4992.3   32.83  4996.3   31.98  5008.1   32.85
  5013.1   35.64  5017.2   38.89  5046.7   39.84  5082.3   45.98  5099.6   50.81
  5099.7   50.84 5100.19   50.94  5100.3   50.97  5100.4   50.99    5110      53
 5110.09      53  5110.2      53 5110.31   53.01  5140.6   53.53  5166.7   53.49
  5216.9   53.42  5231.7   53.32  5278.7      53  5290.1   52.96  5342.2   52.78
  5343.2   52.91  5343.3   52.92    5354      53    5509      52    5579    51.6
    5614    51.1    5629    51.6    5669    51.3  5692.7   51.69  5718.2    52.1
  5743.3   52.16  5898.2    52.5  5908.2    52.8  5948.2    52.5  5953.6   52.51
  6199.1      53  6274.1    53.1  6293.2   53.37  6293.3   53.37  6309.1    53.6
  6654.1    54.1  6804.1    54.4  6819.1    54.1  7049.1    55.6  7059.1    55.4
  7304.1    56.5  7319.1    56.4  7335.8    56.7  7650.8    57.8  7675.8    57.5
  7695.8    57.8  7755.8    58.1  7770.8    57.8  7905.8      58  8060.8      58
  8070.8    58.3  8175.8    58.6  8190.8    58.4  8285.8    58.5  8385.8    59.1
  8400.8    58.7  8445.8    59.5
BR U #Mann= 7
  1069.6      .2  1084.1      .1  2418.3      .1  4934.3    .035    5110      .1
  5743.3      .1  6293.2      .2
BR U Banks=4934.3,5110
BR D #Sta/Elev= 162
  1069.6   59.49    1084   58.91  1084.1   58.91  1084.6   58.89  1114.6   56.19
  1129.6   56.39  1144.6   56.19  1174.6   57.99  1759.6   57.19  1774.6   56.79
  1804.6   56.99  1819.6   56.59  1834.6   56.69  1904.6   56.29  1944.6   56.59
  1969.6   56.09  2029.6   56.69  2044.6   55.89  2094.1   56.01  2129.6   56.09
  2184.1   55.87  2219.1   55.73  2249.1   55.61  2254.6   55.59  2274.6   54.89
  2289.6   54.89  2294.1    54.9  2309.1   54.93  2334.6   54.99  2379.6   54.69
  2418.3   55.04  2429.1   55.14  2434.6   55.19  2449.6   55.99  2454.6   56.09
  2484.6   55.79  2524.6   56.29  2554.6   55.99  2584.6   56.29  2619.6   55.49
  2874.6   55.39  2919.6   54.89  2934.6   54.49  2994.6   55.39  3069.6   54.99
  3094.6   54.29  3129.6   55.19  3174.6   53.99  3246.6   53.83  3309.6   53.69
  3354.6   53.79  3369.6   53.49  3399.6   53.59  3474.6   52.79  3484.6   53.09
    3523   52.99    3553   52.79    3563   52.99    3588   52.59    3603   52.69
    3628   52.39    3643   52.89    3813   52.19    3838   51.49    3963   52.69
    3973   52.49  3977.5   52.59  4039.7   52.26  4222.5   51.29  4232.5   50.89
  4347.5   51.99  4402.5   51.79  4432.5   52.19  4567.5   51.79  4612.5   51.19
  4637.5   49.99  4647.5   50.29  4654.4   50.89  4657.5   50.84  4657.6   50.84
  4658.1   50.85 4684.29   51.16  4684.4   51.16 4684.51   51.17  4719.9   51.59
    4755   52.02  4777.6   52.11  4820.5   52.28  4845.3   52.08    4878   51.81
  4934.3   52.14  4938.4   50.87 4938.51   50.84  4938.6   50.81  4938.7   50.78
    4987   35.83    4992   32.67  4992.3   32.72  4996.3   31.87  5008.1   32.74
  5013.1   35.53  5017.2   38.78  5046.7   39.73  5082.3   45.87  5099.6    50.7
  5099.7   50.73 5100.19   50.83  5100.3   50.86  5100.4   50.88    5110   52.89
 5110.09   52.89  5110.2   52.89 5110.31    52.9  5140.6   53.42  5166.7   53.38
  5216.9   53.31  5231.7   53.21  5278.7   52.89  5290.1   52.85  5342.2   52.67
  5343.2    52.8  5343.3   52.81    5354   52.89    5509   51.89    5579   51.49
    5614   50.99    5629   51.49    5669   51.19  5692.7   51.58  5718.2   51.99
  5743.3   52.05  5898.2   52.39  5908.2   52.69  5948.2   52.39  5953.6    52.4
  6199.1   52.89  6274.1   52.99  6293.2   53.26  6293.3   53.26  6309.1   53.49
  6654.1   53.99  6804.1   54.29  6819.1   53.99  7049.1   55.49  7059.1   55.29
  7304.1   56.39  7319.1   56.29  7335.8   56.59  7650.8   57.69  7675.8   57.39
  7695.8   57.69  7755.8   57.99  7770.8   57.69  7905.8   57.89  8060.8   57.89
  8070.8   58.19  8175.8   58.49  8190.8   58.29  8285.8   58.39  8385.8   58.99
  8400.8   58.59  8445.8   59.39
BR D #Mann= 7
  1069.6      .2  1084.1      .1  2418.3      .1  4934.3    .035    5110      .1
  5743.3      .1  6293.2      .2
BR D Banks=4934.3,5110
BC Design=,, 0 ,, 0 ,,,,,,
BC HTab HWMax=59.62
BC Use User HTab Curves=0
BC User HTab FreeFlow(D)= 0

Type RM Length L Ch R = 1 ,7221.8  ,41.7,41.7,41.7
BEGIN DESCRIPTION:
Downstream Section of Bridge/Culvert/Weir
END DESCRIPTION:
XS GIS Cut Line= 6
      3164981.02     13906647.76      3162810.52     13906535.82
      3161071.86     13906450.63      3160363.03     13906434.37
      3160102.91     13906453.88        3157622.     13906690.83
#Sta/Elev= 30
  1069.6   59.52  1084.1   58.94  1114.6   56.22  1144.6   56.22  1174.6   58.02
  2418.3   55.07  2524.6   56.32  2934.6   54.52  3129.6   55.22  3174.6   54.02
    3838   51.52    3963   52.72  4232.5   50.92  4567.5   51.82  4637.5   50.02
    4755   52.05  4934.3   52.17    4987   35.86    4992    32.7  4996.3    31.9
  5008.1   32.77  5017.2   38.81  5046.7   39.76  5082.3    45.9    5110   52.92
    5354   52.92    5614   51.02  5743.3   52.08  6293.2   53.29  8445.8   59.42
#Mann= 7 , 1 , 0
  1069.6      .2       0  1084.1      .1       0  2418.3      .1       0
  4934.3    .035       0    5110      .1       0  5743.3      .1       0
  6293.2      .2       0
#XS Ineff= 2 , 0
       0  4928.5    53.3  5110.3       0    53.1
Permanent Ineff=
       F       F
Bank Sta=4934.3,5110
XS Rating Curve= 0 ,0
Exp/Cntr=0.5,0.3

Type RM Length L Ch R = 1 ,7180.1  ,121.3,147.1,110.7
BEGIN DESCRIPTION:
Cross Section 7180.1 - Interpolated
END DESCRIPTION:
XS GIS Cut Line= 6
       3165031.9     13906551.72      3163045.91     13906463.98
      3161906.49     13906446.53      3160205.95     13906384.75
       3158800.8     13906546.86       3157004.8     13906591.12
#Sta/Elev= 30
  1038.3      59  1371.3   57.62    2114    56.3  2234.1    54.9  2324.2    55.5
  3449.9    52.9  4814.4    53.3    4861      52  4901.1    49.1    4921    45.5
  4940.7   39.35  4959.1   38.44  4968.1   39.14  4974.9    36.8  4984.1   36.77
  4991.3   34.56  4992.8   32.65    4993   34.16  5006.2   32.01  5008.7    34.7
  5011.1      36  5016.8    35.8  5031.3    38.2  5060.2    46.6  5089.1    51.8
  5116.2    53.1  5266.3    54.3  5296.3    53.6  6393.4   54.23  9079.2      59
#Mann= 5 , 1 , 0
  1038.3      .2       0  1371.3      .1       0  4814.4    .035       0
  5116.2      .1       0  6393.4      .2       0
Bank Sta=4814.4,5116.2
XS Rating Curve= 0 ,0
Exp/Cntr=0.5,0.3

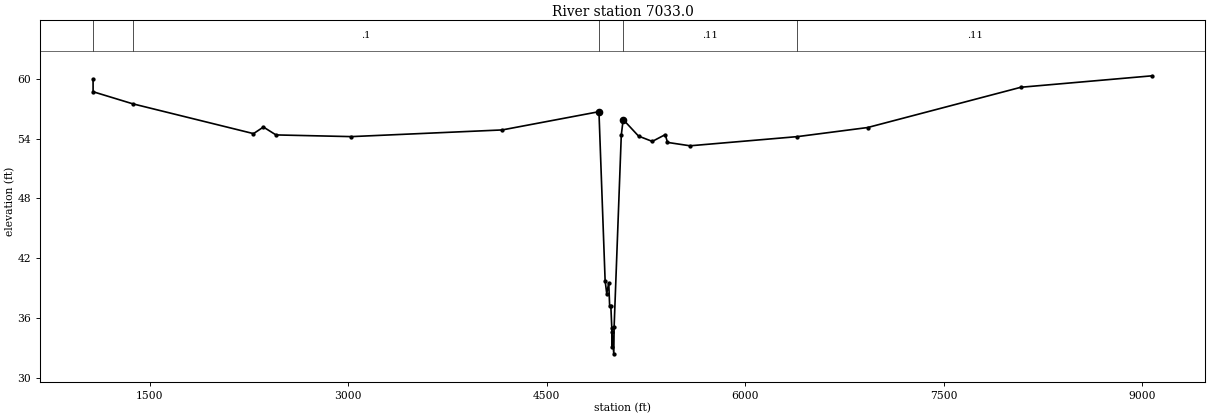
Type RM Length L Ch R = 1 ,7033.0  ,70,70,70
BEGIN DESCRIPTION:
Upstream Section of Bridge/Culvert/Weir
END DESCRIPTION:
XS GIS Cut Line= 6
      3165055.45     13906438.21      3162220.68     13906315.31
       3160645.4     13906260.04       3160222.7     13906263.29
      3158748.25      13906482.2       3157072.1     13906533.98
#Sta/Elev= 30
  1071.8   59.97  1071.9    58.7  1371.3   57.49  2283.9    54.5  2358.9   55.16
  2453.9   54.37  3023.3    54.2  4163.2   54.87  4894.1    56.7  4940.7   39.76
  4952.9   38.46  4968.1   39.55  4974.9   37.21  4984.1   37.18  4991.3   34.97
  4992.8   33.06    4993   34.57  5006.2   32.42  5008.7   35.11  5062.9   54.36
  5077.2   55.91  5193.5   54.25  5297.1   53.72    5395    54.4  5411.9   53.62
  5582.2   53.28  6393.4    54.2  6923.7   55.11  8082.8   59.15  9076.2    60.3
#Mann= 5 ,-1 , 0
  1071.8      .2       0  1371.3      .1       0  4894.1    .035       0
  5077.2     .11       0  6393.4     .11       0
#XS Ineff= 2 , 0
       0    4888   54.43    5074       0   53.47
Permanent Ineff=
       F       F
Bank Sta=4894.1,5077.2
XS Rating Curve= 0 ,0
Exp/Cntr=0.5,0.3