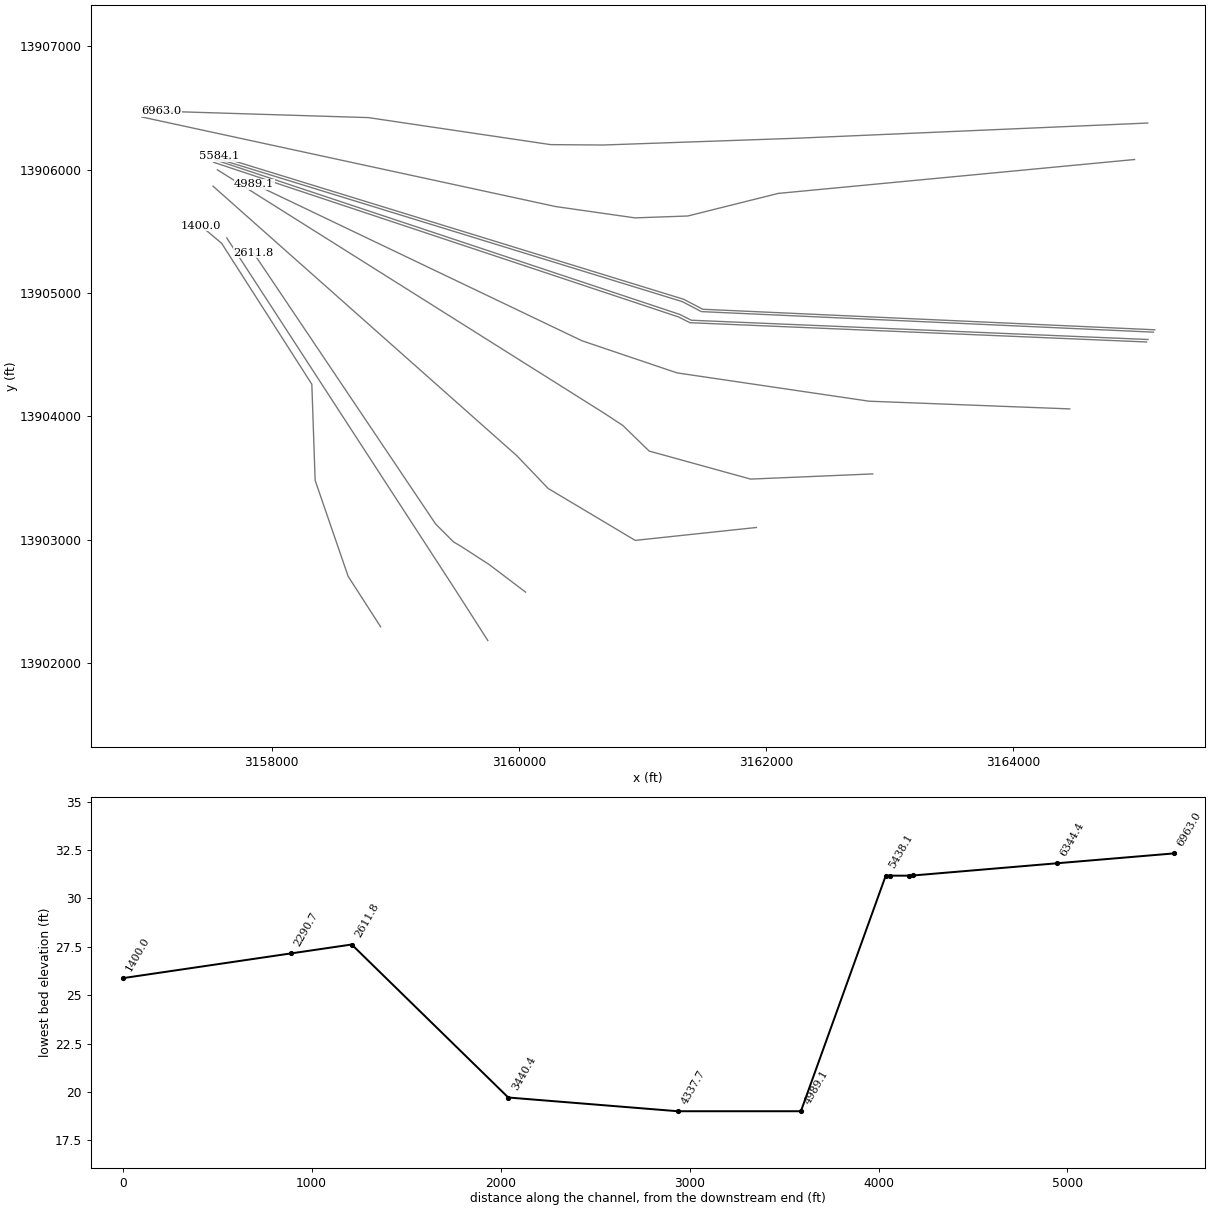
HEC-RAS study P130-00-00.prj: P130-00-00

--- P130-00-00.g01 (geometry) --- (continued)

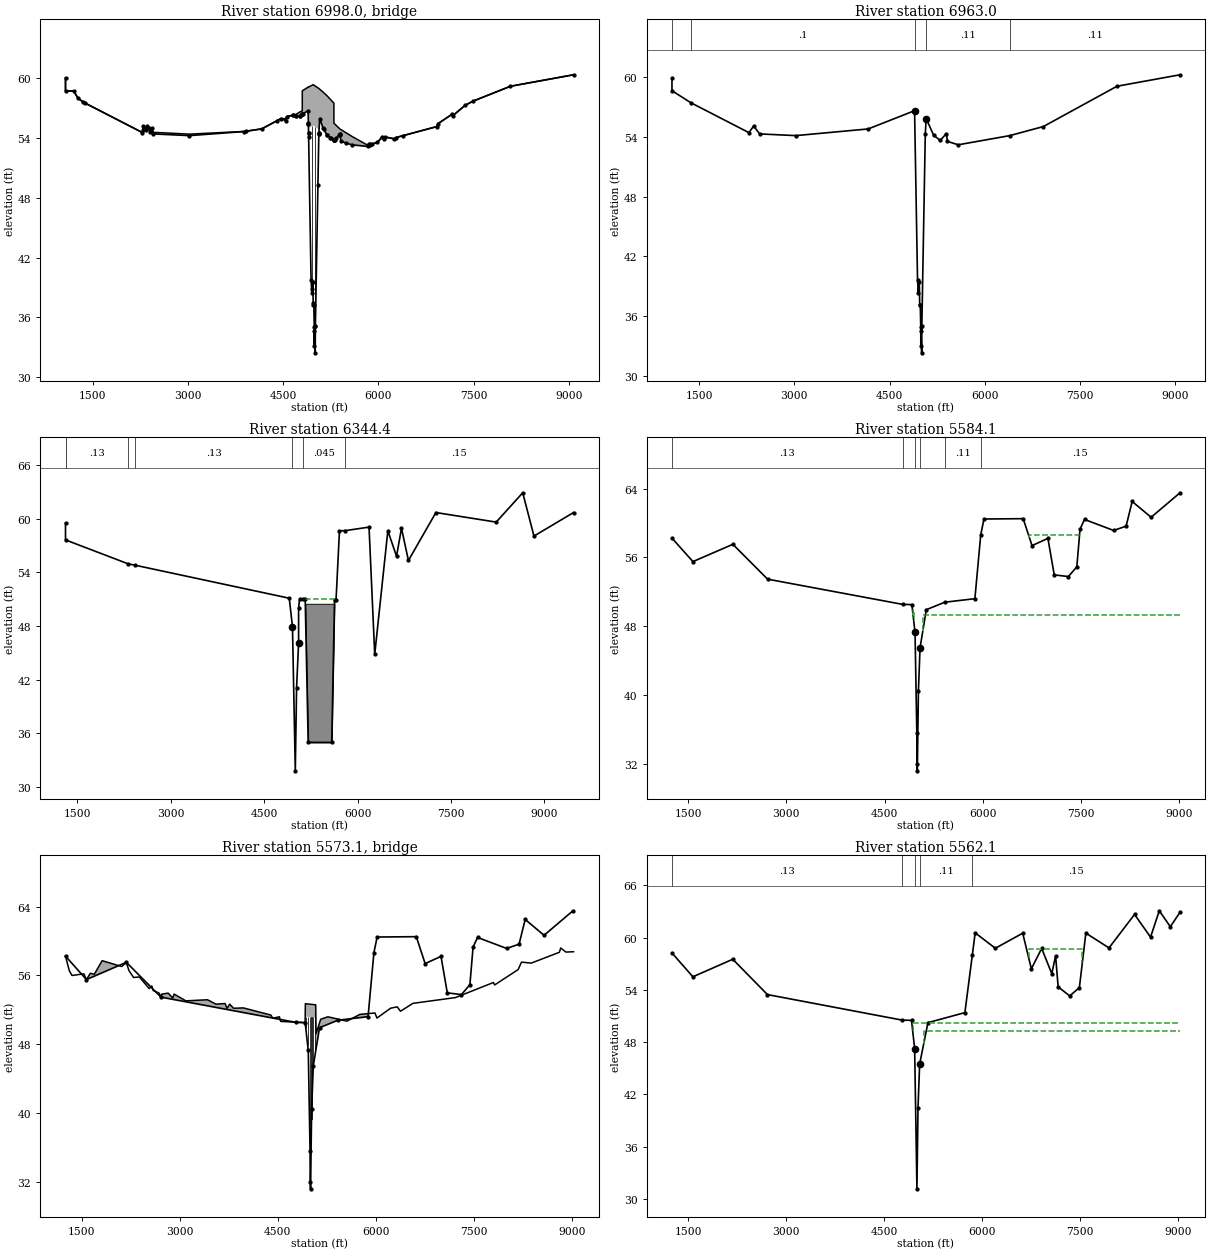
Type RM Length L Ch R = 3 ,6998.0  ,,,
BEGIN DESCRIPTION:
EAST BELTWAY 8
Structure ID: P30-6,,,,
END DESCRIPTION:
Bridge Culvert--1,0,-1,-1, 0
Deck Dist Width WeirC Skew NumUp NumDn MinLoCord MaxHiCord MaxSubmerge Is_Ogee
10,50,2.6,0, 58, 58, , , 0.95, 0, 1,1,,
  1071.8  1071.9  1201.9  1266.9  1353.9  2283.9  2298.9  2343.9  2358.9  2383.9
  2403.9  2433.9  2453.9  3023.3  3888.2  4163.2  4468.2  4538.2  4558.2  4653.8
  4707.4  4766.4 4802.19  4802.3  4894.1  4898.3  4901.1  4974.9  5062.9 5064.09
  5064.2  5077.2  5137.6  5193.5  5300.8 5300.91  5340.7    5395  5396.9  5411.9
  5582.2  5832.2  5847.2  5862.2  5985.1  6065.1  6090.1  6105.1  6253.7  6283.7
  6923.7  6938.7  7163.7  7173.7  7367.8  7497.8  8082.8  9076.2
      60   58.73   58.69      58   57.58   54.54   55.16   54.85    55.2   54.99
   54.64   55.01   54.56   54.38   54.65   54.91   55.95   55.92   56.15   56.27
   56.38   56.61   56.72   58.72   59.09   59.11    59.1   59.34   58.96   58.95
   58.95   58.88   58.55   58.22   57.48   55.48   55.23    54.9   54.89   54.83
   54.16   53.27   53.42    53.3   53.55   54.13   53.95    54.1   53.91   54.05
   55.14   55.42   56.38   56.22   57.27    57.7   59.18   60.33
      60   58.73   58.69      58   57.58   54.53   55.15   54.84   55.19   54.98
   54.63      55    54.4   54.23   54.64    54.9   55.94   55.73   56.14   56.26
    56.2   56.21   56.36   56.36   56.73   55.39      55   55.24   54.86   54.85
   54.53   55.94   54.85   54.28   53.77   53.77   53.97   54.43   54.28   53.65
   53.31   53.14   53.41   53.29   53.54   54.12   53.94   54.09    53.9   54.04
   55.14   55.42   56.38   56.22   57.27    57.7   59.18   60.33
  1071.8  1071.9  1201.9  1266.9  1353.9  2283.9  2298.9  2343.9  2358.9  2383.9
  2403.9  2433.9  2453.9  3023.3  3888.2  4163.2  4468.2  4538.2  4558.2  4653.8
  4707.4  4766.4 4802.19  4802.3  4894.1  4898.3  4901.1  4974.9  5062.9 5064.09
  5064.2  5077.2  5137.6  5193.5  5300.8 5300.91  5340.7    5395  5396.9  5411.9
  5582.2  5832.2  5847.2  5862.2  5985.1  6065.1  6090.1  6105.1  6253.7  6283.7
  6923.7  6938.7  7163.7  7173.7  7367.8  7497.8  8082.8  9076.2
      60   58.73   58.69      58   57.58   54.54   55.16   54.85    55.2   54.99
   54.64   55.01   54.56   54.38   54.65   54.91   55.95   55.92   56.15   56.27
   56.38   56.61   56.72   58.72   59.09   59.11    59.1   59.34   58.96   58.95
   58.95   58.88   58.55   58.22   57.48   55.48   55.23    54.9   54.89   54.83
   54.16   53.27   53.42    53.3   53.55   54.13   53.95    54.1   53.91   54.05
   55.14   55.42   56.38   56.22   57.27    57.7   59.18   60.33
   59.89   58.62   58.58   57.89   57.47   54.42   55.04   54.73   55.08   54.87
   54.52   54.89   54.29   54.12   54.53   54.79   55.83   55.62   56.03   56.15
   56.09    56.1   56.25   56.25   56.62   55.28   54.89   55.13   54.75   54.74
   54.42   55.83   54.74   54.17   53.66   53.66   53.86   54.32   54.17   53.54
    53.2   53.03    53.3   53.18   53.43   54.01   53.83   53.98   53.79   53.93
   55.03   55.31   56.27   56.11   57.16   57.59   59.07   60.22
Pier Skew, UpSta & Num, DnSta & Num=  ,4952.9, 2 ,4952.9, 2 , 0 , 0 , 0 ,,
     1.7     1.7
   37.54   56.17
     1.7     1.7
   37.43   56.06
Pier Skew, UpSta & Num, DnSta & Num=  ,5008.8, 2 ,5008.8, 2 , 0 , 0 , 0 ,,
     1.7     1.7
   33.33    56.1
     1.7     1.7
   33.22   55.99
Abutment Skew #Up #Dn= , 2 , 2
  4898.1  4901.2
   55.39   54.47
  4898.1  4901.2
   55.28   54.36
Abutment Skew #Up #Dn= , 2 , 2
  5062.9 5064.29
   54.39   54.85
  5062.9 5064.29
   54.28   54.74
BR Coef= 1 , 1 , 0 ,1.25, 0 ,,,0.8,0,2,0,
WSPro=,,,, 1 ,,,, 0 ,,,, 0 ,,,,-1 ,-1 ,-1 , 0 , 0 , 0 , 0 , 0
BR U #Sta/Elev= 99
  1071.8      60  1071.9   58.73  1201.9   58.69  1266.9      58  1353.9   57.58
  1371.3   57.52  2283.9   54.53  2291.3   54.84  2298.9   55.15  2326.3   54.96
  2343.9   54.84  2358.9   55.19  2383.9   54.98  2403.9   54.63  2433.9      55
  2453.9    54.4  3023.3   54.23  3888.2   54.64  3909.2   54.66  4163.2    54.9
    4405   55.72  4468.2   55.94  4538.2   55.73  4558.2   56.14  4653.8   56.26
  4655.9   56.26  4707.4    56.2    4711    56.2  4761.5   56.21  4766.4   56.21
 4802.19   56.36  4802.3   56.36 4802.41   56.36  4814.5   56.41  4894.1   56.73
  4898.1   55.46 4898.21   55.42  4898.3   55.39  4901.1    54.5  4901.2   54.47
  4902.1   54.14  4940.7   39.79  4952.9   38.49  4959.1   38.88  4968.1   39.58
  4974.3   37.45  4974.9   37.24  4984.1   37.21  4991.3      35  4992.8   33.09
    4993    34.6  5006.2   32.45  5008.7   35.14  5008.8   35.14  5048.4   49.23
  5062.8   54.35  5062.9   54.39 5064.09   54.52  5064.2   54.53  5077.2   55.94
  5131.6   54.96  5137.6   54.85  5193.5   54.28  5193.9   54.28  5246.1   54.04
  5252.3      54  5297.1   53.75 5300.69   53.77  5300.8   53.77 5300.91   53.77
  5311.5   53.82  5340.7   53.97  5384.2   54.34  5394.9   54.43    5395   54.43
  5396.9   54.28  5411.9   53.65  5485.9    53.5  5582.2   53.31  5832.2   53.14
  5847.2   53.41  5862.2   53.29  5865.1   53.34  5908.6   53.41  5985.1   53.54
  6065.1   54.12  6090.1   53.94  6105.1   54.09  6253.7    53.9  6283.7   54.04
  6393.4   54.23  6923.7   55.14  6938.7   55.42  7163.7   56.38  7173.7   56.22
  7367.8   57.27  7497.8    57.7  8082.8   59.18  9076.2   60.33
BR U #Mann= 5
  1071.8      .2  1371.3      .1  4894.1    .035  5077.2     .11  6393.4     .11
BR U Banks=4894.1,5077.2
BR D #Sta/Elev= 99
  1071.8   59.89  1071.9   58.62  1201.9   58.58  1266.9   57.89  1353.9   57.47
  1371.3   57.41  2283.9   54.42  2291.3   54.73  2298.9   55.04  2326.3   54.85
  2343.9   54.73  2358.9   55.08  2383.9   54.87  2403.9   54.52  2433.9   54.89
  2453.9   54.29  3023.3   54.12  3888.2   54.53  3909.2   54.55  4163.2   54.79
    4405   55.61  4468.2   55.83  4538.2   55.62  4558.2   56.03  4653.8   56.15
  4655.9   56.15  4707.4   56.09    4711   56.09  4761.5    56.1  4766.4    56.1
 4802.19   56.25  4802.3   56.25 4802.41   56.25  4814.5    56.3  4894.1   56.62
  4898.1   55.35 4898.21   55.31  4898.3   55.28  4901.1   54.39  4901.2   54.36
  4902.1   54.03  4940.7   39.68  4952.9   38.38  4959.1   38.77  4968.1   39.47
  4974.3   37.34  4974.9   37.13  4984.1    37.1  4991.3   34.89  4992.8   32.98
    4993   34.49  5006.2   32.34  5008.7   35.03  5008.8   35.03  5048.4   49.12
  5062.8   54.24  5062.9   54.28 5064.09   54.41  5064.2   54.42  5077.2   55.83
  5131.6   54.85  5137.6   54.74  5193.5   54.17  5193.9   54.17  5246.1   53.93
  5252.3   53.89  5297.1   53.64 5300.69   53.66  5300.8   53.66 5300.91   53.66
  5311.5   53.71  5340.7   53.86  5384.2   54.23  5394.9   54.32    5395   54.32
  5396.9   54.17  5411.9   53.54  5485.9   53.39  5582.2    53.2  5832.2   53.03
  5847.2    53.3  5862.2   53.18  5865.1   53.23  5908.6    53.3  5985.1   53.43
  6065.1   54.01  6090.1   53.83  6105.1   53.98  6253.7   53.79  6283.7   53.93
  6393.4   54.12  6923.7   55.03  6938.7   55.31  7163.7   56.27  7173.7   56.11
  7367.8   57.16  7497.8   57.59  8082.8   59.07  9076.2   60.22
BR D #Mann= 5
  1071.8      .2  1371.3      .1  4894.1    .035  5077.2     .11  6393.4     .11
BR D Banks=4894.1,5077.2
BC Design=,, 0 ,, 0 ,,,,,,
BC HTab HWMax=60.3
BC Use User HTab Curves=0
BC User HTab FreeFlow(D)= 0

Type RM Length L Ch R = 1 ,6963.0  ,618.6,618.6,618.6
BEGIN DESCRIPTION:
Downstream Section of Bridge/Culvert/Weir
END DESCRIPTION:
XS GIS Cut Line= 6
      3165089.89     13906377.26      3162255.12     13906254.37
      3160679.84      13906199.1      3160257.14     13906202.35
      3158782.69     13906421.26      3157106.54     13906473.03
#Sta/Elev= 30
  1071.8   59.88  1071.9   58.61  1371.3    57.4  2283.9   54.41  2358.9   55.07
  2453.9   54.28  3023.3   54.11  4163.2   54.78  4894.1   56.61  4940.7   39.67
  4952.9   38.37  4968.1   39.46  4974.9   37.12  4984.1   37.09  4991.3   34.88
  4992.8   32.97    4993   34.48  5006.2   32.33  5008.7   35.02  5062.9   54.27
  5077.2   55.82  5193.5   54.16  5297.1   53.63    5395   54.31  5411.9   53.53
  5582.2   53.19  6393.4   54.11  6923.7   55.02  8082.8   59.06  9076.2   60.21
#Mann= 5 ,-1 , 0
  1071.8      .2       0  1371.3      .1       0  4894.1    .035       0
  5077.2     .11       0  6393.4     .11       0
#XS Ineff= 2 , 0
       0    4888   54.43    5074       0   53.47
Permanent Ineff=
       F       F
Bank Sta=4894.1,5077.2
XS Rating Curve= 0 ,0
Exp/Cntr=0.5,0.3

Type RM Length L Ch R = 1 ,6344.4  ,1028.5,760.3,483.8
BEGIN DESCRIPTION:
Cross Section 6344.4 - Interpolated
END DESCRIPTION:
XS GIS Cut Line= 6
      3164983.93     13906081.71      3162100.02     13905807.06
       3161367.6     13905623.95      3160940.35     13905608.69
      3160299.49     13905700.24 3156948.6278919  13906426.26229
#Sta/Elev= 30
  1312.2    59.5  1312.3   57.64  2319.5   54.96  2430.2   54.81  4904.4   51.12
  4955.8   47.91    5001   31.82  5021.6   41.07  5053.8   46.12 5054.18   50.02
 5069.19      51 5129.23      51    5160      51    5208      35    5586      35
    5631    50.9    5655    50.9    5710   58.65    5804   58.68 6184.85   59.07
 6275.91   44.84 6486.69   58.66 6626.27   55.81 6705.66   58.94 6817.16   55.34
 7258.19    60.7 8226.14   59.63 8651.79   62.91 8832.37   58.07 9467.77    60.7
#Mann= 7 ,-1 , 0
  1312.2      .2       0  1312.3     .13       0  2319.5      .1       0
  2430.2     .13       0  4955.8    .045       0 5129.23    .045       0
    5804     .15       0
#XS Ineff= 3 ,-1
 5159.24    5631      51    5710    5810   58.65 6184.85 7198.84   59.07
Permanent Ineff=
       T       T       F
#Block Obstruct= 1 ,-1
 5159.24    5650    50.5
Bank Sta=4955.8,5053.8
XS Rating Curve= 0 ,0
Exp/Cntr=0.5,0.3

Type RM Length L Ch R = 1 ,5584.1  ,22,22,22
BEGIN DESCRIPTION:
Upstream Section of Bridge/Culvert/Weir
END DESCRIPTION:
XS GIS Cut Line= 5
      3165147.26     13904701.77      3161488.79     13904868.19
      3161333.88     13904949.22      3157577.05     13906106.11
 3157577.040666913906106.1128741
#Sta/Elev= 30
  1253.9   58.24  1573.9   55.51  2183.9   57.52  2713.9   53.47  4775.2   50.54
    4918   50.51 4965.89   47.28  4993.1   35.61 4995.46   32.04 5000.92   31.19
 5017.38   40.44 5042.41   45.49 5138.06   49.92 5420.58   50.79    5880    51.2
 5969.82   58.66    6019   60.46 6617.51    60.5 6752.62   57.37 6995.24   58.21
  7091.5   53.97 7307.51   53.77 7436.79   54.91 7485.72   59.29 7553.98   60.41
 7998.79   59.13 8189.07   59.63 8282.23    62.5 8571.02   60.66 9012.58   63.51
#Mann= 6 ,-1 , 0
  1253.9     .13       0  4775.2     .13       0 4965.89    .045       0
 5042.41     .11       0 5420.58     .11       0 5969.82     .15       0
#XS Ineff= 3 ,-1
 4935.45 4945.38   49.89 5084.41 5084.41   49.32 6713.92 7475.52   58.66
Permanent Ineff=
       F       F       F
Bank Sta=4965.89,5042.41
XS Rating Curve= 0 ,0
Exp/Cntr=0.5,0.3

Type RM Length L Ch R = 3 ,5573.1  ,,,
BEGIN DESCRIPTION:
18" PIPELINE
END DESCRIPTION:
Bridge Culvert--1,0,-1,-1, 0
Deck Dist Width WeirC Skew NumUp NumDn MinLoCord MaxHiCord MaxSubmerge Is_Ogee
10,2,2.6,0, 60, 60, , , 0.95, 0, 1,1,,
  1253.9  1313.9  1353.9  1533.9  1573.9  1633.9  1693.9  1813.9  2113.9  2183.9
  2223.9  2293.9  2383.9  2533.9  2573.9  2593.9  2683.9  2713.9  2723.9  2823.9
  2893.9  2913.9  3093.9  3423.9  3553.9  3693.9  3723.9  3763.9  3823.9  3973.9
  4393.9  4423.9  4523.9  4543.9  4917.5    4918    4921 5068.12  5079.7 5085.19
  5155.7  5265.7  5555.7  5755.7  5985.7  6015.7  6225.7  6325.7  6375.7  6565.7
  7215.7  7795.7  7815.7  8175.7  8225.7  8375.7  8805.7  8825.7  8905.7  9021.9
   58.23    56.5   55.99   56.18    55.5   56.25   56.13   57.71   57.03   57.51
   56.56   55.76   55.81   54.46   54.77   54.24   53.95   53.46   53.82   53.94
   53.37   53.83   53.04   53.17   52.66   52.73   52.17   52.66   52.18   52.22
   51.39   51.02   51.19   50.65   50.51    50.8   52.71   52.59   52.58   49.23
    50.9   51.19   50.68   51.47   51.63   51.04   52.19   52.34   51.83   52.75
   53.42   55.17   54.89   56.68   57.54   57.43   58.69   59.19   58.71   58.75
                                                                                
                                                                                
                                                                                
                                            50.5   51.21   51.09
                                                                                
                                                                                
  1253.9  1313.9  1353.9  1533.9  1573.9  1633.9  1693.9  1813.9  2113.9  2183.9
  2223.9  2293.9  2383.9  2533.9  2573.9  2593.9  2683.9  2713.9  2723.9  2823.9
  2893.9  2913.9  3093.9  3423.9  3553.9  3693.9  3723.9  3763.9  3823.9  3973.9
  4393.9  4423.9  4523.9  4543.9  4917.5    4918    4921 5068.12  5079.7 5085.19
  5155.7  5265.7  5555.7  5755.7  5985.7  6015.7  6225.7  6325.7  6375.7  6565.7
  7215.7  7795.7  7815.7  8175.7  8225.7  8375.7  8805.7  8825.7  8905.7  9021.9
   58.23    56.5   55.99   56.18    55.5   56.25   56.13   57.71   57.03   57.51
   56.56   55.76   55.81   54.46   54.77   54.24   53.95   53.46   53.82   53.94
   53.37   53.83   53.04   53.17   52.66   52.73   52.17   52.66   52.18   52.22
   51.39   51.02   51.19   50.65   50.51    50.8   52.71   52.59   52.58   49.23
    50.9   51.19   50.68   51.47   51.63   51.04   52.19   52.34   51.83   52.75
   53.42   55.17   54.89   56.68   57.54   57.43   58.69   59.19   58.71   58.75
                                                                                
                                                                                
                                                                                
                                            50.5   51.21   51.09
                                                                                
                                                                                
Pier Skew, UpSta & Num, DnSta & Num=  ,4927.3, 2 ,4927.3, 2 , 0 , 0 , 0 ,,
     1.5     1.5
    49.3    52.2
     1.5     1.5
    49.3    52.2
Pier Skew, UpSta & Num, DnSta & Num=  ,4956.6, 2 ,4956.6, 2 , 0 , 0 , 0 ,,
     1.5     1.5
      47   52.18
     1.5     1.5
      47   52.18
Pier Skew, UpSta & Num, DnSta & Num=  ,4986.1, 2 ,4986.1, 2 , 0 , 0 , 0 ,,
     1.5     1.5
   37.28   52.16
     1.5     1.5
   37.28   52.16
Pier Skew, UpSta & Num, DnSta & Num=  ,5015.4, 2 ,5015.4, 2 , 0 , 0 , 0 ,,
     1.5     1.5
   37.71   52.13
     1.5     1.5
   37.71   52.13
Pier Skew, UpSta & Num, DnSta & Num=  ,5044.7, 2 ,5044.7, 2 , 0 , 0 , 0 ,,
     1.5     1.5
    44.6   52.11
     1.5     1.5
    44.6   52.11
Pier Skew, UpSta & Num, DnSta & Num=  ,5074, 2 ,5074, 2 , 0 , 0 , 0 ,,
     1.5     1.5
   47.05   52.09
     1.5     1.5
   47.05   52.09
BR Coef= 1 , 1 , 0 ,1.25, 0 ,,,0.8,0,2,0,
WSPro=,,,, 1 ,,,, 0 ,,,, 0 ,,,,-1 ,-1 ,-1 , 0 , 0 , 0 , 0 , 0
BC Design=,, 0 ,, 0 ,,,,,,
BC HTab HWMax=59.16
BC Use User HTab Curves=0
BC User HTab FreeFlow(D)= 0

Type RM Length L Ch R = 1 ,5562.1  ,101,101,101
BEGIN DESCRIPTION:
Downstream Section of Bridge/Culvert/Weir
END DESCRIPTION:
XS GIS Cut Line= 5
      3165136.45     13904682.61      3161477.97     13904849.03
      3161323.06     13904930.06      3157566.24     13906086.95
 3157566.230666913906086.9528741
#Sta/Elev= 30
  1253.9   58.23  1573.9    55.5  2183.9   57.51  2713.9   53.46  4775.2   50.53
    4918    50.5 4965.89   47.27 5000.92   31.18 5017.38   40.43 5042.41   45.48
 5169.46   50.24 5734.49   51.39 5848.51      58 5891.81   60.54 6200.29   58.77
 6619.19    60.5 6751.16   56.41 6909.12   58.75 7064.08   55.86 7122.07   57.91
 7161.06   54.35 7338.01    53.3 7485.98   54.26 7584.95   60.51 7938.87   58.81
 8329.77   62.65 8574.65   60.05 8708.57   63.07 8877.46   61.24 9025.36    62.9
#Mann= 5 ,-1 , 0
  1253.9     .13       0  4775.2     .13       0 4965.89    .045       0
 5042.41     .11       0 5848.51     .15       0
#XS Ineff= 3 ,-1
 4935.45 4935.45   50.17 5104.27 5104.27   49.27 6710.83 7530.11   58.63
Permanent Ineff=
       F       F       F
Bank Sta=4965.89,5042.41
XS Rating Curve= 0 ,0
Exp/Cntr=0.5,0.3

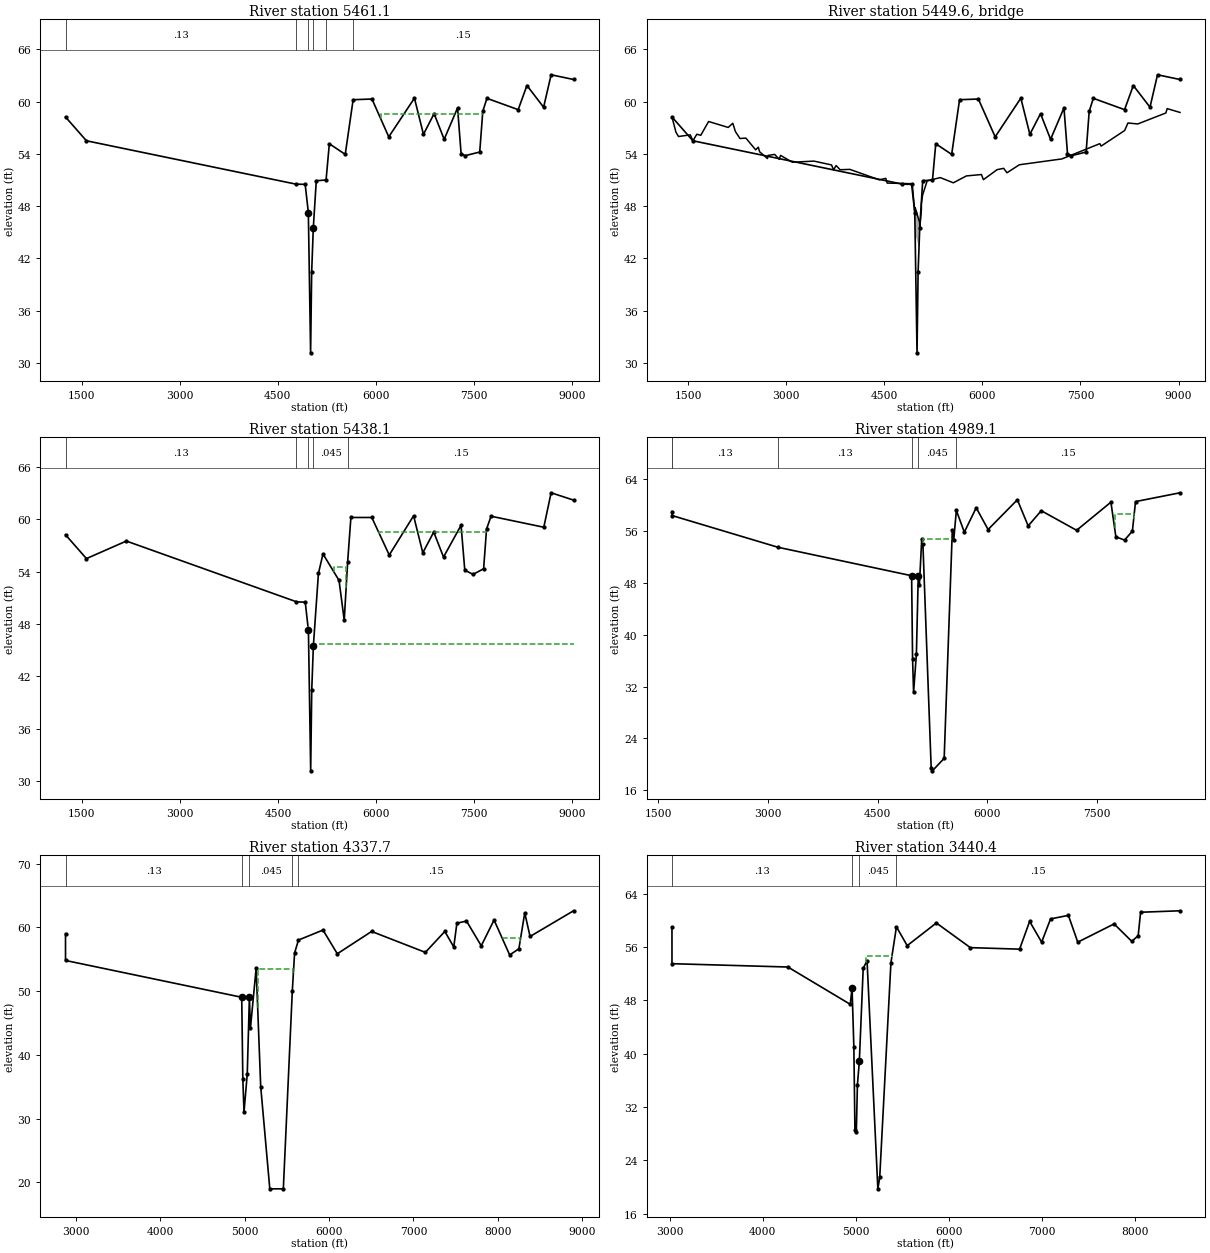
Type RM Length L Ch R = 1 ,5461.1  ,23,23,23
BEGIN DESCRIPTION:
Upstream Section of Bridge/Culvert/Weir
END DESCRIPTION:
XS GIS Cut Line= 4
      3165092.11     13904623.13      3161396.08     13904779.26
      3161304.33     13904825.73      3157541.77     13906079.11
#Sta/Elev= 30
  1253.9   58.23  1573.9    55.5  4775.2   50.53    4918    50.5 4966.29   47.27
  5000.9   31.18 5017.17   40.43 5041.91   45.48 5087.69   50.92 5237.29      51
  5287.3   55.16 5530.38   53.94 5650.94   60.21 5938.84   60.29 6195.57   55.95
 6588.17   60.39 6726.04   56.24  6888.9   58.61 7042.75   55.67 7247.57   59.27
 7301.52   54.03 7362.46   53.79  7586.3   54.21 7633.28   58.88 7696.25   60.37
 8174.03   59.07 8307.97   61.84 8562.85   59.35 8677.79   63.07 9020.63   62.53
#Mann= 6 ,-1 , 0
  1253.9     .13       0  4775.2     .07       0 4966.29    .045       0
 5041.91     .11       0 5237.29     .11       0 5650.94     .15       0
#XS Ineff= 3 ,-1
 4955.31 4965.24   47.18 5044.69 5044.69   45.66 6076.76 7633.2858.53585
Permanent Ineff=
       F       F       F
Bank Sta=4966.29,5041.91
XS Rating Curve= 0 ,0
Exp/Cntr=0.5,0.3

Type RM Length L Ch R = 3 ,5449.6  ,,,
BEGIN DESCRIPTION:
36" PIPELINE
END DESCRIPTION:
Bridge Culvert--1,0,-1,-1, 0
Deck Dist Width WeirC Skew NumUp NumDn MinLoCord MaxHiCord MaxSubmerge Is_Ogee
10,3,2.6,0, 60, 60, , , 0.95, 0, 1,1,,
  1253.9  1313.9  1353.9  1533.9  1573.9  1633.9  1693.9  1813.9  2113.9  2183.9
  2223.9  2293.9  2383.9  2533.9  2573.9  2593.9  2713.9  2723.9  2823.9  2893.9
  2913.9  3093.9  3423.9  3693.9  3723.9  3763.9  3823.9  3973.9  4423.9  4523.9
  4543.9    4908 4931.93 4966.29  4971.9 5031.19 5040.99 5041.91  5067.3    5068
  5085.7  5155.7  5355.7  5555.7  5755.7  5985.7  6015.7  6225.7  6325.7  6375.7
  6565.7  7215.7  7795.7  7815.7  8175.7  8225.7  8375.7  8805.7  8825.7  9021.9
   58.23    56.5   55.99   56.18    55.5   56.25   56.13   57.71   57.03   57.51
   56.56   55.76   55.81   54.46   54.77   54.24   53.46   53.82   53.94   53.37
   53.83   53.04   53.17   52.73   52.17   52.66   52.18   52.22   51.02   51.19
   50.65   50.58   50.24   47.27   47.85   46.36   46.11   45.48   47.54   48.28
   49.27    50.9   51.28   50.68   51.47   51.63   51.04   52.19   52.34   51.83
   52.75   53.42   55.17   54.89   56.68   57.54   57.43   58.69   59.19   58.75
   58.23    56.5   55.99   56.18    55.5   56.25   56.13   57.71   57.03   57.51
   56.56   55.76   55.81   54.46   54.77   54.24   53.46   53.82   53.94   53.37
   53.83   53.04   53.17   52.73   52.17   52.66   52.18   52.22   51.02   51.19
   50.65   50.58   50.24   47.27   44.84   43.29   45.29   45.48   47.54   48.28
   49.27    50.9   51.28   50.68   51.47   51.63   51.04   52.19   52.34   51.83
   52.75   53.42   55.17   54.89   56.68   57.54   57.43   58.69   59.19   58.75
  1253.9  1313.9  1353.9  1533.9  1573.9  1633.9  1693.9  1813.9  2113.9  2183.9
  2223.9  2293.9  2383.9  2533.9  2573.9  2593.9  2713.9  2723.9  2823.9  2893.9
  2913.9  3093.9  3423.9  3693.9  3723.9  3763.9  3823.9  3973.9  4423.9  4523.9
  4543.9    4908 4931.93 4966.29  4971.9 5031.19 5040.99 5041.91  5067.3    5068
  5085.7  5155.7  5355.7  5555.7  5755.7  5985.7  6015.7  6225.7  6325.7  6375.7
  6565.7  7215.7  7795.7  7815.7  8175.7  8225.7  8375.7  8805.7  8825.7  9021.9
   58.23    56.5   55.99   56.18    55.5   56.25   56.13   57.71   57.03   57.51
   56.56   55.76   55.81   54.46   54.77   54.24   53.46   53.82   53.94   53.37
   53.83   53.04   53.17   52.73   52.17   52.66   52.18   52.22   51.02   51.19
   50.65   50.58   50.24   47.27   47.85   46.36   46.11   45.48   47.54   48.28
   49.27    50.9   51.28   50.68   51.47   51.63   51.04   52.19   52.34   51.83
   52.75   53.42   55.17   54.89   56.68   57.54   57.43   58.69   59.19   58.75
   58.23    56.5   55.99   56.18    55.5   56.25   56.13   57.71   57.03   57.51
   56.56   55.76   55.81   54.46   54.77   54.24   53.46   53.82   53.94   53.37
   53.83   53.04   53.17   52.73   52.17   52.66   52.18   52.22   51.02   51.19
   50.65   50.58   50.24   47.27   44.84   43.29   45.29   45.48   47.54   48.28
   49.27    50.9   51.28   50.68   51.47   51.63   51.04   52.19   52.34   51.83
   52.75   53.42   55.17   54.89   56.68   57.54   57.43   58.69   59.19   58.75
BR Coef= 1 , 1 , 0 ,1.25, 0 ,,,0.8,0,2,0,
WSPro=,,,, 1 ,,,, 0 ,,,, 0 ,,,,-1 ,-1 ,-1 , 0 , 0 , 0 , 0 , 0
BC Design=,, 0 ,, 0 ,,,,,,
BC HTab HWMax=59.12
BC Use User HTab Curves=0
BC User HTab FreeFlow(D)= 0

Type RM Length L Ch R = 1 ,5438.1  ,449,449,449
BEGIN DESCRIPTION:
Downstream Section of Bridge/Culvert/Weir
END DESCRIPTION:
XS GIS Cut Line= 4
       3165080.8      13904603.1      3161384.78     13904759.22
      3161293.03     13904805.69      3157530.47     13906059.08
#Sta/Elev= 30
  1253.9   58.23  1573.9    55.5  2183.9   57.51  4783.9   50.55    4918    50.5
 4966.29   47.27  5000.9   31.18 5017.17   40.43 5041.91   45.48  5119.3    53.8
 5188.95   56.03  5434.3      53 5513.59   48.44 5566.29   55.16 5615.35   60.21
 5934.76  60.2126201.705 55.91026573.587 60.40436714.498   56.166881.393 58.5397
7031.298 55.67797299.128 59.31557356.092 54.17417483.012 53.6893 7643.91 54.3365
7688.885 58.89247757.855 60.35538563.505 59.09258675.456 63.04149018.307 62.2019
#Mann= 5 ,-1 , 0
  1253.9     .13       0  4783.9     .07       0 4966.29    .045       0
 5041.91    .045       0 5566.29     .15       0
#XS Ineff= 4 ,-1
 4964.36 4965.83   47.63 5042.23 5042.23   45.69 5352.53 5541.21   54.54
 6052.58 7688.84   58.51
Permanent Ineff=
       F       F       F       F
Bank Sta=4966.29,5041.91
XS Rating Curve= 0 ,0
Exp/Cntr=0.5,0.3

Type RM Length L Ch R = 1 ,4989.1  ,925.8,651.4,364.8
BEGIN DESCRIPTION:
Cross Section 4989.1 - Interpolated
END DESCRIPTION:
XS GIS Cut Line= 6
      3164459.13    13904060.689      3162834.13    13904123.189
     3161282.046    13904352.356     3161188.296    13904383.605
      3160511.21     13904612.77     3157859.013    13905882.438
#Sta/Elev= 30
  1687.1      59  1687.2    58.4  3137.2    53.5  4964.9   49.11    4978   36.26
  4991.8   31.13  5030.3   37.04  5055.8   49.12  5071.1   47.64 5103.38   54.76
 5119.52   53.95 5232.52   19.43 5248.66      19 5410.08   20.93  5521.9   56.19
 5540.93   54.63 5576.82   59.18 5685.86   55.83 5848.29    59.6 6010.81   56.24
 6411.31   60.83 6559.12    56.8    6738   59.14 7221.89   56.12 7690.79   60.46
 7758.73   55.11 7877.63   54.61 7984.53      56 8027.49   60.55 8635.94   61.91
#Mann= 6 ,-1 , 0
  1687.1      .2       0  1687.2     .13       0  3137.2     .13       0
  4964.9    .045       0  5055.8    .045       0 5576.82     .15       0
#XS Ineff= 2 ,-1
 5115.19 5520.36   54.78 7741.34 8000.73   58.63
Permanent Ineff=
       T       F
Bank Sta=4964.9,5055.8
XS Rating Curve= 0 ,0
Exp/Cntr=0.3,0.1

Type RM Length L Ch R = 1 ,4337.7  ,1006,897.3,641.6
BEGIN DESCRIPTION:
Cross Section  4337.7
END DESCRIPTION:
XS GIS Cut Line= 6
3162864.9003543713903533.8764075      3161876.02      13903491.8
      3161055.14     13903718.94      3160841.28     13903926.85
      3160690.79     13904025.86 3157560.398262113905998.4147938
#Sta/Elev= 30
  2876.8      59  2876.9    54.8  4964.9   49.03    4978   36.18  4991.8   31.05
  5030.3   36.96  5055.8   49.04 5067.77   44.16 5135.91   53.59 5189.78   35.03
 5297.51      19 5457.89      19 5564.27      50 5591.26   55.97    5637      58
 5927.74   59.57 6097.41   55.85 6503.98   59.35 7140.69   56.07 7371.51   59.35
  7477.4   56.92 7514.37   60.64 7628.25   60.98 7803.08    57.1 7954.93   61.14
 8139.75   55.67 8248.62   56.62 8318.53   62.26 8381.44   58.56 8896.75   62.59
#Mann= 5 ,-1 , 0
  2876.8     .13       0  4964.9    .045       0  5055.8    .045       0
 5564.27    .045       0    5637     .15       0
#XS Ineff= 2 ,-1
 5153.92 5574.98   53.51 8054.94 8258.67   58.28
Permanent Ineff=
       T       F
Bank Sta=4964.9,5055.8
XS Rating Curve= 0 ,0
Exp/Cntr=0.3,0.1

Type RM Length L Ch R = 1 ,3440.4  ,948.8,828.6,731.7
BEGIN DESCRIPTION:
Cross Section  3440.4
END DESCRIPTION:
XS GIS Cut Line= 6
      3161923.11     13903099.71      3160941.95     13902995.21
      3160237.33     13903415.97      3159984.24     13903680.98
      3157548.56     13905844.713157525.0480265313905865.5968005
#Sta/Elev= 30
  3024.6      59  3024.7    53.5  4271.3      53    4942    47.4  4961.1   49.85
  4980.4   41.04  4992.1   28.53    5007   28.25 5018.67   35.28 5039.41   38.84
  5080.9   52.78 5122.38   53.95 5238.57   19.71 5258.64   21.42 5379.02   53.62
  5438.4   59.03 5554.24   56.21 5867.71   59.61 6233.19   55.91 6762.83   55.68
  6870.8   59.85 6999.77   56.73  7095.7   60.22 7287.52   60.75 7388.43   56.73
 7779.08   59.47 7968.99   56.85 8037.98    57.7 8063.97   61.22 8487.85   61.44
#Mann= 4 ,-1 , 0
  3024.6     .13       0  4961.1    .045       0 5039.41    .045       0
  5438.4     .15       0
#XS Ineff= 1 ,-1
 5109.24 5389.27   54.62
Permanent Ineff=
       T
Bank Sta=4961.1,5039.41
XS Rating Curve= 0 ,0
Exp/Cntr=0.3,0.1

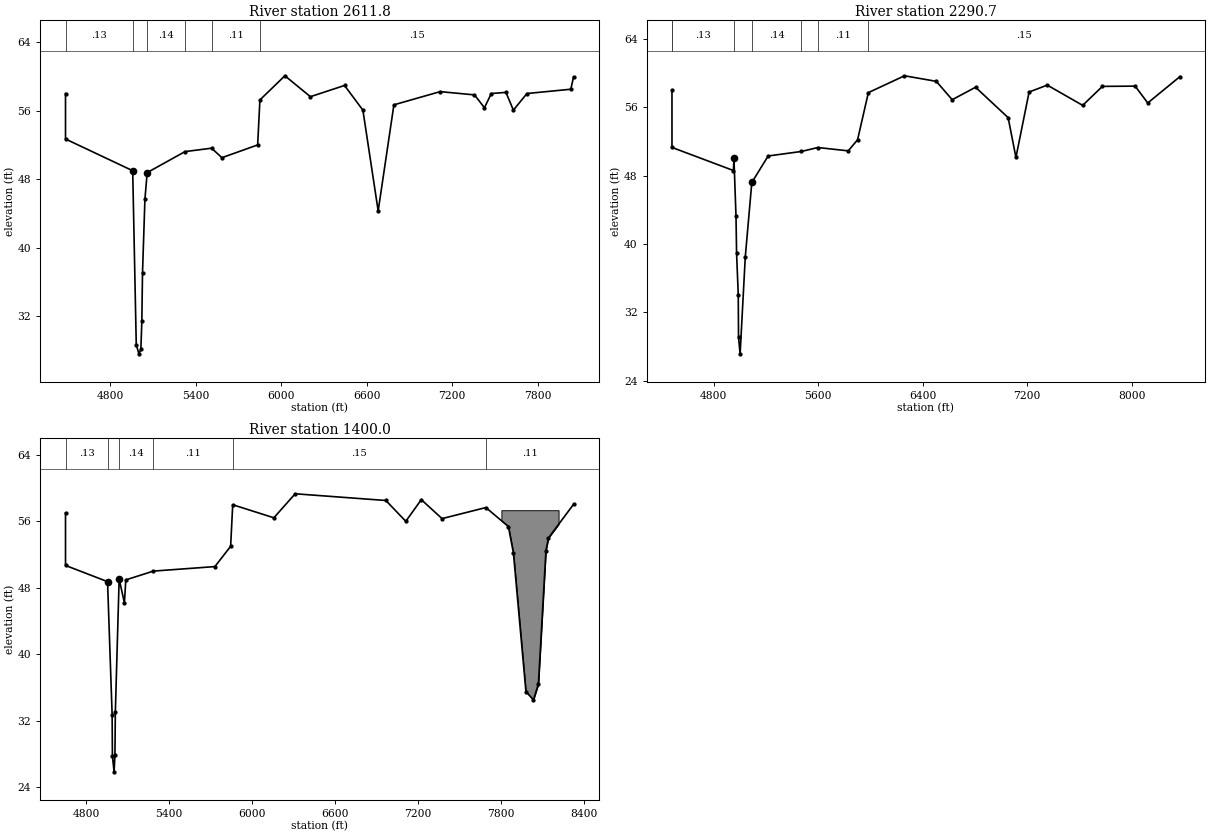
Type RM Length L Ch R = 1 ,2611.8  ,405,321.1,236.8
BEGIN DESCRIPTION:
Cross Section  2611.8
END DESCRIPTION:
XS GIS Cut Line= 6
      3160054.62     13902576.03      3159759.61     13902799.65
      3159534.05     13902945.75      3159472.13     13902982.44
      3159326.84     13903127.733157851.8281022113905326.0062799
#Sta/Elev= 30
    4487      58  4487.1   52.69  4958.3   48.99  4983.3    28.7  5001.6   27.62
  5015.6   28.14  5022.4   31.42  5027.1   37.05    5044   45.65  5059.9   48.77
 5325.18   51.22 5511.75   51.62 5584.01   50.51 5834.85      52  5850.6   57.25
  6025.7   60.07  6204.9   57.63 6444.12   58.94 6573.03   56.06 6680.21    44.3
  6790.5   56.68 7114.94   58.22 7355.85   57.84 7425.64   56.34 7473.81      58
  7576.6   58.13 7628.65   56.06 7723.77      58 8031.38    58.5 8050.65   59.93
#Mann= 6 ,-1 , 0
    4487     .13       0  4958.3    .045       0  5059.9     .14       0
 5325.18     .11       0 5511.75     .11       0  5850.6     .15       0
#XS Ineff= 1 ,-1
 6573.03  6790.5   56.06
Permanent Ineff=
       F
Bank Sta=4958.3,5059.9
XS Rating Curve= 0 ,0
Exp/Cntr=0.3,0.1

Type RM Length L Ch R = 1 ,2290.7  ,832,890.7,580
BEGIN DESCRIPTION:
Cross Section 2290.7 - Interpolated
END DESCRIPTION:
XS GIS Cut Line= 3
3159749.0091930713902183.9274478      3159477.86     13902607.68
 3157636.286541713905445.9920307
#Sta/Elev= 30
  4481.8      58  4481.9    51.3  4951.9    48.6  4955.8   50.03  4971.6   43.27
    4976   38.94  4988.9   34.04  4990.9   29.08  5003.1   27.16  5042.6    38.5
  5092.6    47.2  5217.6    50.3 5472.41   50.83 5597.58   51.29 5830.03    50.9
 5901.55   52.19 5984.19   57.71  6260.6   59.68 6503.92   59.03 6625.51   56.88
 6804.15   58.34 7053.57   54.78 7113.06   50.13 7213.86   57.78 7352.66   58.59
 7623.56   56.22 7774.64   58.44 8024.97   58.47 8121.45    56.5 8368.28   59.59
#Mann= 7 ,-1 , 0
  4481.8      .2       0  4481.9     .13       0  4955.8    .045       0
  5092.6     .14       0 5472.41     .11       0 5597.58     .11       0
 5984.19     .15       0
#XS Ineff= 1 ,-1
 6916.69 7213.86   56.71
Permanent Ineff=
       F
Bank Sta=4955.8,5092.6
XS Rating Curve= 0 ,0
Exp/Cntr=0.3,0.1

Type RM Length L Ch R = 1 ,1400.0  ,0,0,0
BEGIN DESCRIPTION:
Cross Section  1400.0
END DESCRIPTION:
XS GIS Cut Line= 6
      3158881.43     13902294.93      3158618.56     13902703.97
      3158351.57    13903481.194     3158324.754    13904260.433
     3157594.798    13905402.518     3157425.905    13905544.744
#Sta/Elev= 30
  4652.1      57  4652.2    50.7  4955.8   48.75  4988.9   32.76  4990.9    27.8
  5003.1   25.88  5009.2    27.9  5012.1   33.06  5039.6   49.07  5077.6    46.2
 5087.64   48.96 5287.16   50.02 5731.25   50.56    5845      53    5860      58
 6157.21 56.42916311.192 59.31636966.337 58.50867110.329 56.00537222.322 58.6103
7372.313 56.3294 7688.79   57.66 7851.53   55.38 7887.69   52.21  7978.1   35.53
 8032.35   34.53 8068.51   36.46 8122.76   52.47 8140.84      54 8322.17   58.05
#Mann= 6 ,-1 , 0
  4652.1     .13       0  4955.8    .045       0  5039.6     .14       0
 5287.16     .11       0    5860     .15       0 7688.79     .11       0
#Block Obstruct= 1 ,-1
 7800.89    8214   57.34
Bank Sta=4955.8,5039.6
XS Rating Curve= 0 ,0
Exp/Cntr=0.3,0.1
LCMann Table=0

Chan Stop Cuts=-1
Use User Specified Reach Order=0
Composite Channel Slope=5